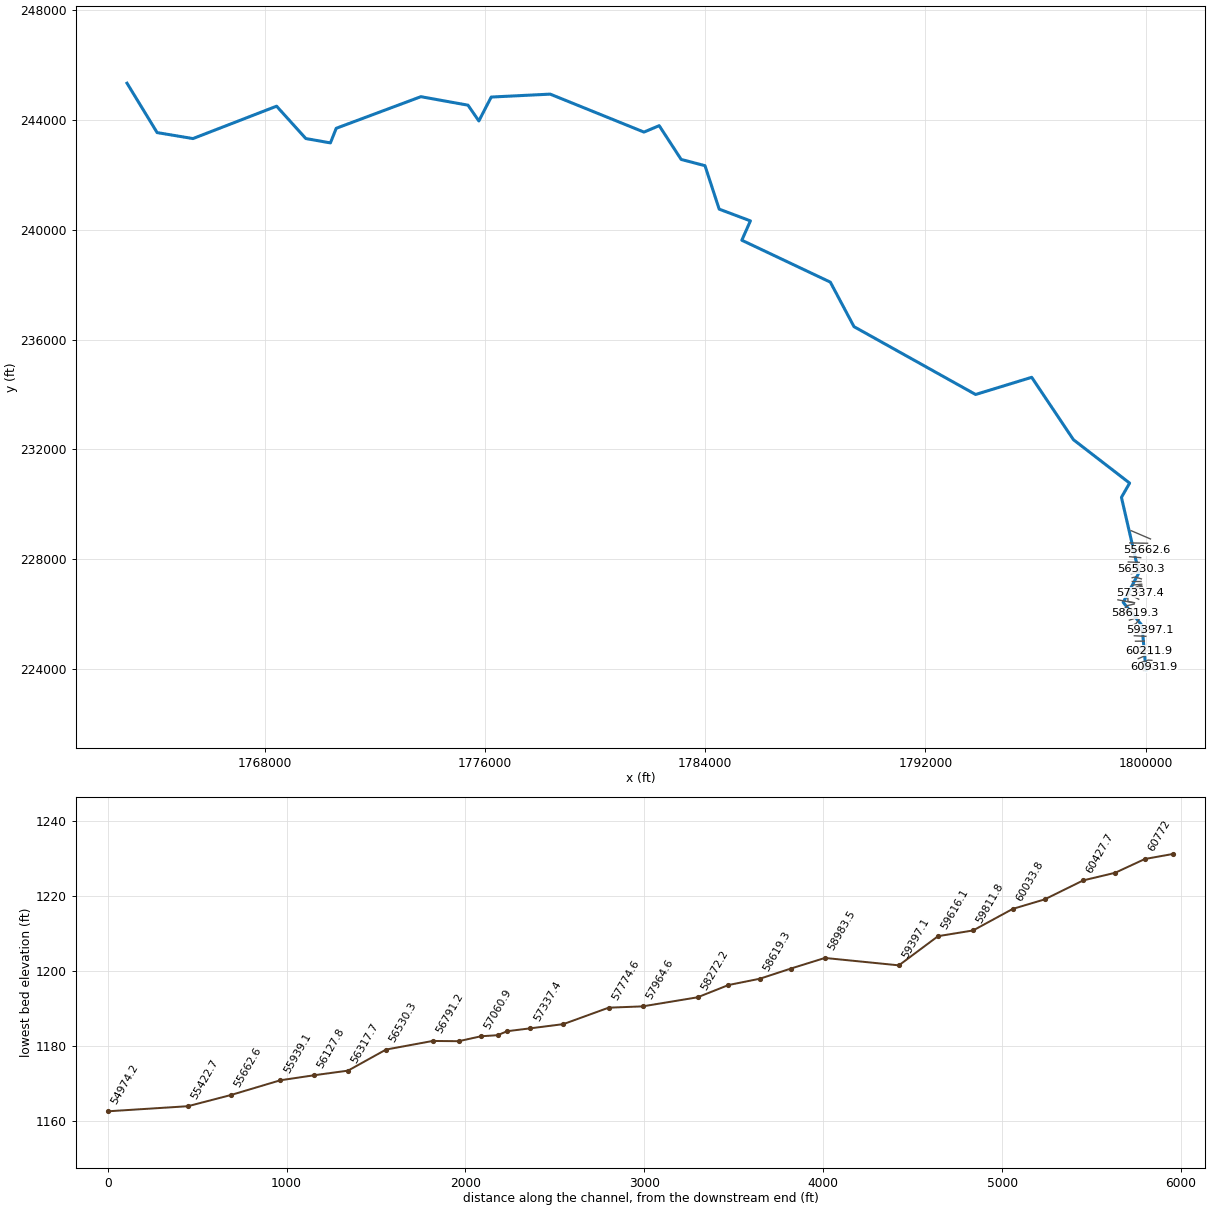
--- ELKCK.prj (project) ---

Proj Title=ELKCK
Current Plan=p01
Default Exp/Contr=0,0
English Units
Geom File=g01
Flow File=f01
Plan File=p01
BEGIN DESCRIPTION:
END DESCRIPTION:
DSS Export Rating Curves= 0
DSS Export Rating Curve Sorted= 0
DSS Export Volume Flow Curves= 0
DXF OffsetX= 0
DXF OffsetY= 0
DXF ScaleX= 0
DXF ScaleY= 0

--- ELKCK.p01 (plan) ---

Plan Title=Floodplain
Program Version=4.00
Geom File=g01
Flow File=f01
K Sum by GR=0
Std Step Tol=0.01
Critical Tol=0.01
Num of Std Step Trials=20
Max Error Tol=0.3
Flow Tol Ratio=0.001
Split Flow NTrial=30
Split Flow Tol=0.02
Split Flow Ratio=0.02
Log Output Level=0
Friction Slope Method=1
Unsteady Friction Slope Method=2
Unsteady Bridges Friction Slope Method=1
Global Log Level=0
CheckData=False
Run HTab=0
Run UNet=0
Run PostProcess=0
UNET Theta=0
UNET Theta Warmup=0
UNET ZTol=0
UNET ZSATol=0
UNET MxIter=0
UNET MaxInSteps=0
UNET DtIC=0
UNET DtMin=0
UNET MaxCRTS=0
UNET WFStab=0
UNET SFStab=0
UNET WFX=0
UNET SFX=0
UNET DSS MLevel=0
UNET DZMax Abort=0
UNET Convert EG Bridges=0
UNET Use Existing IB Tables=0
UNET Froude Limit=0
UNET Froude Power=0
Write IC File=0
Echo Input=False
Echo Output=False
Write Detailed=0

--- ELKCK.f01 (steady flow) ---

Flow Title=NFF Regression Equation
Program Version=5.03
Number of Profiles= 1
Profile Names=P100yr
River Rch & RM=ELKCK,Main            ,60931.9
1085.169
River Rch & RM=ELKCK,Main            ,57964.6
1140.452
River Rch & RM=ELKCK,Main            ,57774.6
2114.766
River Rch & RM=ELKCK,Main            ,56936.9
2121.613
River Rch & RM=ELKCK,Main            ,54135.1
2356.587
River Rch & RM=ELKCK,Main            ,46540.8
2597.789
River Rch & RM=ELKCK,Main            ,46319.3
 3011.07
River Rch & RM=ELKCK,Main            ,46138
3016.495
River Rch & RM=ELKCK,Main            ,34795.1
3346.356
River Rch & RM=ELKCK,Main            ,34116.7
4071.152
River Rch & RM=ELKCK,Main            ,33835.6
4215.179
River Rch & RM=ELKCK,Main            ,24068.3
4609.955
River Rch & RM=ELKCK,Main            ,9388.6
5121.436
River Rch & RM=ELKCK,Main            ,285.1
5591.629
Boundary for River Rch & Prof#=ELKCK,Main            , 1
Up Type= 0
Dn Type= 1
Dn Known WS=1024.2
DSS Import GetInterval= 0
DSS Import GetPeak= 0
DSS Import FillOption= 0

--- ELKCK.g01 (geometry) ---

Geom Title=USGS 10m DEM
Program Version=4.10

River Reach=ELKCK           ,Main
Reach XY= 30
     1800006.346      223977.177     1799860.836      225602.158
     1799179.001      226442.129     1799748.613      227511.625
     1799115.958      230258.667     1799413.306      230777.955
     1797373.222      232355.856     1795856.849      234625.057
     1793819.726      234000.423      1789403.27      236468.061
     1788543.932      238086.968     1785329.259      239611.565
     1785641.516      240314.732     1784507.038      240741.955
     1783991.907      242322.191     1783126.151      242549.897
     1782328.627      243777.724     1781775.764      243544.492
     1778369.164      244924.991     1776227.874      244818.301
     1775778.863      243949.104     1775384.929      244523.106
     1773673.672      244831.721     1770599.595      243682.253
      1770388.17      243150.986     1769494.826      243309.544
     1768433.773      244486.262     1765396.537       243308.25
     1764095.189      243525.484      1763001.59      245322.341

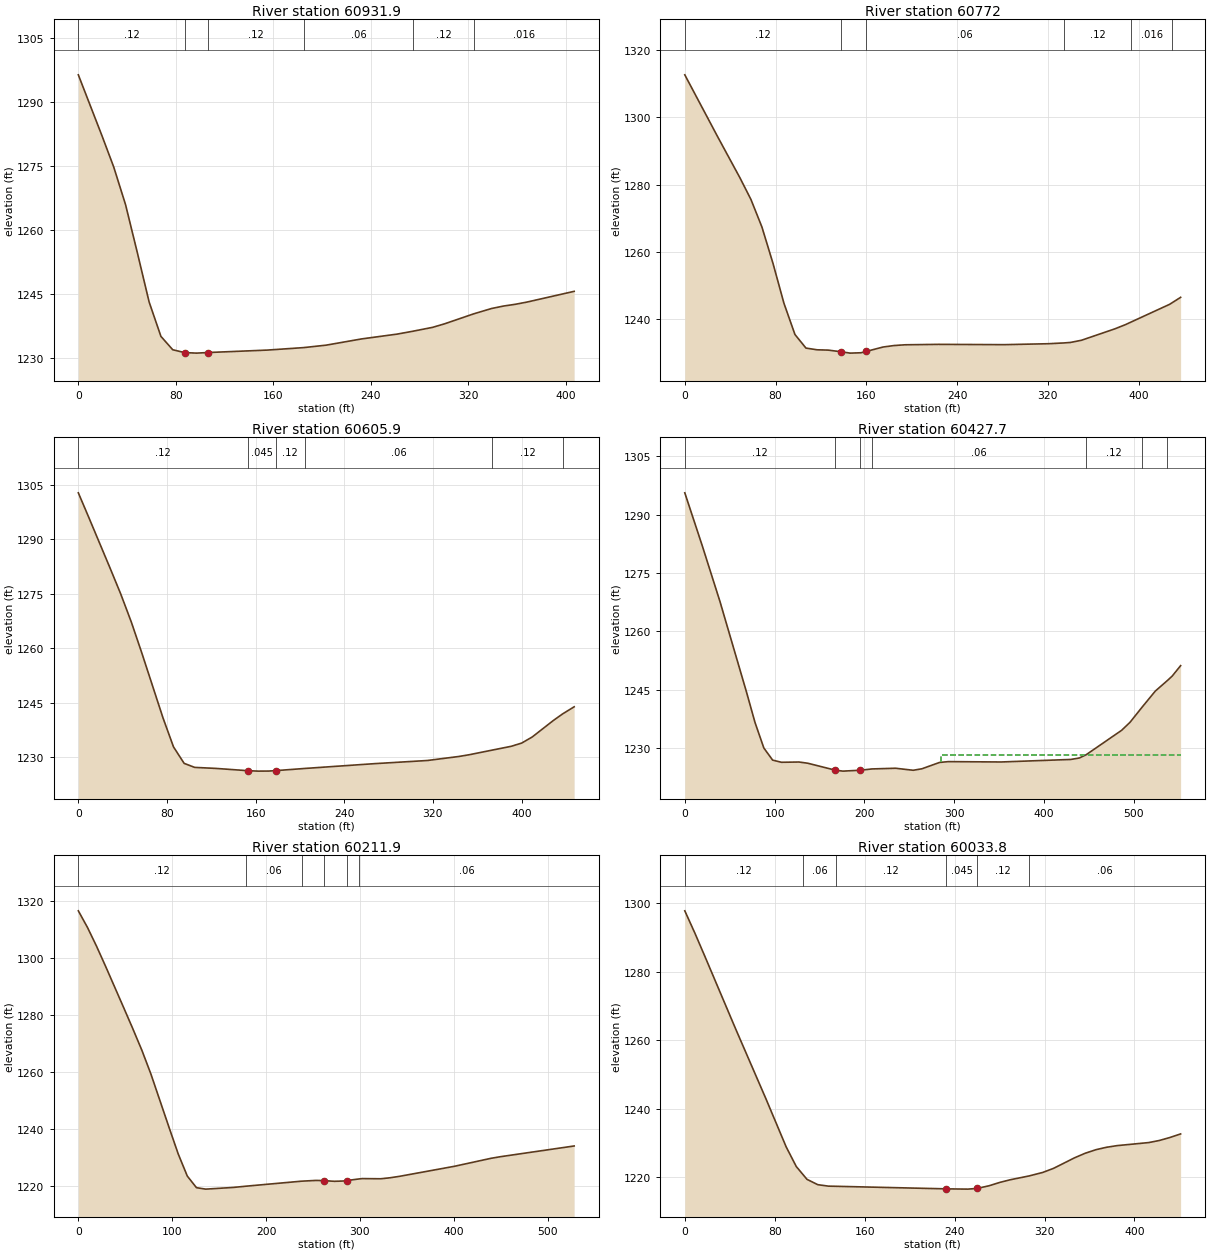
Type RM Length L Ch R = 1 ,60931.9 ,160.5,159.9,159.3
XS GIS Cut Line= 2
     1799915.782      223954.366     1800300.906      224085.998
#Sta/Elev= 25
       0 1296.34    19.4 1282.08    29.1 1274.72    38.8  1265.9    48.4 1254.74
    58.1 1243.16    67.8 1235.09    77.5 1231.96    87.2  1231.3    96.9 1231.17
   106.6 1231.31     155 1231.88  184.831232.459   203.5 1233.04   232.6  1234.5
   261.6 1235.62  274.951236.314   290.7  1237.2   300.4 1238.01  324.451240.361
   339.2 1241.62   348.9 1242.19   358.6  1242.6   368.2 1243.12     407 1245.64
#Mann= 6 ,-1 , 0
       0     .12       0    87.2    .045       0   106.6     .12       0
  184.83     .06       0  274.95     .12       0  324.45    .016       0
Bank Sta=87.2,106.6
XS Rating Curve= 0 ,0
Exp/Cntr=0.3,0.1

Type RM Length L Ch R = 1 ,60772   ,166,166.1,166.1
XS GIS Cut Line= 2
     1799842.865      224084.574     1800257.503      224222.717
#Sta/Elev= 30
       0 1312.66    29.1 1294.14    48.6    1282    58.3 1275.55      68 1267.33
    77.7 1256.56    87.4 1244.63    97.1 1235.34   106.8  1231.3   116.6 1230.79
   126.3  1230.7   137.81230.207   145.7  1229.8   155.4 1229.91  159.681230.287
   174.8 1231.62   184.5 1232.06   194.2 1232.28   223.4 1232.41   281.6 1232.32
   320.5  1232.6  334.341232.837   339.9 1232.98   349.6 1233.63   378.8    1237
   388.5  1238.3  393.681239.112   427.3 1244.33  429.741244.853     437 1246.41
#Mann= 6 ,-1 , 0
       0     .12       0   137.8    .045       0  159.68     .06       0
  334.34     .12       0  393.68    .016       0  429.74     .12       0
Bank Sta=137.8,159.68
XS Rating Curve= 0 ,0
Exp/Cntr=0.3,0.1

Type RM Length L Ch R = 1 ,60605.9 ,176.4,178.3,180.1
XS GIS Cut Line= 3
     1799790.782      224240.824     1800089.393      224341.519
     1800221.337      224331.102
#Sta/Elev= 27
       0 1302.84     9.6 1295.95    28.6 1282.13    38.2 1275.01    47.8 1267.25
    57.3  1258.7    76.4 1240.82    85.9 1232.81    95.5 1228.27     105 1227.16
   124.1 1226.88   152.8 1226.25   162.3 1226.13   171.9 1226.15  177.971226.265
  204.741226.872   267.4 1228.19   315.1 1229.06   343.5 1230.17     353 1230.66
  373.62 1231.93   390.8 1232.98   400.2 1233.87   409.7 1235.55   428.6 1240.06
   437.21241.926   447.5 1243.86
#Mann= 6 ,-1 , 0
       0     .12       0   152.8    .045       0  177.97     .12       0
  204.74     .06       0  373.62     .12       0   437.2    .016       0
Bank Sta=152.8,177.97
XS Rating Curve= 0 ,0
Exp/Cntr=0.3,0.1

Type RM Length L Ch R = 1 ,60427.7 ,220.2,215.8,208.6
XS GIS Cut Line= 3
     1799726.546      224391.866     1800113.048      224557.606
     1800244.482      224554.748
#Sta/Elev= 30
       0 1295.58    19.6 1281.88    39.1 1267.71    68.5 1244.57    78.2 1236.58
      88 1230.05    97.8 1226.94   107.6 1226.38   127.1 1226.45   136.9 1226.14
   167.6 1224.35     176 1224.11   195.6 1224.34  208.511224.674   234.7 1224.85
   254.3 1224.33   264.1 1224.72   283.6 1226.34   293.4 1226.55   352.1 1226.46
   429.9 1227.11   439.3 1227.49   446.71228.301   486.3 1234.59   495.7 1236.66
  508.981240.501   523.8 1244.66  536.731247.267   542.6 1248.51     552  1251.2
#Mann= 7 ,-1 , 0
       0     .12       0   167.6    .045       0   195.6     .12       0
  208.51     .06       0   446.7     .12       0  508.98    .016       0
  536.73     .12       0
#XS Ineff= 2 , 0
                          285.45         1228.24
Permanent Ineff=
       F       F
Bank Sta=167.6,195.6
XS Rating Curve= 0 ,0
Exp/Cntr=0.3,0.1

Type RM Length L Ch R = 1 ,60211.9 ,178.8,178.1,179.9
XS GIS Cut Line= 3
     1799605.018      224598.463     1799712.657      224641.866
     1800122.954      224682.786
#Sta/Elev= 30
       0 1316.56     9.7 1310.77    19.3 1304.24      29 1297.16    48.4 1282.58
      58  1275.3    67.7 1267.72    77.4 1259.33    96.7 1240.65   106.4 1231.43
   116.1 1223.64   125.9 1219.56   135.7 1219.05   165.2 1219.64  178.67 1220.08
  238.241221.843   253.5  1222.1   261.31222.028   273.1 1221.79     283  1221.9
   286.31222.068  299.361222.628   302.6 1222.74   322.2 1222.68     332 1223.02
   341.9 1223.51   400.8 1227.05     440 1229.86   449.8 1230.41   528.4 1234.17
#Mann= 6 ,-1 , 0
       0     .12       0  178.67     .06       0  238.24     .12       0
   261.3    .045       0   286.3     .12       0  299.36     .06       0
Bank Sta=261.3,286.3
XS Rating Curve= 0 ,0
Exp/Cntr=0.3,0.1

Type RM Length L Ch R = 1 ,60033.8 ,226.5,222,217.5
XS GIS Cut Line= 4
     1799592.865      224801.588     1799691.823      224794.644
     1799915.782      224841.519     1800028.629      224834.574
#Sta/Elev= 30
       0  1297.8       9 1291.27      18  1284.4    45.1 1263.42    72.2 1242.89
    90.2 1228.85    99.2 1223.11  105.451220.656   108.7 1219.38   118.3 1217.82
   127.8 1217.39  134.251217.349   232.7  1216.6   251.7 1216.52     260 1216.72
   270.8 1217.51   280.3 1218.49   289.9 1219.28  306.351220.376   318.5  1221.4
     328 1222.58   346.9 1225.69   356.3 1227.01   365.7 1228.03   375.1 1228.74
   384.5 1229.22   412.8 1230.12   422.2 1230.73   431.6  1231.6   441.1 1232.64
#Mann= 6 ,-1 , 0
       0     .12       0  105.45     .06       0  134.25     .12       0
   232.7    .045       0     260     .12       0  306.35     .06       0
Bank Sta=232.7,260
XS Rating Curve= 0 ,0
Exp/Cntr=0.3,0.1

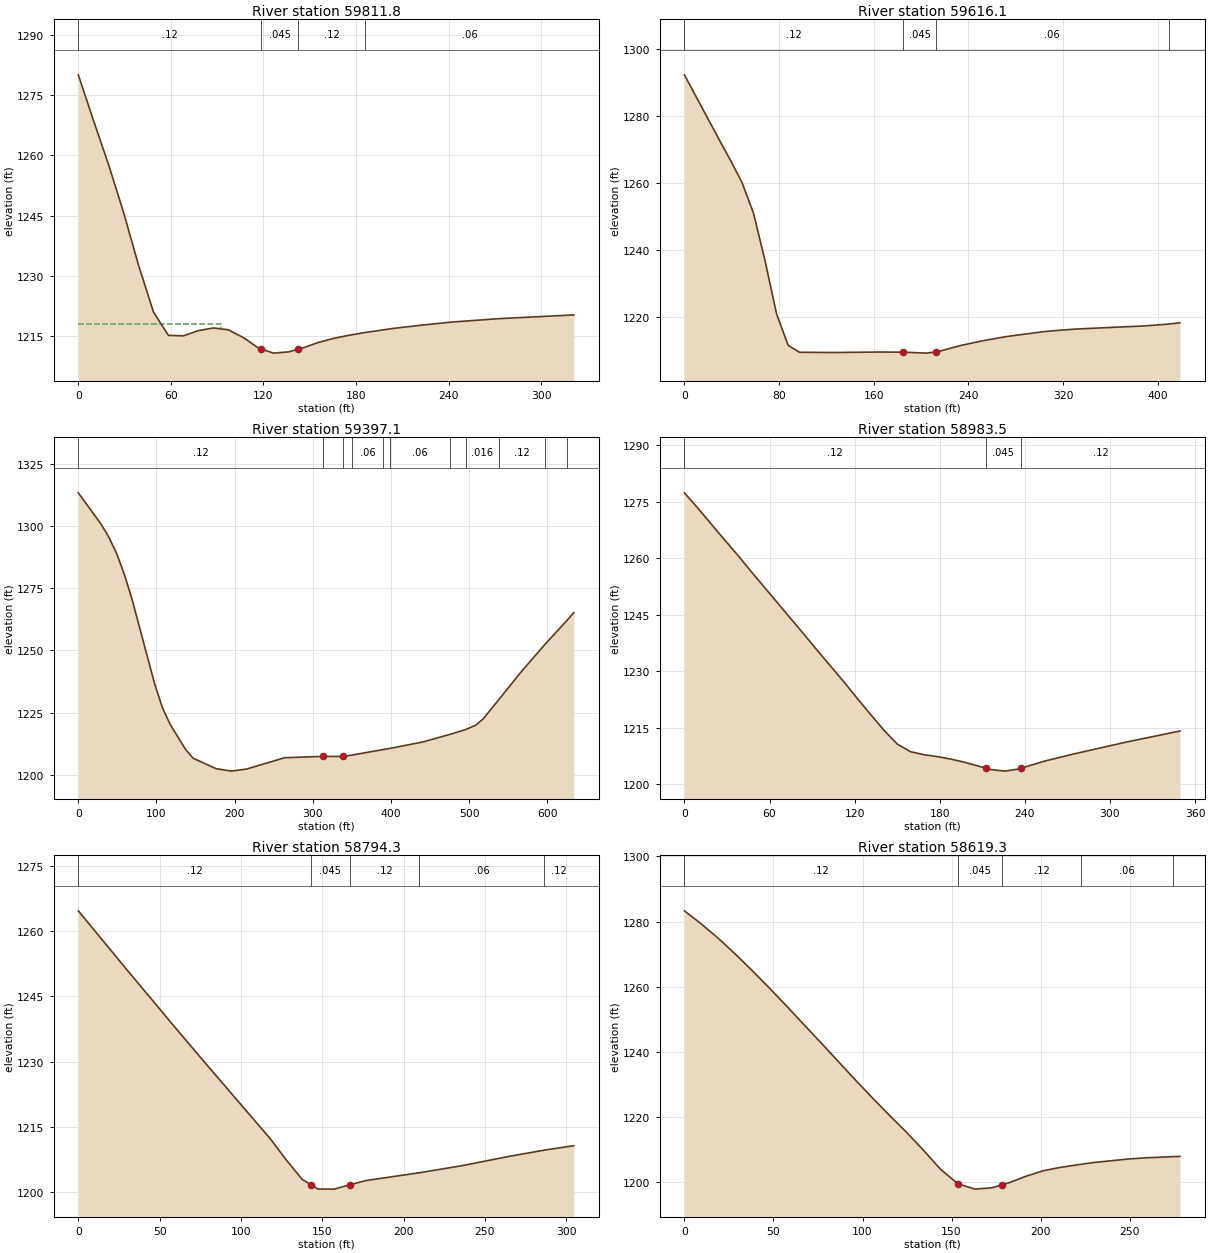
Type RM Length L Ch R = 1 ,59811.8 ,196.6,195.7,194.6
XS GIS Cut Line= 2
     1799625.851      225027.283     1799947.032      225030.755
#Sta/Elev= 27
       0 1279.99     9.7  1268.8    19.5 1257.78    29.2 1245.96    38.9 1232.82
    48.7 1221.01    58.4  1215.2    68.1 1215.08    77.9 1216.38    87.6 1217.04
    97.3 1216.57   107.1 1214.62   116.8 1212.05   118.3 1211.85   126.5 1210.78
   136.3 1211.09  142.481211.753     146 1212.13   155.7 1213.44   165.5 1214.45
   175.2  1215.2  185.781215.903   204.4 1216.94   223.9  1217.8   243.3 1218.54
   272.5 1219.35   321.2 1220.28
#Mann= 4 ,-1 , 0
       0     .12       0   118.3    .045       0  142.48     .12       0
  185.78     .06       0
#XS Ineff= 2 , 0
           92.47 1217.92
Permanent Ineff=
       F       F
Bank Sta=118.3,142.48
XS Rating Curve= 0 ,0
Exp/Cntr=0.3,0.1

Type RM Length L Ch R = 1 ,59616.1 ,218.5,219,217.6
XS GIS Cut Line= 2
     1799584.184      225225.199     1800002.587      225204.366
#Sta/Elev= 24
       0 1292.24    29.2 1273.04      39 1266.73    48.7 1260.13    58.4    1251
    68.2 1236.76    77.9 1220.98    87.7 1211.57    97.4 1209.51   126.6 1209.44
   165.6 1209.59   185.1 1209.54   204.6 1209.26   212.6 1209.62   214.3  1209.7
   233.8 1211.56   253.3 1213.02   272.8 1214.23     302 1215.58   311.8 1215.93
   331.2 1216.44   389.7 1217.39   409.31217.924   418.9 1218.29
#Mann= 4 ,-1 , 0
       0     .12       0   185.1    .045       0   212.6     .06       0
   409.3     .12       0
Bank Sta=185.1,212.6
XS Rating Curve= 0 ,0
Exp/Cntr=0.3,0.1

Type RM Length L Ch R = 1 ,59397.1 ,391.7,413.6,437.3
XS GIS Cut Line= 3
     1799511.268      225450.894     1799959.184      225404.019
     1800136.268       225452.63
#Sta/Elev= 30
       0 1313.26    29.4 1300.56    39.2 1295.37      49 1288.89    58.7  1280.7
    68.5 1270.77    97.9  1236.3   107.7 1226.89   117.5 1220.28   137.1 1210.26
   146.9 1206.66   176.2 1202.49   195.8 1201.49   215.4 1202.34   264.3 1206.89
   313.3 1207.41     339 1207.38  350.441207.954  389.751210.134  398.51 1210.59
   440.6 1213.18  475.651216.264  495.831218.213   508.4 1219.91     518 1222.47
  537.871230.129   566.3 1241.26  597.651252.587  625.911262.233     634 1265.16
#Mann= 11 ,-1 , 0
       0     .12       0   313.3    .045       0     339     .12       0
  350.44     .06       0  389.75     .12       0  398.51     .06       0
  475.65     .12       0  495.83    .016       0  537.87     .12       0
  597.65     .06       0  625.91     .12       0
Bank Sta=313.3,339
XS Rating Curve= 0 ,0
Exp/Cntr=0.3,0.1

Type RM Length L Ch R = 1 ,58983.5 ,202.9,189.2,175.6
XS GIS Cut Line= 3
     1799497.379      225600.199     1799643.212      225664.435
     1799756.059      225817.213
#Sta/Elev= 26
       0 1277.39     9.4 1273.35    28.1 1264.98    37.5 1260.88    46.9 1256.55
    84.4 1239.76    93.7 1235.51   112.5 1227.15   121.9 1222.76   131.2 1218.53
   140.6 1214.36     150 1210.66   159.4 1208.62   168.8 1207.83   178.4 1207.31
   187.8 1206.66   197.3 1205.83   212.3 1204.27   216.3 1203.87   225.8 1203.46
   235.3    1204   237.31204.234   254.3 1206.16   273.3 1207.92   311.3 1211.16
   349.3 1214.12
#Mann= 3 ,-1 , 0
       0     .12       0   212.3    .045       0   237.3     .12       0
Bank Sta=212.3,237.3
XS Rating Curve= 0 ,0
Exp/Cntr=0.3,0.1

Type RM Length L Ch R = 1 ,58794.3 ,173.9,175,176
XS GIS Cut Line= 2
     1799405.365      225792.908     1799693.559      225891.866
#Sta/Elev= 18
       0 1264.66    29.5 1251.28      59 1238.07    78.6 1229.42     118 1212.26
   127.8  1207.4   137.6 1202.91  142.921201.696   147.4 1200.68   155.7 1200.65
   157.3 1200.65   167.1 1201.67   176.9 1202.62  209.781204.417   235.9 1206.04
   265.4 1208.22  286.65 1209.62   304.7 1210.64
#Mann= 5 ,-1 , 0
       0     .12       0  142.92    .045       0   167.1     .12       0
  209.78     .06       0  286.65     .12       0
Bank Sta=142.92,167.1
XS Rating Curve= 0 ,0
Exp/Cntr=0.3,0.1

Type RM Length L Ch R = 1 ,58619.3 ,178.5,174.8,171.1
XS GIS Cut Line= 2
     1799330.712      225943.949     1799589.393       226046.38
#Sta/Elev= 28
       0  1283.3     9.6 1279.22    19.2 1274.78    28.8 1269.92    38.4 1264.78
      48 1259.45    57.6 1253.95    76.8 1242.75    95.9 1231.47   105.5 1225.94
   115.1 1220.58   124.7 1215.37   134.3 1209.81   143.9 1203.97   153.41199.606
   163.1 1197.92   172.7 1198.32   178.4 1199.25   182.3 1199.89   191.9 1201.89
   201.5 1203.56   211.1  1204.6  222.471205.524   230.2 1206.11   249.4 1207.17
     259 1207.53  274.35 1207.89   278.2 1207.97
#Mann= 5 ,-1 , 0
       0     .12       0   153.4    .045       0   178.4     .12       0
  222.47     .06       0  274.35     .12       0
Bank Sta=153.4,178.4
XS Rating Curve= 0 ,0
Exp/Cntr=0.3,0.1

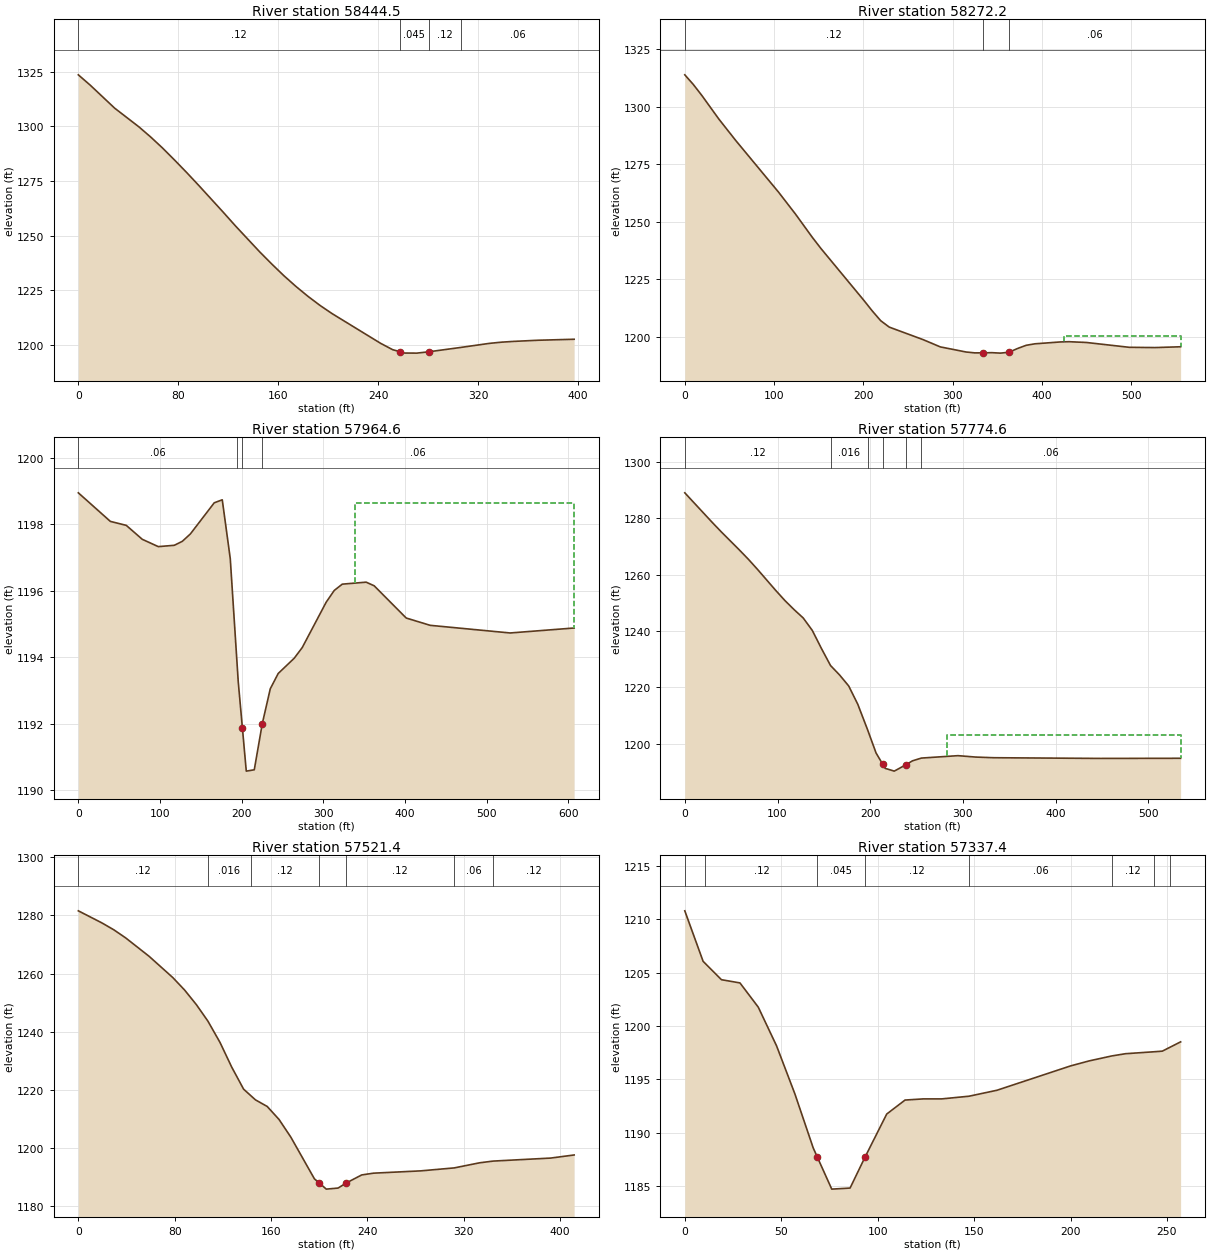
Type RM Length L Ch R = 1 ,58444.5 ,172.8,172.3,172.1
XS GIS Cut Line= 3
     1799198.768      226020.338     1799374.115      226157.491
     1799544.254      226195.685
#Sta/Elev= 30
       0 1323.62     9.7  1318.8      29 1308.41    48.4 1299.86    58.1 1295.08
    67.8 1289.92    77.4 1284.41    87.1  1278.7    96.8 1272.77   116.2 1260.63
   125.8 1254.48   145.2 1242.61   154.9 1237.02   164.5 1231.73   174.2 1226.79
   183.9 1222.23   193.6 1218.05   203.3 1214.29     242 1200.75   251.7 1197.82
  257.331196.932   261.4 1196.29     271 1196.25   280.7 1196.87  306.011198.836
   329.2 1200.72   338.9 1201.27   348.6 1201.62   367.9 1202.14     397  1202.6
#Mann= 4 ,-1 , 0
       0     .12       0  257.33    .045       0   280.7     .12       0
  306.01     .06       0
Bank Sta=257.33,280.7
XS Rating Curve= 0 ,0
Exp/Cntr=0.3,0.1

Type RM Length L Ch R = 1 ,58272.2 ,316.1,307.6,297
XS GIS Cut Line= 3
     1799137.711      226093.376     1799313.493      226319.071
     1799576.079      226377.665
#Sta/Elev= 30
       0 1313.87     9.5  1309.7    19.1  1304.9    38.1 1294.67    57.2 1285.27
   104.9 1262.94     124 1253.34     143 1243.16   152.6 1238.35   200.2 1216.04
   209.8 1211.36   219.3 1207.08   228.9 1204.29     267 1198.82   286.1 1195.69
   314.9 1193.48   324.5  1193.1   334.1 1193.11   343.7 1193.19   353.3 1192.99
   362.9 1193.37   372.6 1195.01   382.2 1196.39   391.8 1197.03   420.6 1197.85
   430.2 1197.95   449.4 1197.62   497.5 1195.52   526.3  1195.4   555.1 1195.75
#Mann= 3 ,-1 , 0
       0     .12       0   334.1    .045       0   362.9     .06       0
#XS Ineff= 2 , 0
                          424.15         1200.34
Permanent Ineff=
       F       F
Bank Sta=334.1,362.9
XS Rating Curve= 0 ,0
Exp/Cntr=0.3,0.1

Type RM Length L Ch R = 1 ,57964.6 ,220.5,190,159.6
XS GIS Cut Line= 2
     1798987.972      226531.744      1799584.76      226421.067
#Sta/Elev= 30
       0 1198.95    39.2 1198.09    58.7 1197.97    78.3 1197.55    97.9 1197.33
   117.5 1197.37   127.3 1197.49   137.1 1197.71   166.4 1198.65   176.2 1198.74
     186 1196.97  193.691194.051   195.8 1193.25   200.9 1191.86   205.6 1190.57
   215.4 1190.61   225.2    1192     235 1193.05   244.7 1193.51   264.3 1193.97
   274.1 1194.29   303.5 1195.66   313.3 1196.01   323.1  1196.2   352.4 1196.26
   362.2 1196.15   401.4 1195.18   430.8 1194.96   528.6 1194.73     607 1194.88
#Mann= 4 ,-1 , 0
       0     .06       0  193.69     .12       0   200.9    .045       0
   225.2     .06       0
#XS Ineff= 2 , 0
                           338.8         1198.65
Permanent Ineff=
       F       F
Bank Sta=200.9,225.2
XS Rating Curve= 0 ,0
Exp/Cntr=0.3,0.1

Type RM Length L Ch R = 1 ,57774.6 ,229.9,253.2,276
XS GIS Cut Line= 3
     1799339.805      226767.476     1799354.725      226473.151
     1799590.457      226427.849
#Sta/Elev= 30
       0 1289.05    29.5 1278.58    39.3 1275.21    58.9 1268.75    68.8 1265.38
    78.6  1261.8    98.2 1254.35   108.1 1250.76   117.9 1247.57   127.7 1244.62
   137.5  1240.2   147.4 1233.76   157.2 1227.72  157.771227.524     167 1224.35
   176.8 1220.46   186.6 1213.95  197.111204.959   206.3 1196.66  213.381192.723
   216.1 1191.21   225.9 1190.22  238.851192.544   245.6 1193.88  255.281194.858
   294.7 1195.71   313.9 1195.21   333.1 1194.98   448.3 1194.73   534.8 1194.78
#Mann= 6 ,-1 , 0
       0     .12       0  157.77    .016       0  197.11     .12       0
  213.38    .045       0  238.85     .12       0  255.28     .06       0
#XS Ineff= 2 , 0
                          282.35         1202.91
Permanent Ineff=
       F       F
Bank Sta=213.38,238.85
XS Rating Curve= 0 ,0
Exp/Cntr=0.3,0.1

Type RM Length L Ch R = 1 ,57521.4 ,177.3,184,190.8
XS GIS Cut Line= 2
     1799382.123        226751.2     1799743.234      226553.066
#Sta/Elev= 30
       0 1281.59    19.6 1277.43    29.4 1275.08    39.2 1272.32    58.8 1265.94
    78.5 1258.62    88.3 1254.33    98.1 1249.29  107.641243.644   117.7 1236.31
   127.5 1227.76   137.3 1220.24  143.071218.079   147.1 1216.57   156.9 1214.28
   166.7 1209.83   176.5 1203.75   196.1  1189.4     200    1188     206 1185.84
   215.8 1186.21  222.631187.966   235.4 1190.72   245.2 1191.33   284.4 1192.12
  312.291193.143   333.4  1194.9   344.61195.489   392.3 1196.52   411.9 1197.59
#Mann= 7 ,-1 , 0
       0     .12       0  107.64    .016       0  143.07     .12       0
     200    .045       0  222.63     .12       0  312.29     .06       0
   344.6     .12       0
Bank Sta=200,222.63
XS Rating Curve= 0 ,0
Exp/Cntr=0.3,0.1

Type RM Length L Ch R = 1 ,57337.4 ,111.1,129.8,148.4
XS GIS Cut Line= 2
     1799547.726      226839.783     1799799.462      226787.699
#Sta/Elev= 27
       0 1210.79     9.5 1206.06    10.71205.843      19 1204.34    28.6 1204.04
    38.1 1201.77    47.6 1198.14    57.1 1193.64    66.6 1188.58   68.74 1187.72
    76.2 1184.73    85.7 1184.83   93.361187.692   104.7 1191.76   114.2 1193.07
   123.8 1193.18   133.3 1193.18  147.441193.432   161.9 1193.99   199.9 1196.26
   209.5 1196.73  221.411197.201   228.5 1197.41  243.061197.589   247.6 1197.65
  251.471198.004   257.1 1198.52
#Mann= 8 ,-1 , 0
       0    .016       0    10.7     .12       0   68.74    .045       0
   93.36     .12       0  147.44     .06       0  221.41     .12       0
  243.06     .06       0  251.47    .016       0
Bank Sta=68.74,93.36
XS Rating Curve= 0 ,0
Exp/Cntr=0.3,0.1

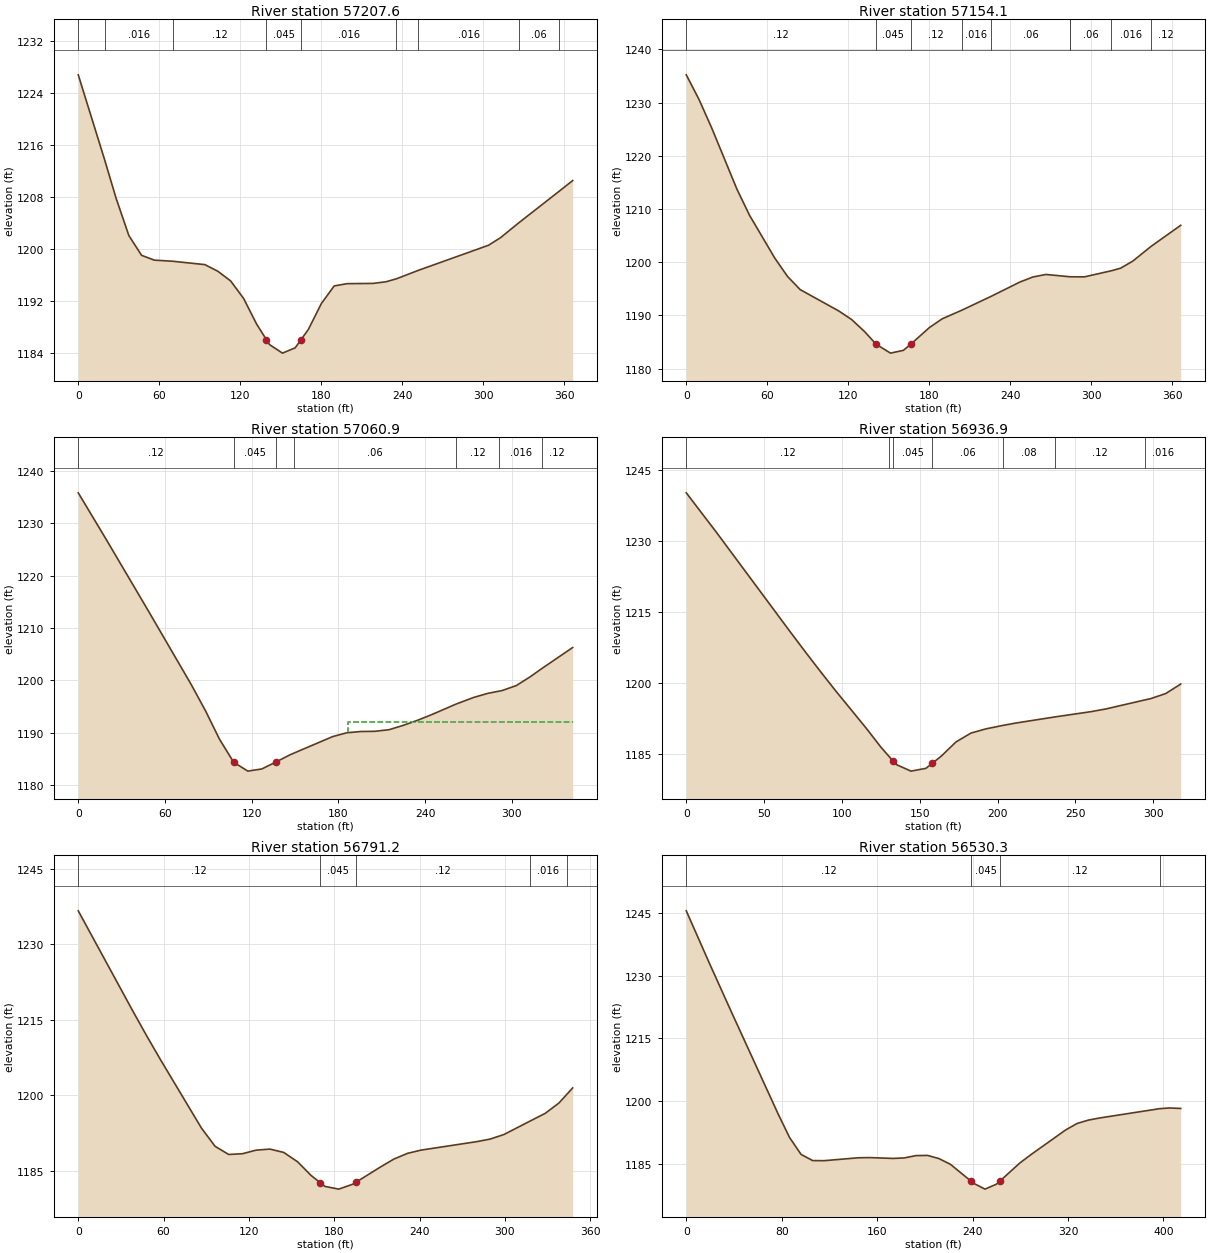
Type RM Length L Ch R = 1 ,57207.6 ,55.4,53.5,51.5
XS GIS Cut Line= 4
     1799526.893      226912.699     1799620.643      226914.435
      1799795.99      227013.394     1799867.171      227013.394
#Sta/Elev= 30
       0 1226.75   19.481213.727    28.1 1207.73    37.5 1202.03    46.9    1199
    56.3 1198.26   70.031198.085    93.8 1197.57   103.4 1196.55   112.9 1195.06
   122.5 1192.37   132.1 1188.44  139.391186.033   141.7 1185.27   151.3 1183.96
   160.7 1184.77  164.961186.005   170.5 1187.61   180.1 1191.58   189.6 1194.29
   199.2 1194.64   218.4 1194.68     228 1194.93  235.74 1195.39  252.011196.691
     304 1200.55   312.9 1201.72  326.371203.995  355.911208.787   366.3 1210.49
#Mann= 9 ,-1 , 0
       0     .12       0   19.48    .016       0   70.03     .12       0
  139.39    .045       0  164.96    .016       0  235.74     .08       0
  252.01    .016       0  326.37     .06       0  355.91     .08       0
Bank Sta=139.39,164.96
XS Rating Curve= 0 ,0
Exp/Cntr=0.3,0.1

Type RM Length L Ch R = 1 ,57154.1 ,102.5,93.1,83.8
XS GIS Cut Line= 4
     1799509.532       226961.31     1799603.282      226963.046
     1799778.629      227062.005     1799849.809      227062.005
#Sta/Elev= 30
       0 1235.22     9.4 1230.61    18.8 1225.26    37.5 1213.74    46.9  1208.8
    65.6 1200.76      75 1197.32    84.4 1194.84   112.9 1190.84   122.5 1189.22
   132.1 1186.95  140.661184.569   151.3  1182.9   160.9 1183.43   166.21184.551
   180.1  1187.7   189.6 1189.35  203.941190.949  225.881193.576   247.2 1196.27
   256.8 1197.21   266.4 1197.69  283.921197.262  284.271197.249   295.1 1197.24
  314.991198.388   321.8 1198.87   330.7 1200.18  344.541203.002   366.3 1206.93
#Mann= 9 ,-1 , 0
       0     .12       0  140.66    .045       0   166.2     .12       0
  203.94    .016       0  225.88     .06       0  283.92    .016       0
  284.27     .06       0  314.99    .016       0  344.54     .12       0
Bank Sta=140.66,166.2
XS Rating Curve= 0 ,0
Exp/Cntr=0.3,0.1

Type RM Length L Ch R = 1 ,57060.9 ,126.5,124.1,121.6
XS GIS Cut Line= 2
     1799509.532      227067.213     1799849.809      227101.935
#Sta/Elev= 29
       0 1235.87    19.6 1226.83    48.9 1213.08    78.2 1199.15      88 1194.17
    97.7 1188.72   107.5 1184.31   117.3 1182.61     127 1183.03   136.8 1184.36
   146.6 1185.75  149.361186.077   175.9 1189.21   185.7 1189.95   195.4 1190.19
   205.2 1190.23     215 1190.54   224.8 1191.37   234.5 1192.32   244.3  1193.4
  261.32 1195.44   273.6 1196.72   283.4  1197.5  291.061197.914   293.2 1198.03
     303 1198.98   312.7 1200.68  320.811202.269     342 1206.27
#Mann= 7 ,-1 , 0
       0     .12       0   107.5    .045       0   136.8     .12       0
  149.36     .06       0  261.32     .12       0  291.06    .016       0
  320.81     .12       0
#XS Ineff= 2 , 0
                          186.74         1192.06
Permanent Ineff=
       F       F
Bank Sta=107.5,136.8
XS Rating Curve= 0 ,0
Exp/Cntr=0.3,0.1

Type RM Length L Ch R = 1 ,56936.9 ,152.3,145.7,139.1
XS GIS Cut Line= 2
     1799509.532      227199.158      1799827.24      227197.421
#Sta/Elev= 27
       0 1240.09    19.3 1231.78    67.4 1210.46      77 1206.28    86.6 1202.18
    96.3 1198.14   115.5 1190.42   125.2 1186.31  130.431184.349     1331183.385
   134.8 1182.71   144.4  1181.3     154 1181.89     1581182.933   163.7 1184.42
   173.3 1187.46   182.9 1189.33   192.6 1190.23  203.481190.957   211.8 1191.46
  236.771192.743     260 1193.86   269.6 1194.43  294.531196.325   298.5 1196.62
   308.1 1197.69   317.7 1199.69
#Mann= 7 ,-1 , 0
       0     .12       0  130.43     .06       0     133    .045       0
     158     .06       0  203.48     .08       0  236.77     .12       0
  294.53    .016       0
Bank Sta=133,158
XS Rating Curve= 0 ,0
Exp/Cntr=0.3,0.1

Type RM Length L Ch R = 1 ,56791.2 ,237.9,260.9,283.5
XS GIS Cut Line= 3
     1799506.059       227336.31     1799618.907      227360.616
     1799841.129      227292.908
#Sta/Elev= 30
       0 1236.63    38.5 1216.66    48.1 1211.81    57.7 1207.13    86.6  1193.5
    96.2 1189.87   105.8 1188.24   115.4 1188.39   125.1  1189.1   134.8 1189.31
   144.5 1188.65   154.2  1186.8   163.8 1184.06  170.051182.668   173.5  1181.9
   183.2 1181.36   192.9 1182.32  195.311182.727   212.2  1185.7   221.9 1187.32
   231.6 1188.47   241.3 1189.12     280 1190.78   289.7  1191.3   299.4 1192.21
  317.591194.855   328.4 1196.41   338.1 1198.48  343.561200.175   347.7 1201.46
#Mann= 5 ,-1 , 0
       0     .12       0  170.05    .045       0  195.31     .12       0
  317.59    .016       0  343.56     .12       0
Bank Sta=170.05,195.31
XS Rating Curve= 0 ,0
Exp/Cntr=0.3,0.1

Type RM Length L Ch R = 1 ,56530.3 ,219.5,212.6,205.4
XS GIS Cut Line= 3
     1799474.809      227482.144     1799653.629      227520.338
     1799830.712      227669.644
#Sta/Elev= 30
       0 1245.43    19.2 1233.05    38.5  1220.9      77    1197    86.6 1191.38
    96.2 1187.36   105.9 1185.88   115.5 1185.85   144.4 1186.55     154 1186.59
   173.2 1186.39   182.8 1186.51   192.5 1187.06   202.2 1187.11   211.8 1186.36
   221.5 1184.98  238.561181.013   240.8 1180.48   250.4 1179.07   260.1 1180.26
  263.181181.049   279.4 1185.24     289 1187.31     318 1193.17   327.6 1194.72
   337.3 1195.54   346.9 1196.05  396.811198.254   404.8 1198.42   414.5 1198.31
#Mann= 4 ,-1 , 0
       0     .12       0  238.56    .045       0  263.18     .12       0
  396.81    .016       0
Bank Sta=238.56,263.18
XS Rating Curve= 0 ,0
Exp/Cntr=0.3,0.1

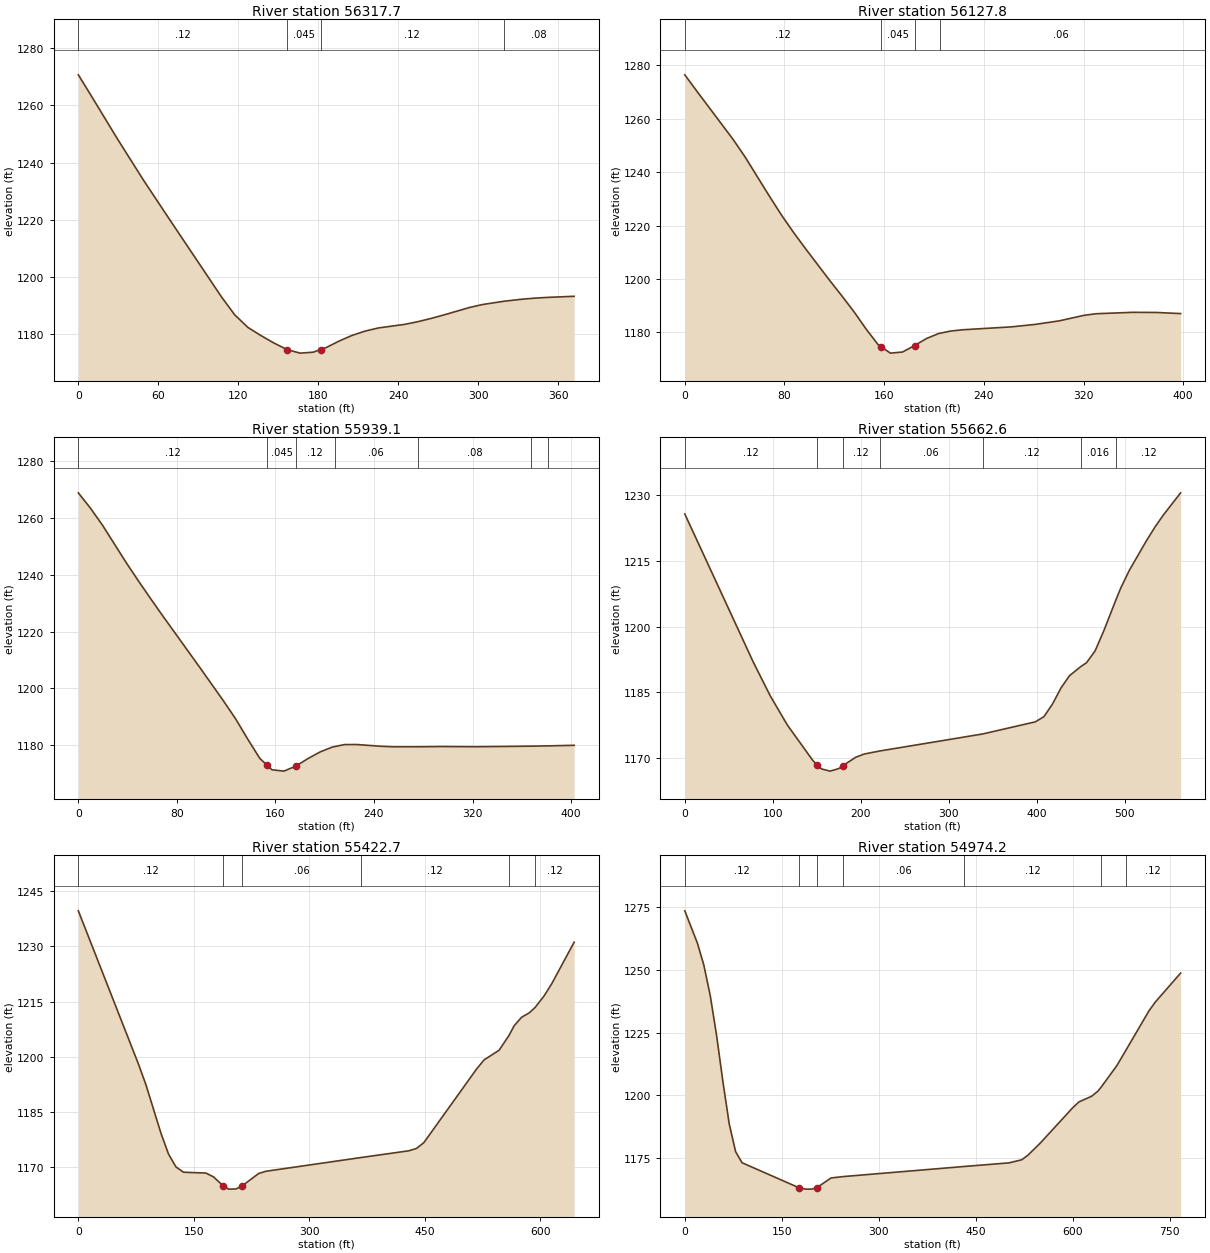
Type RM Length L Ch R = 1 ,56317.7 ,199.7,189.9,180.4
XS GIS Cut Line= 2
     1799407.101      227657.491     1799750.851      227799.852
#Sta/Elev= 30
       0 1270.67     9.8 1263.27    29.4 1248.25      49 1233.81    68.5 1220.14
   107.7 1192.92   117.5 1186.77   127.3 1182.43   137.1 1179.58   146.9 1176.96
   156.81174.667   166.4 1173.46   176.2 1173.78   181.81174.706     186  1175.4
   195.8 1177.69   205.6 1179.68   215.4 1181.18   225.2 1182.25   244.8  1183.5
   254.6 1184.42   264.4 1185.54   274.2 1186.78   293.7 1189.42   303.5 1190.45
  319.421191.583   332.9 1192.29   342.7 1192.67   352.5 1192.94   372.1 1193.31
#Mann= 4 ,-1 , 0
       0     .12       0   156.8    .045       0   181.8     .12       0
  319.42     .08       0
Bank Sta=156.8,181.8
XS Rating Curve= 0 ,0
Exp/Cntr=0.3,0.1

Type RM Length L Ch R = 1 ,56127.8 ,189.6,188.8,187.4
XS GIS Cut Line= 2
     1799365.434      227909.227     1799763.004      227893.602
#Sta/Elev= 30
       0 1276.46     9.7 1270.32    38.8 1252.25    48.5 1245.62    67.9 1231.01
    77.6 1223.94    87.3 1217.41      97 1211.28   116.4 1199.39   126.2 1193.58
   135.9 1187.65   145.6  1181.2   155.3  1175.3   157.6 1174.57     165 1172.23
   174.7 1172.64   184.4 1175.07   194.1 1177.73   203.8 1179.58  205.05  1179.7
   213.5 1180.51   223.2 1180.98     262 1182.06   281.4    1183   300.8 1184.34
   320.2 1186.37     330 1186.98   359.1 1187.51   378.5 1187.46   397.9 1187.04
#Mann= 4 ,-1 , 0
       0     .12       0   157.6    .045       0   184.4     .12       0
  205.05     .06       0
Bank Sta=157.6,184.4
XS Rating Curve= 0 ,0
Exp/Cntr=0.3,0.1

Type RM Length L Ch R = 1 ,55939.1 ,275.9,276.5,277.4
XS GIS Cut Line= 2
     1799414.046      228100.199     1799815.087      228065.477
#Sta/Elev= 30
       0 1268.84     9.8 1263.46    19.6 1257.45    39.3 1243.98    49.1 1237.63
    58.9 1231.48    68.7 1225.43    98.2 1207.63   117.8 1195.62   127.6 1189.35
   137.4 1182.24   147.3 1175.39   153.2 1172.98   157.1 1171.38   166.9 1170.89
   176.7 1172.68   186.5 1175.33   196.4 1177.67   206.2 1179.36  208.071179.526
     216 1180.23   225.8 1180.26   245.4 1179.64   255.3 1179.46  275.361179.463
   294.5 1179.54     324 1179.48  367.741179.676  381.071179.777   402.5 1179.98
#Mann= 7 ,-1 , 0
       0     .12       0   153.2    .045       0   176.7     .12       0
  208.07     .06       0  275.36     .08       0  367.74     .06       0
  381.07     .12       0
Bank Sta=153.2,176.7
XS Rating Curve= 0 ,0
Exp/Cntr=0.3,0.1

Type RM Length L Ch R = 1 ,55662.6 ,239,239.9,240.5
XS GIS Cut Line= 2
     1799457.448       228367.56     1800019.948      228338.046
#Sta/Elev= 30
       0 1225.73    77.7 1191.92    97.1 1184.16   116.5  1177.5   145.7 1169.33
   150.41168.423   155.4 1167.46   165.1 1166.96   174.8 1167.53   179.81168.231
   194.2 1170.13   203.9 1170.87  221.231171.556  338.271175.446   398.2 1178.22
   407.9 1179.39   417.6 1182.24   427.3 1185.93     437 1188.76  449.611190.809
   456.4 1191.74   466.2 1194.46   475.9 1198.97  490.171206.293   495.3 1208.81
     505 1212.84   524.4 1219.59   534.1 1222.72   543.8 1225.52   563.3 1230.56
#Mann= 7 ,-1 , 0
       0     .12       0   150.4    .045       0   179.8     .12       0
  221.23     .06       0  338.27     .12       0  449.61    .016       0
  490.17     .12       0
Bank Sta=150.4,179.8
XS Rating Curve= 0 ,0
Exp/Cntr=0.3,0.1

Type RM Length L Ch R = 1 ,55422.7 ,457.3,448.6,439.8
XS GIS Cut Line= 2
      1799420.99      228601.935     1800064.698      228589.957
#Sta/Elev= 30
       0 1239.68      78 1198.04    87.8 1192.36   107.3 1179.18   117.1 1173.53
   126.8 1170.02   136.6 1168.59   165.8 1168.36   175.6 1167.31  188.331164.837
   195.1 1163.99   204.8 1164.04  212.911164.892   234.1 1168.24   243.9 1168.86
  366.911172.576   429.2 1174.42     439 1175.04   448.7 1176.65     517 1196.63
   526.8 1199.13   546.3 1201.76  559.281205.815   565.8 1208.39   575.5 1210.73
   585.3  1211.9   592.91213.357   604.8 1216.55   614.6 1219.82   643.8 1231.16
#Mann= 6 ,-1 , 0
       0     .12       0  188.33    .045       0  212.91     .06       0
  366.91     .12       0  559.28    .016       0   592.9     .12       0
Bank Sta=188.33,212.91
XS Rating Curve= 0 ,0
Exp/Cntr=0.3,0.1

Type RM Length L Ch R = 1 ,54974.2 ,330,348.2,366.5
XS GIS Cut Line= 2
     1799465.739       229048.29     1800170.601      228746.207
#Sta/Elev= 30
       0 1273.63    19.7 1260.61    29.5 1251.92    39.3 1239.93    49.2 1223.87
      59 1205.39    68.8 1188.54    78.6  1177.6    88.5 1173.16     177 1163.14
   186.8 1162.63   196.6 1162.64  204.021163.178   226.1 1167.07  244.871167.631
  431.431171.646   501.4  1173.1   521.1 1174.33   530.9  1176.2   550.6 1181.21
   599.7    1195   609.6 1197.42   629.2 1199.67   639.1 1201.74   644.21203.374
   668.6 1212.02  682.161217.979   717.7 1233.63   727.5 1237.18   766.9  1248.8
#Mann= 7 ,-1 , 0
       0     .12       0     177    .045       0  204.02     .12       0
  244.87     .06       0  431.43     .12       0   644.2    .016       0
  682.16     .12       0
Bank Sta=177,204.02
XS Rating Curve= 0 ,0
Exp/Cntr=0.3,0.1