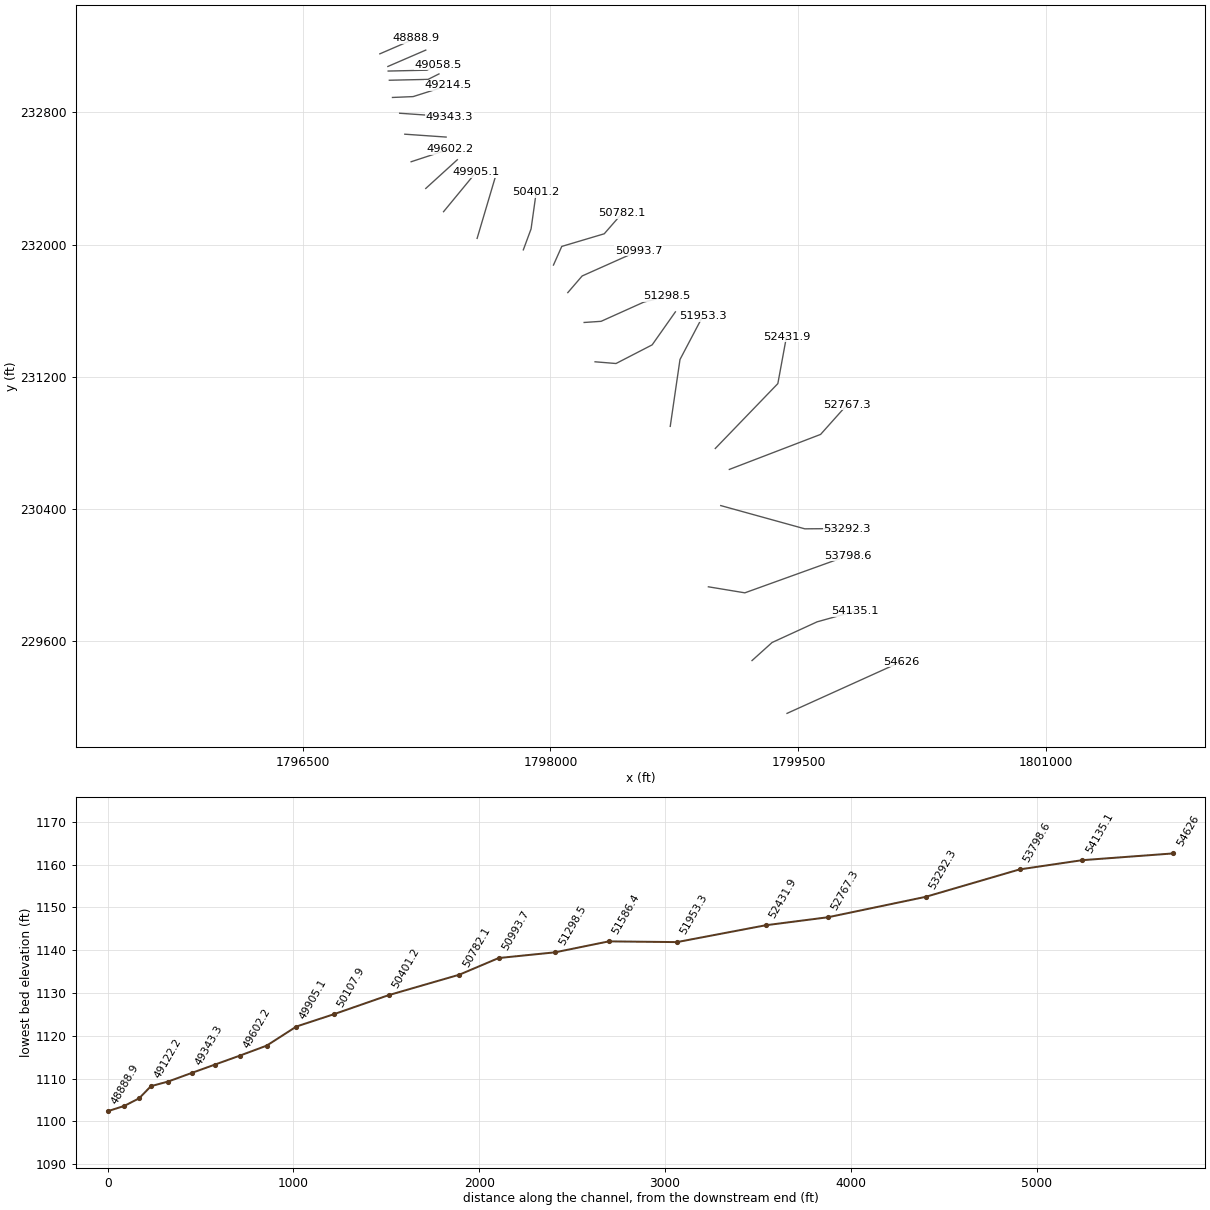
HEC-RAS study ELKCK.prj: ELKCK

--- ELKCK.g01 (geometry) --- (continued)

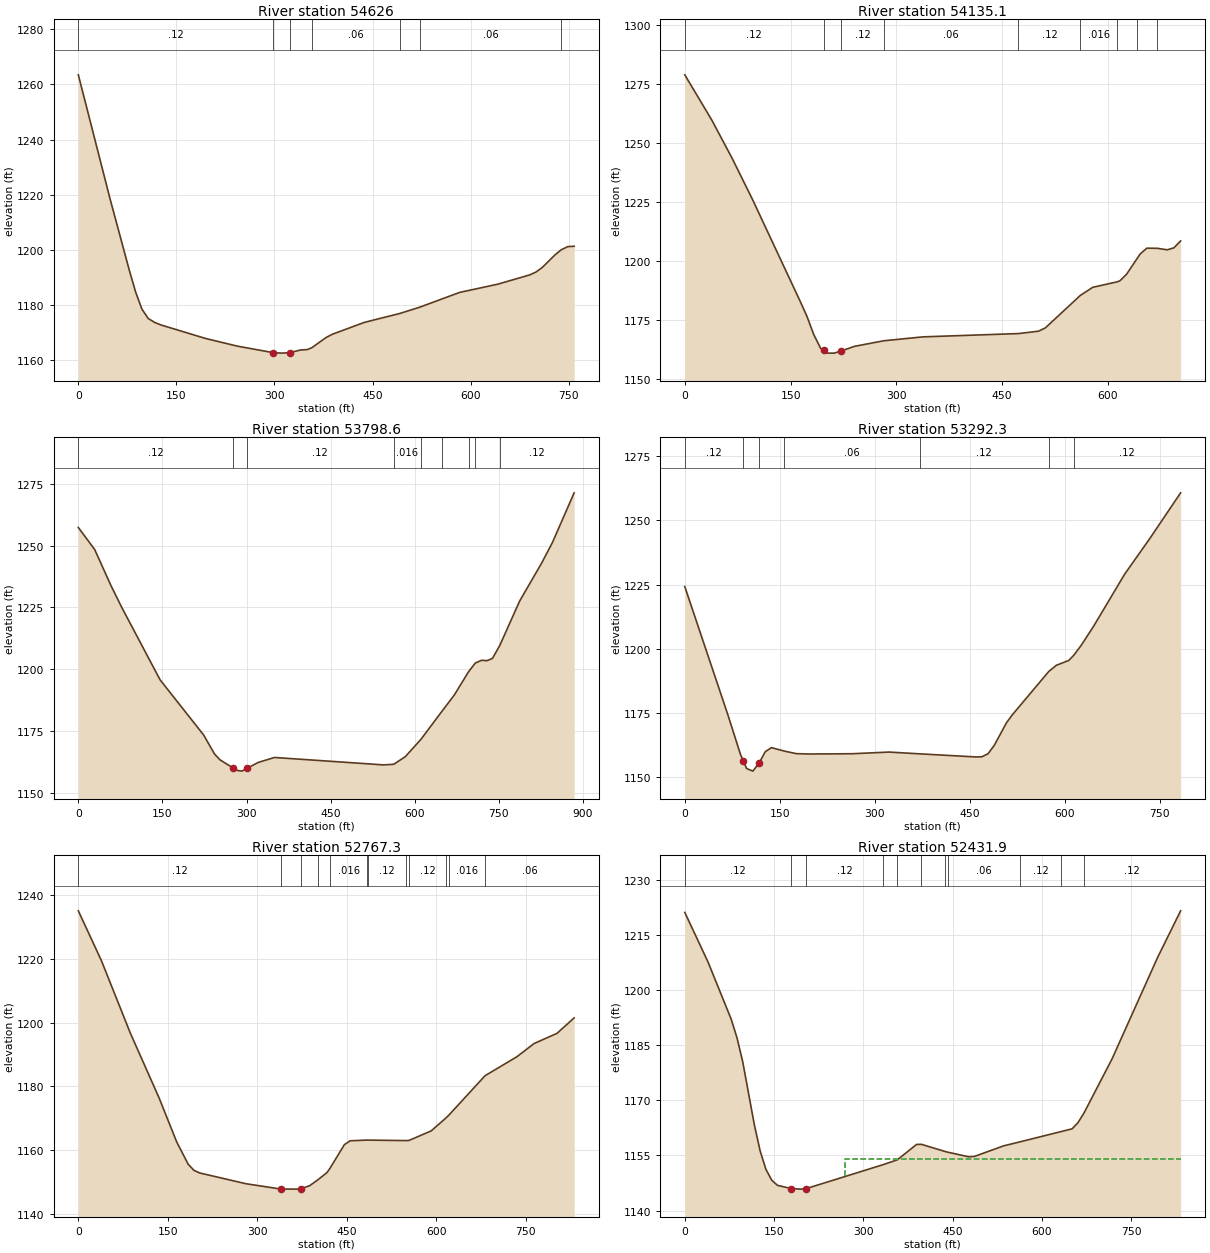
Type RM Length L Ch R = 1 ,54626   ,489.9,490.9,491.8
XS GIS Cut Line= 2
     1799431.407      229164.435     1800122.379      229476.935
#Sta/Elev= 30
       0 1263.44    48.6 1218.43    77.8 1192.79    87.5 1184.83    97.2 1178.57
     107 1175.12   116.7 1173.73   126.4  1172.8   194.4 1167.92   243.1 1165.13
  297.741162.773   311.1 1162.59   323.5 1162.77   340.3 1163.74     350 1163.86
  356.911164.515   379.2 1168.28   388.9 1169.46   437.5 1173.73  491.551176.948
  522.271179.246   583.4  1184.6   641.7 1187.58   690.3 1190.93     700 1191.97
   709.7 1193.65   729.2 1198.21  738.521200.016   748.6 1201.18   758.4 1201.32
#Mann= 7 ,-1 , 0
       0     .12       0  297.74    .045       0   323.5     .12       0
  356.91     .06       0  491.55     .12       0  522.27     .06       0
  738.52    .016       0
Bank Sta=297.74,323.5
XS Rating Curve= 0 ,0
Exp/Cntr=0.3,0.1

Type RM Length L Ch R = 1 ,54135.1 ,338.4,336.5,334.5
XS GIS Cut Line= 4
     1799219.601       229483.88     1799341.129      229593.255
     1799613.698      229718.255     1799844.601      229782.491
#Sta/Elev= 30
       0 1278.79    38.5 1259.53    67.3 1243.35    96.2 1225.92   163.5    1183
   173.2 1176.58   182.8 1168.91   192.5 1163.09     197 1162.13   202.2 1161.02
   211.9 1161.01   221.5 1161.92   240.9  1163.9  282.061166.235   337.6 1167.89
  473.121169.283   501.7  1170.3   511.3 1171.71   560.81185.435   578.4 1188.86
     6131191.182   616.8 1191.59   626.3 1194.37  640.441200.669   645.5 1202.93
   655.1 1205.43  670.161205.367   683.9 1204.73   693.4 1205.56     703 1208.48
#Mann= 9 ,-1 , 0
       0     .12       0     197    .045       0   221.5     .12       0
  282.06     .06       0  473.12     .12       0   560.8    .016       0
     613     .08       0  640.44     .12       0  670.16    .016       0
Bank Sta=197,221.5
XS Rating Curve= 0 ,0
Exp/Cntr=0.3,0.1

Type RM Length L Ch R = 1 ,53798.6 ,520.2,506.3,492.4
XS GIS Cut Line= 3
     1798955.712       229930.06     1799176.198      229893.602
     1799797.726       230117.56
#Sta/Elev= 30
       0 1257.35    29.2 1248.42    58.3 1233.81    77.7 1224.92   145.8 1195.76
   223.5 1173.45   242.9 1165.76   252.6 1163.42   275.61160.191   281.8 1159.23
   291.5 1158.86   300.61159.957   320.6 1162.36   349.8 1164.38   544.1 1161.38
  562.31 1161.62     583  1164.7  610.951171.729   647.61182.816   670.4 1189.63
  695.791199.017  707.771202.537     719 1203.66   728.7 1203.51   738.4  1204.4
  751.591209.708     787 1227.65   825.8 1242.81   845.3 1251.24   884.1 1271.35
#Mann= 9 ,-1 , 0
       0     .12       0   275.6    .045       0   300.6     .12       0
  562.31    .016       0  610.95     .12       0   647.6    .016       0
  695.79     .12       0  707.77    .016       0  751.59     .12       0
Bank Sta=275.6,300.6
XS Rating Curve= 0 ,0
Exp/Cntr=0.3,0.1

Type RM Length L Ch R = 1 ,53292.3 ,510.4,524.9,539.5
XS GIS Cut Line= 3
     1799030.365       230421.38     1799539.046      230280.755
     1799794.254      230282.491
#Sta/Elev= 30
       0  1224.2    68.4 1174.08      88 1158.88    92.41156.413    97.7 1153.44
   107.5 1152.45   117.41155.615     127 1159.98   136.8 1161.59  157.341160.233
   175.9 1159.25   195.5 1159.11   263.9 1159.21   322.5 1159.86  371.071159.167
   459.4 1157.97   469.1 1158.02   478.9 1159.22   488.7 1162.47   508.2 1171.34
     518 1174.57  574.781191.197   586.7  1193.6   606.3 1195.48  614.161197.469
   625.9 1201.32   645.6 1208.79   694.6 1229.02   733.9 1242.73     783 1260.66
#Mann= 7 ,-1 , 0
       0     .12       0    92.4    .045       0   117.4     .12       0
  157.34     .06       0  371.07     .12       0  574.78    .016       0
  614.16     .12       0
Bank Sta=92.4,117.4
XS Rating Curve= 0 ,0
Exp/Cntr=0.3,0.1

Type RM Length L Ch R = 1 ,52767.3 ,326.4,335.4,344.6
XS GIS Cut Line= 3
     1799082.448       230640.13     1799634.532      230851.935
     1799794.254      231030.755
#Sta/Elev= 30
       0 1235.08    38.8 1219.39    87.2 1196.67   135.7 1176.19   164.8 1162.54
   184.2 1155.49   193.9 1153.57   203.6 1152.76   281.1 1149.38   339.3 1147.72
   368.2 1147.69  373.091147.794   387.8 1148.78  401.541150.615   416.8 1152.89
  421.91 1154.26   445.9 1161.64   455.6 1162.87  484.041163.091   485.61163.083
  549.97 1162.93   554.31162.984   591.3 1165.96  616.561170.087  622.04 1171.12
  681.761183.304   735.2 1189.27     764 1193.42   802.3  1196.6   831.1 1201.46
#Mann= 12 ,-1 , 0
       0     .12       0   339.3    .045       0  373.09     .12       0
  401.54     .08       0  421.91    .016       0  484.04     .06       0
   485.6     .12       0  549.97     .06       0   554.3     .12       0
  616.56     .06       0  622.04    .016       0  681.76     .06       0
Bank Sta=339.3,373.09
XS Rating Curve= 0 ,0
Exp/Cntr=0.3,0.1

Type RM Length L Ch R = 1 ,52431.9 ,463.6,478.6,492.8
XS GIS Cut Line= 3
     1798997.379      230766.866     1799375.851      231159.227
     1799427.934      231442.213
#Sta/Elev= 30
       0 1221.08    38.9 1207.63    77.9 1192.06    87.6 1187.03    97.4 1180.39
   116.8 1163.36   126.6 1156.19   136.3  1151.2     146 1148.25   155.8 1146.84
   179.21145.962   194.7 1145.82   204.21145.977  332.651152.447  356.991153.788
   389.4 1157.98  397.381158.005  437.781156.032  441.641155.874     477 1154.61
   486.7 1154.72   535.4 1157.58  562.911158.673  632.171161.473   650.6 1162.22
   660.2 1163.83  670.521166.502   717.8 1181.27   794.5 1208.92   832.9 1221.51
#Mann= 11 ,-1 , 0
       0     .12       0   179.2    .045       0   204.2     .12       0
  332.65     .06       0  356.99     .08       0  397.38    .016       0
  437.78     .08       0  441.64     .06       0  562.91     .12       0
  632.17    .016       0  670.52     .12       0
#XS Ineff= 2 , 0
                          269.35         1154.02
Permanent Ineff=
       F       F
Bank Sta=179.2,204.2
XS Rating Curve= 0 ,0
Exp/Cntr=0.3,0.1

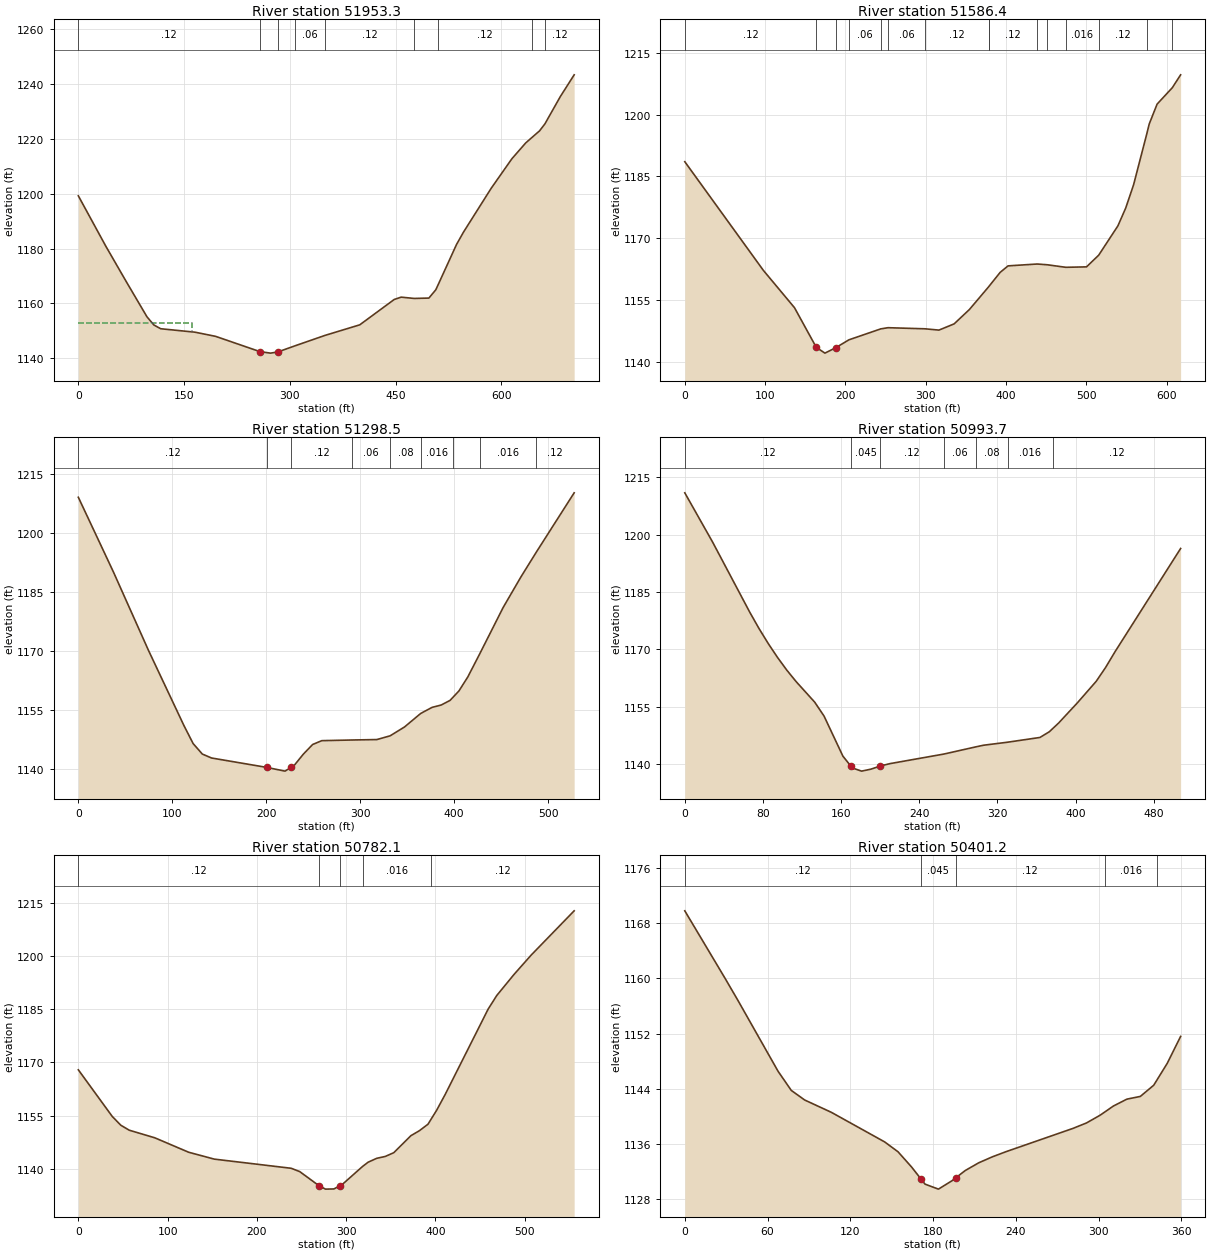
Type RM Length L Ch R = 1 ,51953.3 ,388.5,367,345.4
XS GIS Cut Line= 3
     1798724.809      230900.546     1798783.837       231305.06
      1798920.99      231565.477
#Sta/Elev= 30
       0 1199.29    38.9 1180.94    68.1 1167.92    97.3 1155.15   107.1 1152.16
   116.8 1150.78   165.5 1149.52   194.7    1148   257.61142.424   272.5 1141.88
   282.61142.285  307.751144.592  349.731148.344   399.1 1152.21     448 1161.47
   457.8 1162.31  476.16 1161.84   497.1 1161.97   506.9    1165  510.591167.048
   536.3 1181.53   546.2 1186.05   585.4 1202.02   614.8 1212.82   634.4 1218.59
  642.751220.471   654.1 1223.02  661.681225.565   683.5 1235.52   703.1 1243.45
#Mann= 9 ,-1 , 0
       0     .12       0   257.6    .045       0   282.6     .12       0
  307.75     .06       0  349.73     .12       0  476.16    .016       0
  510.59     .12       0  642.75    .016       0  661.68     .12       0
#XS Ineff= 2 , 0
          161.82 1152.97
Permanent Ineff=
       F       F
Bank Sta=257.6,282.6
XS Rating Curve= 0 ,0
Exp/Cntr=0.3,0.1

Type RM Length L Ch R = 1 ,51586.4 ,289.2,287.9,286.6
XS GIS Cut Line= 4
     1798269.948      231291.171     1798396.684      231280.755
     1798615.434      231393.602     1798756.059      231593.255
#Sta/Elev= 30
       0 1188.54    97.8 1162.16   136.6 1153.09  163.751143.452   174.5 1142.05
   187.91143.351  204.371145.279  244.081147.939  253.121148.225  299.391147.955
   316.5 1147.64   335.4 1149.15   354.4 1152.63  378.391158.154  378.881158.281
   392.8 1161.67   402.6 1163.24  438.851163.691  451.191163.513  474.571162.893
   500.3    1163   515.41165.821   539.4 1172.96   549.1 1177.28   558.9 1182.92
  575.371195.307   578.4  1197.7   588.2 1202.52  607.141206.512   617.5 1209.64
#Mann= 15 ,-1 , 0
       0     .12       0  163.75    .045       0   187.9     .12       0
  204.37     .06       0  244.08     .12       0  253.12     .06       0
  299.39     .12       0  378.39     .08       0  378.88     .12       0
  438.85     .06       0  451.19     .08       0  474.57    .016       0
   515.4     .12       0  575.37    .016       0  607.14     .12       0
Bank Sta=163.75,187.9
XS Rating Curve= 0 ,0
Exp/Cntr=0.3,0.1

Type RM Length L Ch R = 1 ,51298.5 ,304.9,304.8,304.7
XS GIS Cut Line= 4
     1798203.976      231529.019     1798306.407      231535.963
     1798565.087      231652.283      1798702.24      231687.005
#Sta/Elev= 30
       0 1209.16    37.3 1190.19    74.7  1170.2   112.4  1151.1   122.2 1146.51
     132 1143.84   141.8 1142.84   200.5 1140.45     220  1139.5   226.6 1140.48
   229.8 1140.96   239.6 1143.84   249.4 1146.27   259.2 1147.25  291.611147.417
   317.8 1147.53  331.871148.476   347.2 1150.73   364.51154.178   376.5 1155.71
   386.3 1156.32   395.7 1157.49  398.361158.168   405.2 1159.91   414.6 1163.46
  427.061169.229   452.3 1181.16   471.2 1188.92   487.51195.197   527.8 1210.29
#Mann= 9 ,-1 , 0
       0     .12       0   200.5    .045       0   226.6     .12       0
  291.61     .06       0  331.87     .08       0   364.5    .016       0
  398.36     .12       0  427.06    .016       0   487.5     .12       0
Bank Sta=200.5,226.6
XS Rating Curve= 0 ,0
Exp/Cntr=0.3,0.1

Type RM Length L Ch R = 1 ,50993.7 ,214.5,211.6,208.8
XS GIS Cut Line= 3
     1798105.018      231709.574     1798191.823      231810.269
     1798533.837      231963.046
#Sta/Elev= 30
       0 1210.91    28.5 1198.02    66.5  1179.7      76 1175.42    85.5 1171.48
      95 1167.85   104.5 1164.53     114 1161.55     133 1156.18   142.6 1152.52
   161.8 1142.09  169.761139.528   171.4    1139     181 1138.16   190.6 1138.68
   200.2  1139.5   209.8 1140.11  265.171142.621  297.761144.495   305.8 1144.93
  330.361145.719   363.5 1146.96   373.1 1148.45  377.181149.427   382.7 1150.75
   401.9 1156.03   421.1 1161.64   430.7 1165.25   440.3 1169.35   507.5 1196.36
#Mann= 7 ,-1 , 0
       0     .12       0  169.76    .045       0   200.2     .12       0
  265.17     .06       0  297.76     .08       0  330.36    .016       0
  377.18     .12       0
Bank Sta=169.76,200.2
XS Rating Curve= 0 ,0
Exp/Cntr=0.3,0.1

Type RM Length L Ch R = 1 ,50782.1 ,354.9,380.9,406.5
XS GIS Cut Line= 4
     1798018.212      231876.241     1798068.559      231989.088
     1798325.504      232065.477     1798433.143      232188.741
#Sta/Elev= 30
       0 1167.92      38 1154.77    47.5 1152.31      57 1150.89    85.6 1148.75
   123.6 1144.67   152.3 1142.73   238.4 1140.15     248 1139.21  269.241135.286
   276.8 1134.27   286.3 1134.32   292.6 1135.19   295.9 1135.65  318.39 1140.68
   324.6 1141.87   334.2 1142.96   343.8 1143.49   353.3 1144.55   372.5 1149.35
     382 1150.75   391.6 1152.58  394.791153.873   401.2 1156.47   410.9 1160.99
     459 1185.05   468.6 1188.87   487.9  1194.8   507.1 1200.26   555.3 1212.76
#Mann= 5 ,-1 , 0
       0     .12       0  269.24    .045       0   292.6     .08       0
  318.39    .016       0  394.79     .12       0
Bank Sta=269.24,292.6
XS Rating Curve= 0 ,0
Exp/Cntr=0.3,0.1

Type RM Length L Ch R = 1 ,50401.2 ,296.7,293.3,289.8
XS GIS Cut Line= 3
     1797835.921      231968.255     1797882.796      232094.991
     1797914.046      232317.213
#Sta/Elev= 30
       0  1169.8      29 1160.09    38.6  1156.8    67.6 1146.57    77.2 1143.79
    86.9  1142.4   106.2 1140.62   144.9 1136.33   154.6  1134.9   164.4  1132.7
  171.061131.004   174.2 1130.21   183.9 1129.49   193.7  1130.7   196.31131.099
   203.4 1132.19   213.2 1133.31   222.9 1134.16   232.7  1134.9   281.5 1138.29
   291.2 1139.07     301 1140.18   304.41140.648   310.8 1141.53   320.5 1142.52
   330.3 1142.92     340 1144.54  342.051145.203   349.8 1147.71   359.5 1151.61
#Mann= 5 ,-1 , 0
       0     .12       0  171.06    .045       0   196.3     .12       0
   304.4    .016       0  342.05     .12       0
Bank Sta=171.06,196.3
XS Rating Curve= 0 ,0
Exp/Cntr=0.3,0.1

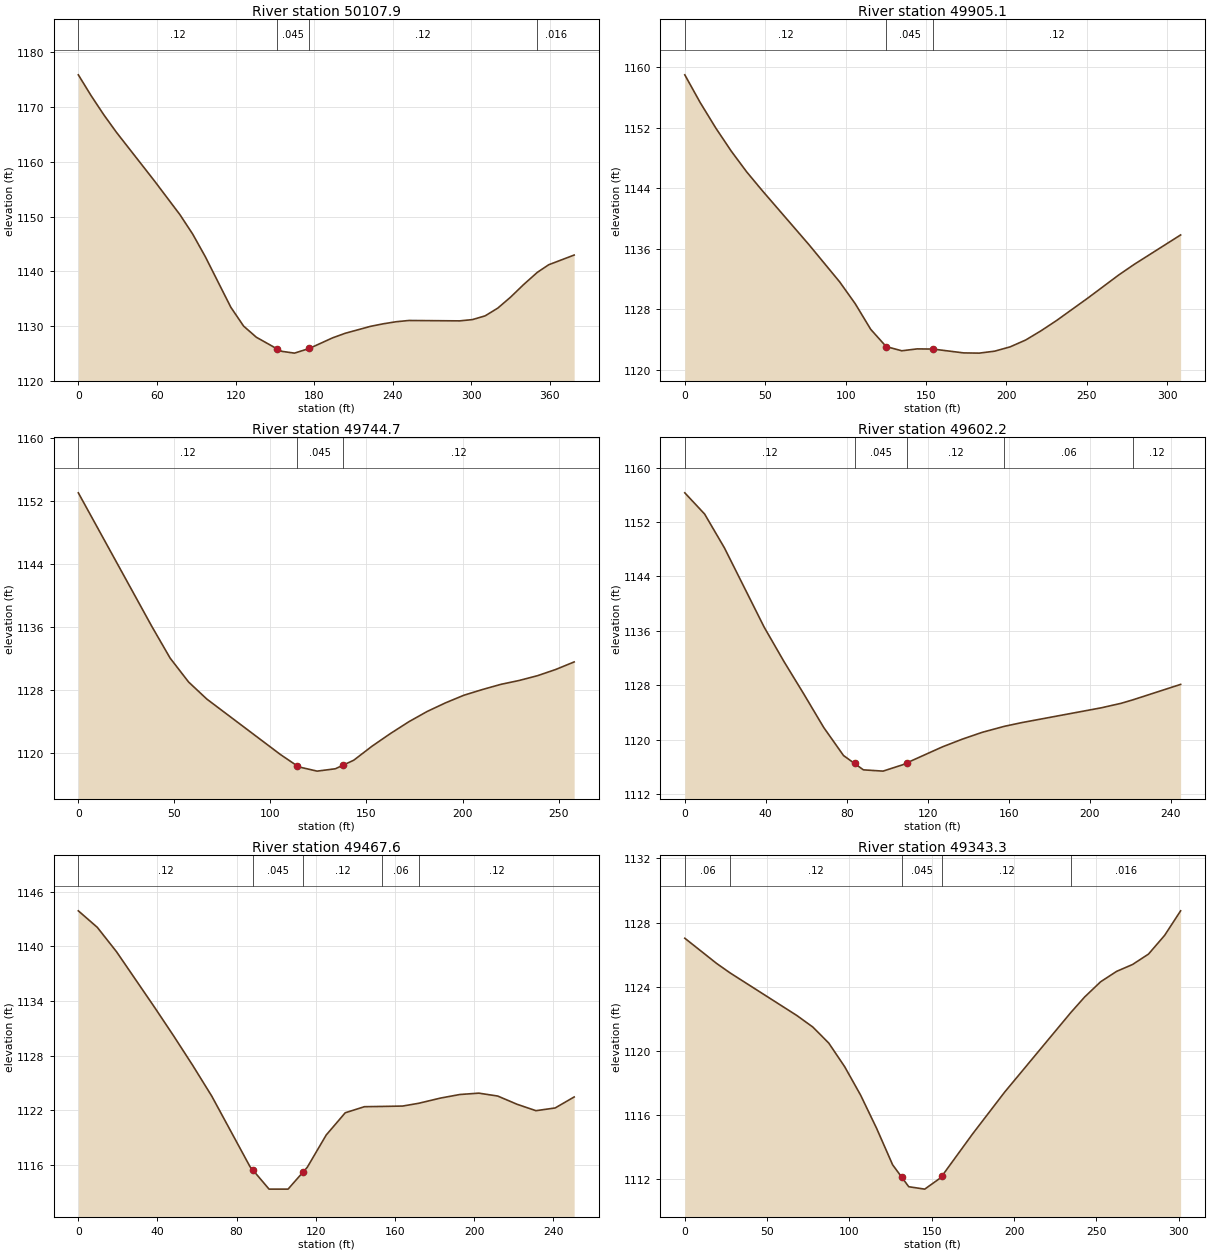
Type RM Length L Ch R = 1 ,50107.9 ,211.7,202.7,193.6
XS GIS Cut Line= 2
     1797556.407      232037.699     1797664.046      232400.546
#Sta/Elev= 30
       0 1175.88     9.7  1172.1    19.4  1168.6    29.1 1165.38    58.2 1156.48
    77.6 1150.33    87.3  1146.8      97 1142.64   116.4 1133.44   126.2 1129.99
   135.9 1127.96   151.4 1125.88   155.3 1125.39     165 1125.06   176.41125.921
   194.1 1127.85   203.8 1128.69   223.2 1129.96   232.9 1130.42   242.6 1130.79
   252.3 1131.02   291.1 1130.95   300.8 1131.18   310.5 1131.86   320.2 1133.28
     330 1135.29   339.7 1137.53  350.34  1139.8   359.1  1141.2   378.5 1142.97
#Mann= 4 ,-1 , 0
       0     .12       0   151.4    .045       0   176.4     .12       0
  350.34    .016       0
Bank Sta=151.4,176.4
XS Rating Curve= 0 ,0
Exp/Cntr=0.3,0.1

Type RM Length L Ch R = 1 ,49905.1 ,163.3,160.4,156.9
XS GIS Cut Line= 2
     1797353.282      232199.158     1797549.462      232437.005
#Sta/Elev= 25
       0    1159     9.6 1155.32    19.3 1151.95    28.9  1148.9    38.5 1146.15
    48.2 1143.67    77.1 1136.55    96.4 1131.57     106  1128.7   115.6 1125.32
   125.2 1123.04   134.9 1122.48   144.5 1122.73   154.2 1122.71   173.4  1122.2
   183.1 1122.17   192.7 1122.43   202.3    1123     212 1123.91   221.6 1125.14
   231.2 1126.49   250.5 1129.44   269.8 1132.51   279.4 1133.91   308.3 1137.81
#Mann= 3 ,-1 , 0
       0     .12       0   125.2    .045       0   154.2     .12       0
Bank Sta=125.2,154.2
XS Rating Curve= 0 ,0
Exp/Cntr=0.3,0.1

Type RM Length L Ch R = 1 ,49744.7 ,152.4,142.5,133.2
XS GIS Cut Line= 2
     1797245.643      232339.783     1797436.615      232513.394
#Sta/Elev= 24
       0 1153.05    38.2 1136.11    47.8 1132.05    57.4 1129.02    66.9 1126.85
   105.2 1119.81  113.721118.402   114.7 1118.24   124.3  1117.7   133.8    1118
  137.751118.448   143.4 1119.09   152.9 1120.87   162.5 1122.48   172.1 1123.98
   181.6 1125.28   191.2 1126.38   200.7 1127.34   210.3 1128.06   219.9 1128.72
   229.4 1129.21     239 1129.82   248.5 1130.61   258.1 1131.57
#Mann= 3 ,-1 , 0
       0     .12       0  113.72    .045       0  137.75     .12       0
Bank Sta=113.72,137.75
XS Rating Curve= 0 ,0
Exp/Cntr=0.3,0.1

Type RM Length L Ch R = 1 ,49602.2 ,143.3,134.6,125.8
XS GIS Cut Line= 2
     1797157.101      232501.241      1797389.74       232577.63
#Sta/Elev= 22
       0 1156.28     9.8 1153.16    19.6 1148.18    39.2 1136.55      49 1131.49
    58.8 1126.72    68.6 1121.82    78.4 1117.69   83.851116.522    88.2 1115.59
    97.9  1115.4   107.7 1116.34   109.71116.618   127.3 1118.97   137.1  1120.1
   146.9  1121.1   157.91121.986   166.5 1122.53   205.7  1124.7   215.5 1125.36
  221.221125.862   244.9 1128.14
#Mann= 5 ,-1 , 0
       0     .12       0   83.85    .045       0   109.7     .12       0
   157.9     .06       0  221.22     .12       0
Bank Sta=83.85,109.7
XS Rating Curve= 0 ,0
Exp/Cntr=0.3,0.1

Type RM Length L Ch R = 1 ,49467.6 ,124.3,124.3,124.3
XS GIS Cut Line= 2
     1797118.907      232667.908     1797368.907      232650.546
#Sta/Elev= 27
       0 1143.92     9.6  1142.1    19.3 1139.42    38.6 1133.28    48.2 1130.15
    57.8 1126.92    67.5 1123.51    86.8 1115.76    88.4 1115.35    96.4  1113.3
     106  1113.3   113.4 1115.13   115.7  1115.7   125.3 1119.26   134.9  1121.7
   144.6 1122.37  153.521122.398   163.9 1122.44     1721122.744   183.1 1123.32
   192.8 1123.71   202.4 1123.86     212 1123.54   221.7 1122.64   231.3 1121.93
     241 1122.23   250.6 1123.44
#Mann= 5 ,-1 , 0
       0     .12       0    88.4    .045       0   113.4     .12       0
  153.52     .06       0     172     .12       0
Bank Sta=88.4,113.4
XS Rating Curve= 0 ,0
Exp/Cntr=0.3,0.1

Type RM Length L Ch R = 1 ,49343.3 ,120.3,128.9,137.4
XS GIS Cut Line= 2
     1797087.657      232794.644     1797388.004       232773.81
#Sta/Elev= 25
       0 1127.02    19.4 1125.44   27.511124.855      68  1122.2    77.7 1121.48
    87.4 1120.48    97.1    1119   106.8 1117.22   116.5 1115.15   126.2 1112.88
  131.661112.116     136 1111.51   145.7 1111.36   155.4 1112.07  156.281112.193
   174.8 1114.81   194.2 1117.41  234.361122.375   242.8 1123.35   252.5  1124.3
   262.2 1124.95   271.9 1125.38   281.6 1126.03   291.4  1127.2   301.1 1128.73
#Mann= 5 ,-1 , 0
       0     .06       0   27.51     .12       0  131.66    .045       0
  156.28     .12       0  234.36    .016       0
Bank Sta=131.66,156.28
XS Rating Curve= 0 ,0
Exp/Cntr=0.3,0.1

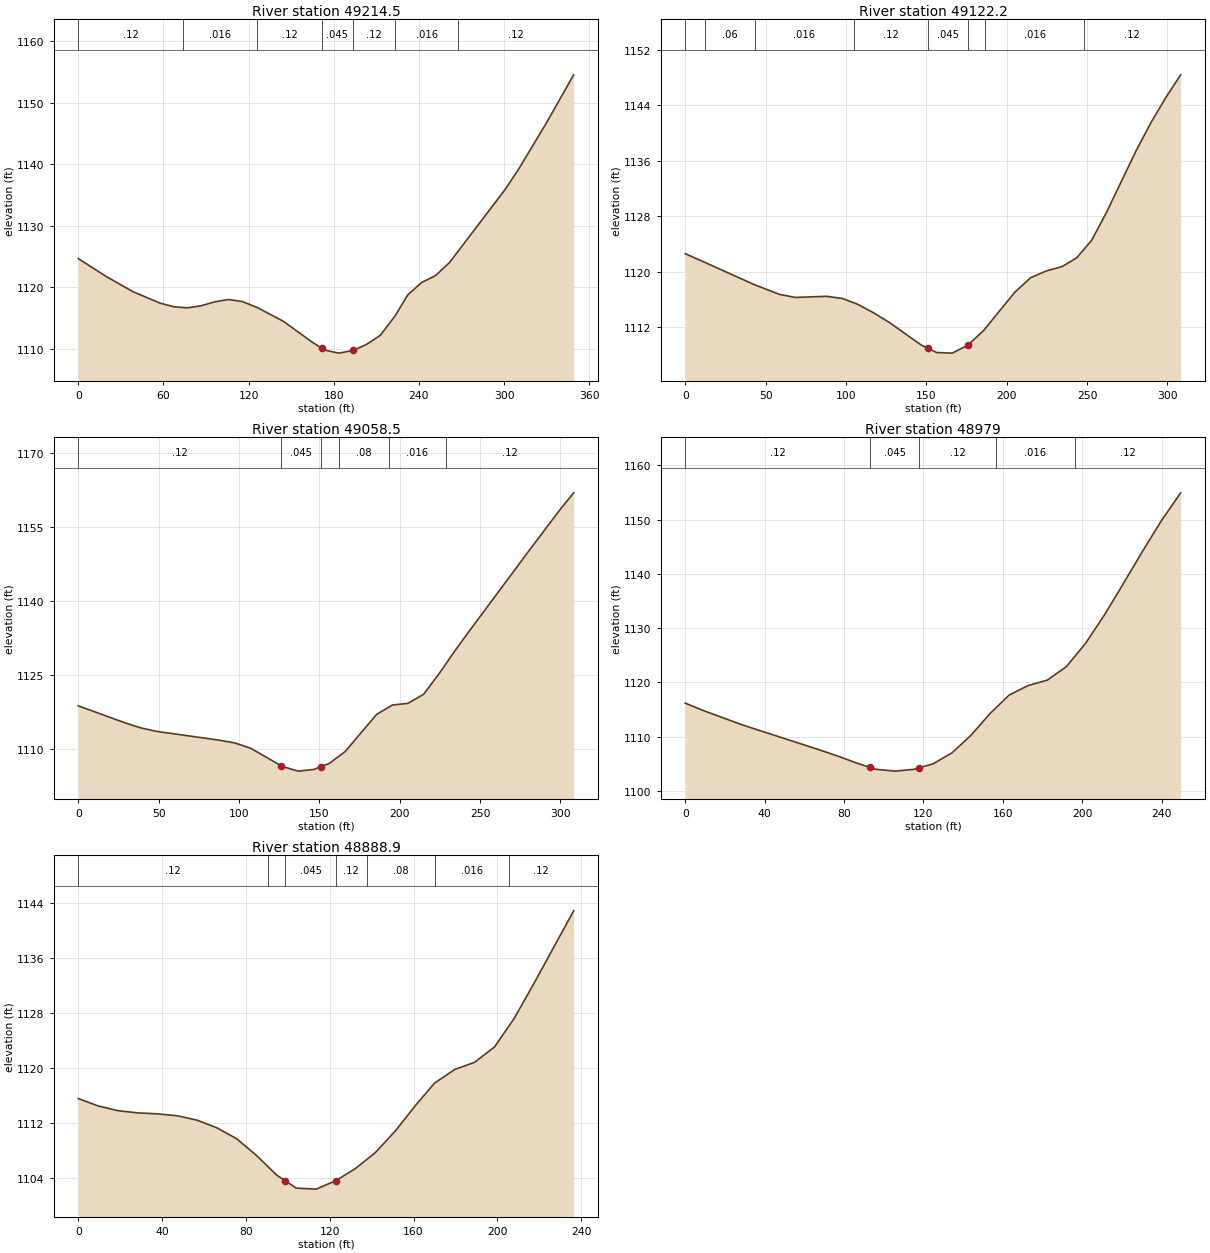
Type RM Length L Ch R = 1 ,49214.5 ,99.3,92.2,85.7
XS GIS Cut Line= 3
     1797044.254       232890.13     1797169.254      232895.338
     1797382.796      232963.046
#Sta/Elev= 30
       0 1124.67    19.2 1121.83    38.5  1119.3    57.7 1117.43    67.4 1116.84
   73.991116.723      77 1116.67    86.6 1117.01    96.2 1117.65   105.9 1118.02
   115.5  1117.7  126.271116.705   144.6 1114.48   164.1 1111.22  171.431110.132
   173.6 1109.81   183.6 1109.32   193.61109.751     203 1110.72   212.8  1112.2
  223.211115.351   232.2 1118.78     242 1120.79   251.7  1121.9   261.5    1124
   267.81125.896   300.4 1135.76   310.2 1139.14   329.6 1146.57   349.1  1154.5
#Mann= 7 ,-1 , 0
       0     .12       0   73.99    .016       0  126.27     .12       0
  171.43    .045       0   193.6     .12       0  223.21    .016       0
   267.8     .12       0
Bank Sta=171.43,193.6
XS Rating Curve= 0 ,0
Exp/Cntr=0.3,0.1

Type RM Length L Ch R = 1 ,49122.2 ,64.6,63.7,62.1
XS GIS Cut Line= 3
     1797025.157      232994.296     1797259.532      232999.505
     1797325.504      233032.491
#Sta/Elev= 30
       0  1122.6    12.41121.327   43.111118.117    58.6 1116.73    68.4 1116.29
    87.9 1116.45    97.7 1116.14   104.81115.518   107.4 1115.29   117.2 1114.06
     127 1112.67   146.5 1109.46   150.91108.959   156.3 1108.34   166.1 1108.25
   175.91109.412   185.6 1111.52  186.681111.821   205.1 1117.06   214.9 1119.14
   224.7 1120.12   234.4 1120.74   243.6 1122.02  247.971123.214   252.9 1124.56
   262.1 1128.58   280.5 1137.47   289.8 1141.55     299 1145.15   308.2 1148.42
#Mann= 8 ,-1 , 0
       0     .12       0    12.4     .06       0   43.11    .016       0
   104.8     .12       0   150.9    .045       0   175.9     .12       0
  186.68    .016       0  247.97     .12       0
Bank Sta=150.9,175.9
XS Rating Curve= 0 ,0
Exp/Cntr=0.3,0.1

Type RM Length L Ch R = 1 ,49058.5 ,69.2,79.5,89.8
XS GIS Cut Line= 3
     1797018.212      233049.852     1797252.587       233055.06
     1797318.559      233088.046
#Sta/Elev= 27
       0 1118.66    29.3 1115.18    39.1 1114.17    48.8 1113.47    87.9 1111.68
    97.7  1111.1   107.4 1110.03   126.21106.492     127 1106.34   136.8 1105.41
   146.5 1105.75   151.21106.349   156.3    1107  162.031108.409   166.1 1109.41
   185.6 1116.92  193.211118.395   195.4 1118.82   205.1 1119.16   214.9 1121.02
   224.7 1125.29  228.741127.193   234.4 1129.86   243.6 1133.98   280.5 1150.17
     299 1158.17   308.2 1161.88
#Mann= 6 ,-1 , 0
       0     .12       0   126.2    .045       0   151.2     .12       0
  162.03     .08       0  193.21    .016       0  228.74     .12       0
Bank Sta=126.2,151.2
XS Rating Curve= 0 ,0
Exp/Cntr=0.3,0.1

Type RM Length L Ch R = 1 ,48979   ,90,90.1,90.1
XS GIS Cut Line= 2
     1797016.476       233077.63     1797245.643      233176.588
#Sta/Elev= 27
       0 1116.18     9.6 1114.74    28.8 1112.16    67.2 1107.61    76.8 1106.42
    86.4 1105.12      931104.336      96 1103.98   105.6 1103.64   115.2 1103.97
     1181104.265   124.8 1104.98   134.4 1107.01     144 1110.27   153.6 1114.28
  156.451115.286   163.2 1117.67   172.8 1119.43   182.4 1120.42     192  1122.9
  196.151124.742   201.6 1127.16   211.2 1132.44   220.8 1138.25   230.4 1144.18
     240 1149.87   249.6 1154.96
#Mann= 5 ,-1 , 0
       0     .12       0      93    .045       0     118     .12       0
  156.45    .016       0  196.15     .12       0
Bank Sta=93,118
XS Rating Curve= 0 ,0
Exp/Cntr=0.3,0.1

Type RM Length L Ch R = 1 ,48888.9 ,174.1,174.8,175.4
XS GIS Cut Line= 2
     1796967.865      233154.019     1797184.879      233247.769
#Sta/Elev= 29
       0 1115.58     9.5  1114.5    18.9 1113.81    28.4 1113.49    37.8 1113.35
    47.3 1113.07    56.7 1112.43    66.2 1111.31    75.6 1109.72    85.1 1107.28
   90.37 1105.71    94.6 1104.45   98.761103.606     104 1102.54   113.5 1102.39
   122.9 1103.62   132.4 1105.42  137.571106.685   141.8 1107.72   151.3 1110.86
   160.8 1114.53  169.991117.825   179.7 1119.82   189.1 1120.85   198.6 1123.08
  205.391126.085     208 1127.24   217.5 1132.37   236.4 1142.91
#Mann= 7 ,-1 , 0
       0     .12       0   90.37     .06       0   98.76    .045       0
   122.9     .12       0  137.57     .08       0  169.99    .016       0
  205.39     .12       0
Bank Sta=98.76,122.9
XS Rating Curve= 0 ,0
Exp/Cntr=0.3,0.1