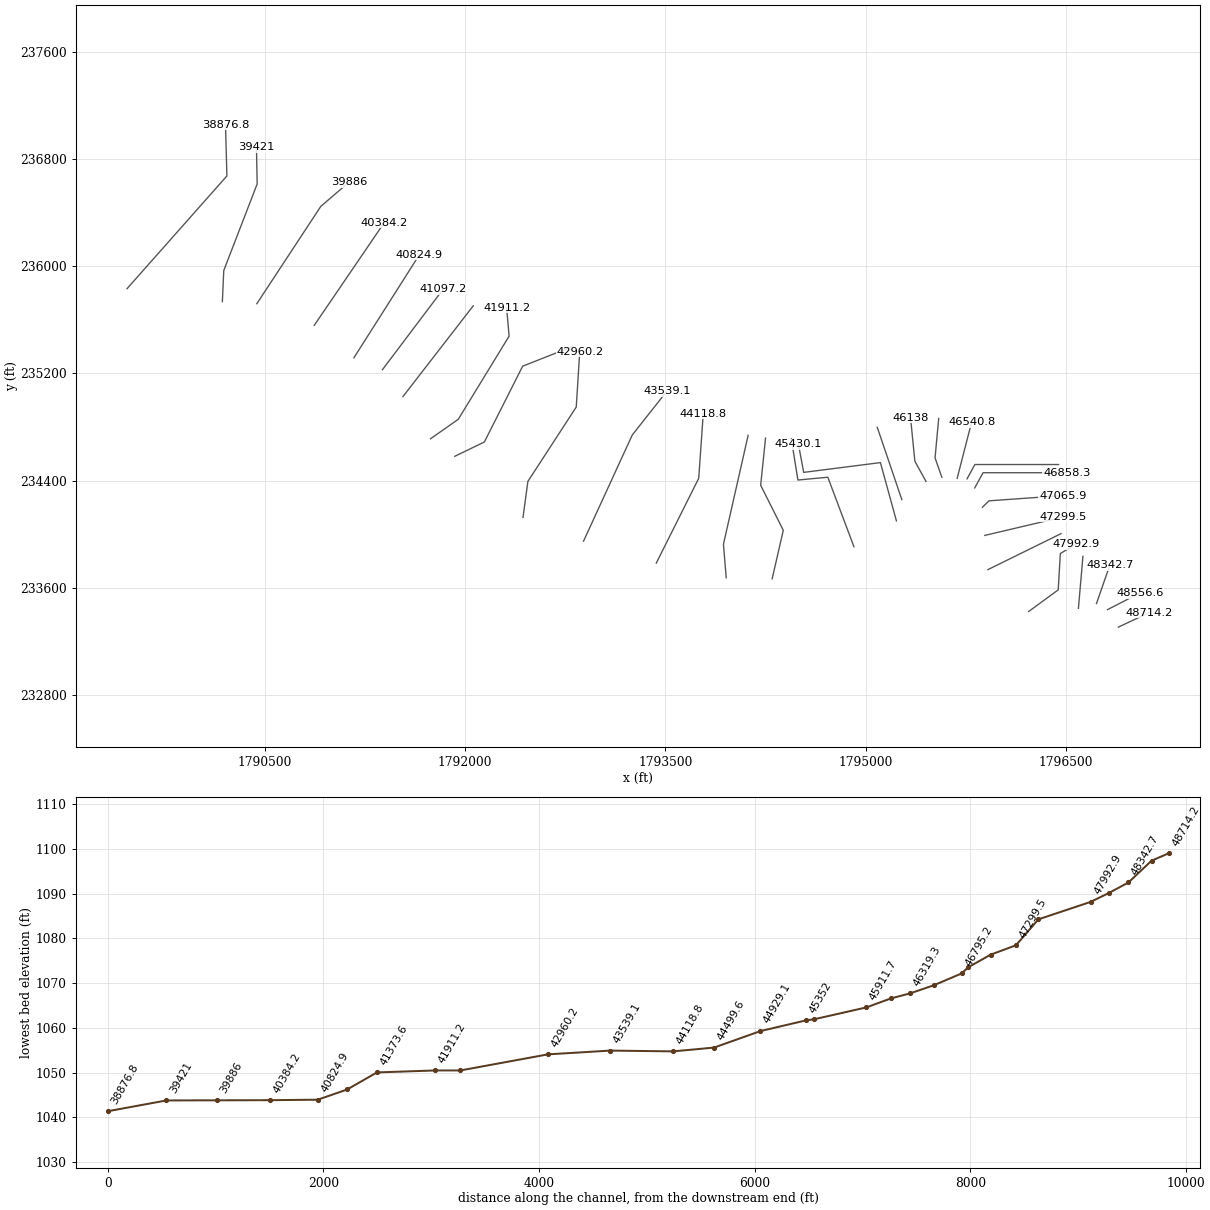
HEC-RAS study ELKCK.prj: ELKCK

--- ELKCK.g01 (geometry) --- (continued)

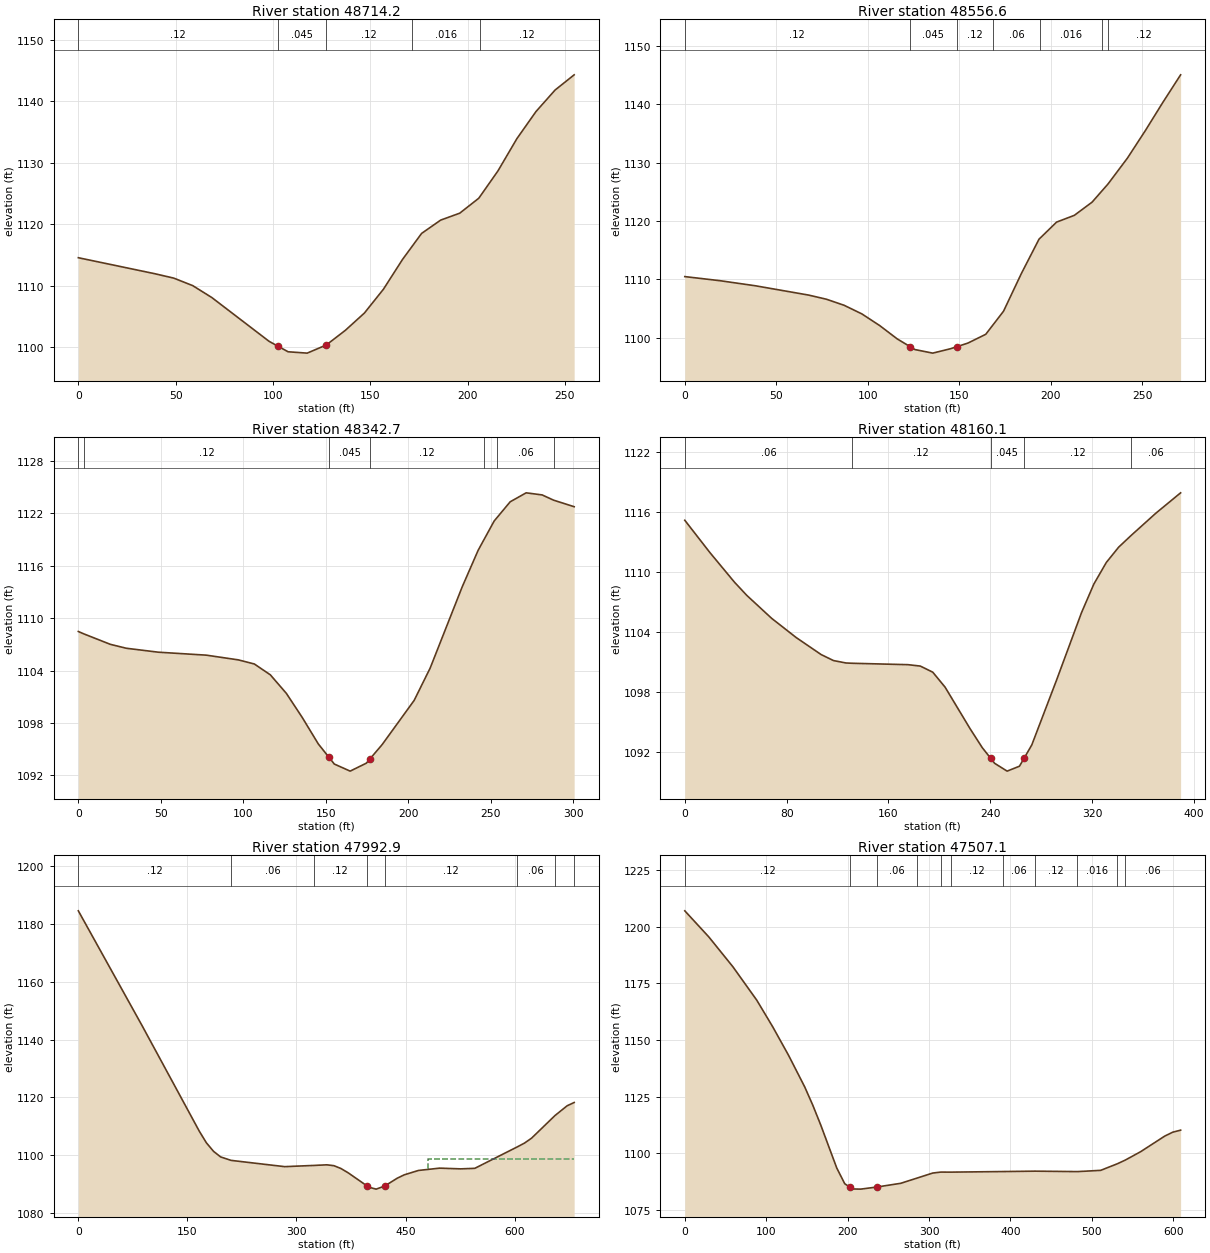
Type RM Length L Ch R = 1 ,48714.2 ,156.8,157.6,158.4
XS GIS Cut Line= 2
      1796889.74      233306.796     1797120.643      233414.435
#Sta/Elev= 25
       0 1114.53    39.2 1111.93      49 1111.21    58.8 1109.98    68.6 1108.04
      98 1100.91  102.451100.134   107.8  1099.2   117.6 1098.98   127.4  1100.3
   137.2 1102.69     147 1105.51   156.8  1109.4   166.6 1114.25  171.511116.374
   176.4 1118.49   186.2 1120.66     196 1121.79   205.8 1124.23  206.541124.564
   215.6 1128.66   225.4 1133.95   235.2 1138.36     245 1141.86   254.8 1144.34
#Mann= 5 ,-1 , 0
       0     .12       0  102.45    .045       0   127.4     .12       0
  171.51    .016       0  206.54     .12       0
Bank Sta=102.45,127.4
XS Rating Curve= 0 ,0
Exp/Cntr=0.3,0.1

Type RM Length L Ch R = 1 ,48556.6 ,196.2,213.9,231
XS GIS Cut Line= 2
     1796808.143      233437.005     1797049.462      233560.269
#Sta/Elev= 30
       0 1110.47    19.4 1109.76    38.7 1108.89    67.7  1107.3    77.4 1106.59
    87.1 1105.55    96.8 1104.07   106.5 1102.08   116.1 1099.79  123.051098.479
   125.8 1097.96   135.5 1097.35   145.2  1098.1   148.61098.447   154.8 1099.08
   164.5 1100.58  168.421102.176   174.2 1104.53   183.9 1110.96   193.6 1116.88
  194.391117.121   203.2 1119.81   212.9 1120.97   222.6 1123.23  227.841125.104
  231.321126.349   241.9 1130.77   251.6 1135.44   261.3 1140.34     271 1145.06
#Mann= 7 ,-1 , 0
       0     .12       0  123.05    .045       0   148.6     .12       0
  168.42     .06       0  194.39    .016       0  227.84     .06       0
  231.32     .12       0
Bank Sta=123.05,148.6
XS Rating Curve= 0 ,0
Exp/Cntr=0.3,0.1

Type RM Length L Ch R = 1 ,48342.7 ,176.3,182.7,188.2
XS GIS Cut Line= 2
     1796726.112      233483.012      1796825.07      233766.866
#Sta/Elev= 30
       0 1108.48    3.471108.197    19.4 1107.01    29.1 1106.56    48.5 1106.11
    77.6 1105.77      97 1105.23   106.7 1104.76   116.4 1103.52   126.1  1101.4
   135.8 1098.62   145.5  1095.6   151.91094.083   155.2  1093.3   164.8 1092.49
   174.6  1093.4   176.9 1093.91   184.2 1095.53   203.6 1100.59   213.3 1104.29
   232.7 1113.58   242.4 1117.78  246.221119.099   252.1 1121.13  254.011121.563
   261.8 1123.33   271.5 1124.36   281.2 1124.12  288.141123.519   300.6 1122.77
#Mann= 7 ,-1 , 0
       0     .06       0    3.47     .12       0   151.9    .045       0
   176.9     .12       0  246.22     .08       0  254.01     .06       0
  288.14    .016       0
Bank Sta=151.9,176.9
XS Rating Curve= 0 ,0
Exp/Cntr=0.3,0.1

Type RM Length L Ch R = 1 ,48160.1 ,167.2,167.2,168
XS GIS Cut Line= 2
     1796590.695      233446.553     1796624.549      233834.574
#Sta/Elev= 30
       0 1115.17    19.5 1111.98      39 1108.99    48.7 1107.67    68.2 1105.38
    87.6 1103.45   107.1 1101.76   116.8 1101.16   126.6 1100.92  131.331100.891
   175.3 1100.75     185 1100.61   194.8    1100   204.5  1098.5     224 1094.38
   233.7 1092.46  240.241091.408   243.4  1090.9   253.2 1090.12   262.9 1090.61
  266.551091.411   272.6 1092.74   292.1 1099.23   311.6 1105.93   321.3 1108.79
   331.1 1110.95   340.8 1112.48  350.471113.635     370 1115.87   389.5 1117.91
#Mann= 5 ,-1 , 0
       0     .06       0  131.33     .12       0  240.24    .045       0
  266.55     .12       0  350.47     .06       0
Bank Sta=240.24,266.55
XS Rating Curve= 0 ,0
Exp/Cntr=0.3,0.1

Type RM Length L Ch R = 1 ,47992.9 ,510.1,485.8,461.8
XS GIS Cut Line= 4
     1796218.299      233423.116     1796439.653      233584.574
     1796455.278      233855.408     1796572.466       233925.72
#Sta/Elev= 30
       0 1184.59    88.1 1144.61   166.4 1108.22   176.1 1104.22   185.9 1101.27
   195.7 1099.32  210.041098.121   283.7 1095.95  323.86 1096.37   341.8 1096.58
   351.5 1096.28   361.2  1095.3   370.9 1093.85  396.831089.312   399.9  1088.8
   409.6 1088.16  421.15  1089.2   438.7 1091.96   448.4 1093.13   467.8 1094.63
   496.8 1095.43   525.9 1095.18   545.3 1095.37  603.281102.743   613.6 1104.11
   623.4 1105.83  655.511113.651   672.2 1117.03  681.441118.125   681.9 1118.18
#Mann= 8 ,-1 , 0
       0     .12       0  210.04     .06       0  323.86     .12       0
  396.83    .045       0  421.15     .12       0  603.28     .06       0
  655.51     .08       0  681.44     .06       0
#XS Ineff= 2 , 0
                          481.11         1098.65
Permanent Ineff=
       F       F
Bank Sta=396.83,421.15
XS Rating Curve= 0 ,0
Exp/Cntr=0.3,0.1

Type RM Length L Ch R = 1 ,47507.1 ,212.4,207.6,202.2
XS GIS Cut Line= 2
     1795913.612      233735.616     1796460.487      234003.845
#Sta/Elev= 30
       0 1206.95    29.5 1195.45      59 1182.33    88.4 1167.56   108.1 1155.76
   127.7 1143.09   147.4 1129.25   157.2 1121.28     167 1112.52   186.7 1093.54
   196.5 1086.61  203.271085.024   206.3 1084.31   216.1 1084.24   235.8 1085.16
   265.3 1086.81  285.391089.115   304.6 1091.33  314.371091.749  326.911091.733
  390.871091.988  430.421092.162   482.41091.965   510.9 1092.52  531.491095.435
  541.171097.055     560 1100.75   589.5  1107.6   599.3 1109.33   609.1 1110.24
#Mann= 11 ,-1 , 0
       0     .12       0  203.27    .045       0   235.8     .06       0
  285.39     .12       0  314.37     .06       0  326.91     .12       0
  390.87     .06       0  430.42     .12       0   482.4    .016       0
  531.49     .12       0  541.17     .06       0
Bank Sta=203.27,235.8
XS Rating Curve= 0 ,0
Exp/Cntr=0.3,0.1

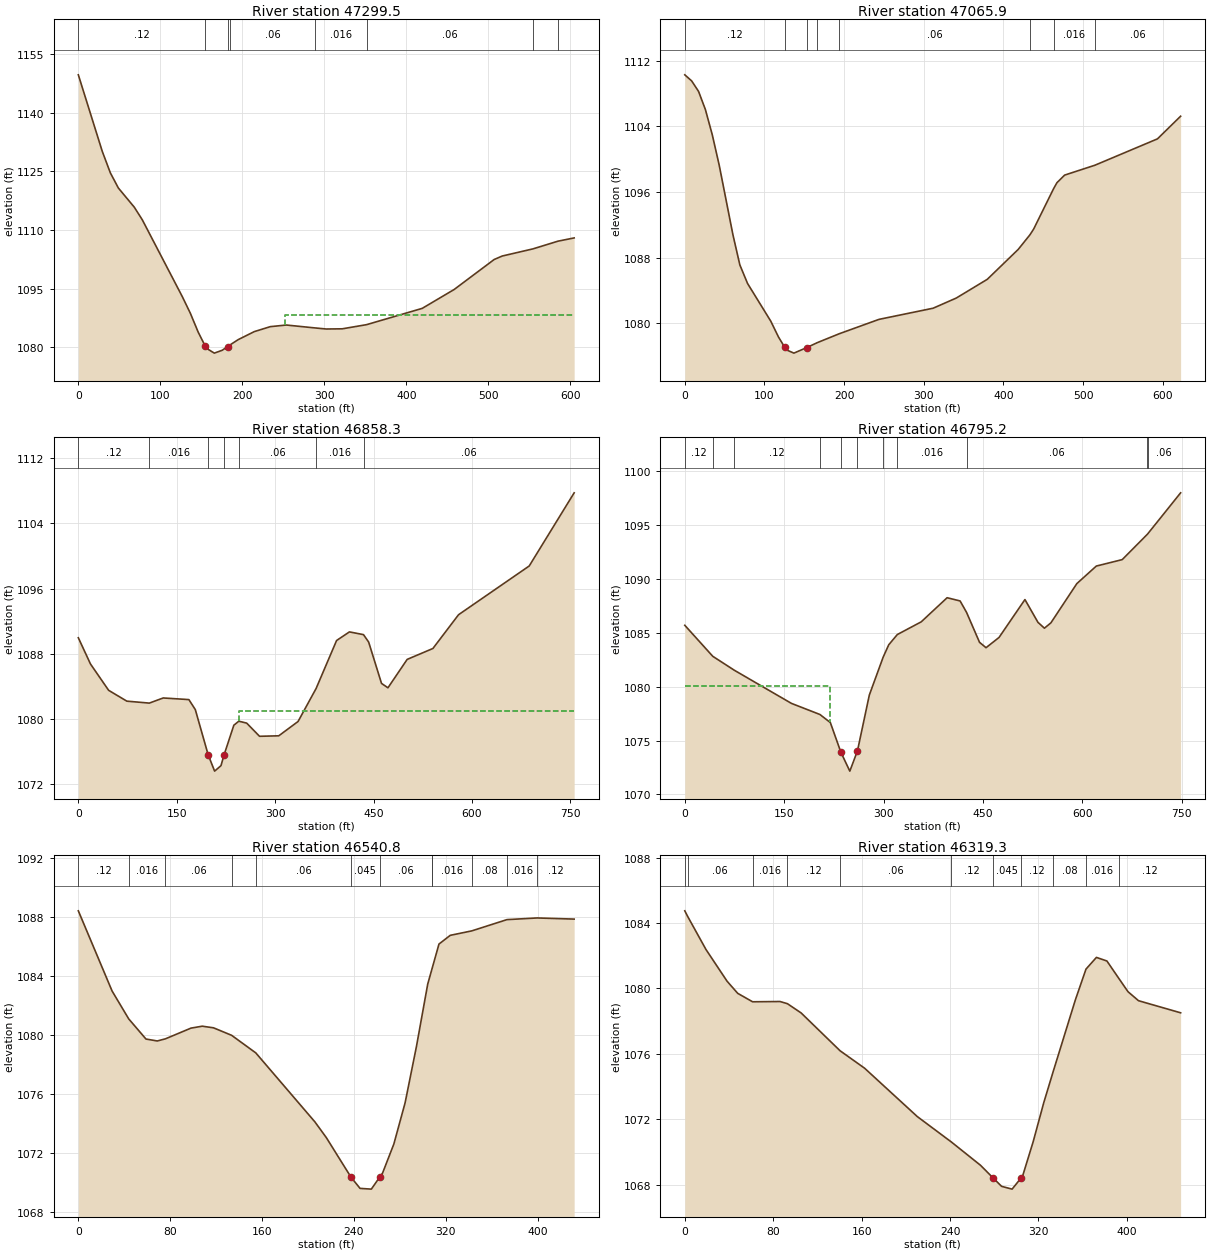
Type RM Length L Ch R = 1 ,47299.5 ,237.2,233.6,229.9
XS GIS Cut Line= 2
     1795890.174      233990.824     1796478.716      234128.845
#Sta/Elev= 30
       0 1149.77    29.2 1130.15      39 1124.67    48.8 1120.77    68.2 1115.86
      78 1112.62   126.8 1092.92   136.5 1088.71   146.2 1083.81  154.881080.187
     156 1079.72   165.8 1078.46   175.5  1079.2     1821080.138  185.291080.612
     195 1081.93   214.5 1083.97     234 1085.24   253.5 1085.66  288.451084.919
   302.2 1084.64   321.8 1084.69  351.391085.752   419.3 1089.93   458.3 1094.78
     507 1102.45   516.8 1103.34  554.281105.172  584.741107.144   604.5 1107.98
#Mann= 8 ,-1 , 0
       0     .12       0  154.88    .045       0     182     .12       0
  185.29     .06       0  288.45    .016       0  351.39     .06       0
  554.28     .08       0  584.74    .016       0
#XS Ineff= 2 , 0
                          251.39         1088.11
Permanent Ineff=
       F       F
Bank Sta=154.88,182
XS Rating Curve= 0 ,0
Exp/Cntr=0.3,0.1

Type RM Length L Ch R = 1 ,47065.9 ,209.1,207.7,206
XS GIS Cut Line= 3
     1795871.945       234200.46     1795921.424      234248.637
     1796473.507      234287.699
#Sta/Elev= 30
       0 1110.26     8.6 1109.52    17.3 1108.24    25.9 1106.02    34.5 1102.96
    43.2 1099.26    60.4  1090.8    69.1 1087.12    78.8 1084.85   107.9 1080.27
   117.6 1078.34  125.381077.089   127.3 1076.78     137 1076.37  153.261077.051
  166.411077.649  194.031078.734   243.8 1080.48   311.8 1081.84   340.9 1083.08
   379.8 1085.36   418.6    1089  433.261090.771     438 1091.48  462.911096.376
   467.2 1097.12   476.9 1098.05  514.871099.251   593.4 1102.46   622.5 1105.22
#Mann= 8 ,-1 , 0
       0     .12       0  125.38    .045       0  153.26     .06       0
  166.41    .016       0  194.03     .06       0  433.26     .08       0
  462.91    .016       0  514.87     .06       0
Bank Sta=125.38,153.26
XS Rating Curve= 0 ,0
Exp/Cntr=0.3,0.1

Type RM Length L Ch R = 1 ,46858.3 ,64.1,63,62.2
XS GIS Cut Line= 3
     1795814.653      234344.991     1795877.153      234458.272
     1796503.455      234458.272
#Sta/Elev= 30
       0 1089.95    18.5 1086.73    46.2 1083.49    73.9 1082.16  108.161081.919
   129.4 1082.55   168.5 1082.35   178.3 1081.12   197.9 1075.56   207.7 1073.56
   217.4 1074.23  222.211075.575     237  1079.2  244.591079.696   256.6 1079.46
   276.2 1077.84   305.5  1077.9   334.9 1079.66  362.391083.713   393.6 1089.61
   413.2 1090.67  434.651090.333   442.5 1089.42   462.1 1084.34   471.9  1083.8
   501.2 1087.29   540.4 1088.63   579.5 1092.78   687.2 1098.77   755.7 1107.76
#Mann= 7 ,-1 , 0
       0     .12       0  108.16    .016       0   197.9    .045       0
  222.21     .08       0  244.59     .06       0  362.39    .016       0
  434.65     .06       0
#XS Ineff= 2 , 0
                           245.2         1081.01
Permanent Ineff=
       F       F
Bank Sta=197.9,222.21
XS Rating Curve= 0 ,0
Exp/Cntr=0.3,0.1

Type RM Length L Ch R = 1 ,46795.2 ,223.5,254.4,285.1
XS GIS Cut Line= 3
     1795757.362      234412.699     1795815.955       234519.47
     1796442.257       234519.47
#Sta/Elev= 30
       0  1085.7   42.211082.821   74.771081.525   160.9 1078.45  203.861077.419
   219.6 1076.67   235.51073.913     249 1072.16   260.51074.038   278.4 1079.22
  299.211082.729   307.7 1083.89  320.641084.841   356.7 1086.02   395.8 1088.26
   415.4 1087.96  425.161086.894   444.7 1084.12   454.5 1083.62   474.1 1084.57
   513.2 1088.09   532.8 1085.98   542.6 1085.43   552.4 1085.93   591.5 1089.57
   620.9  1091.2     660  1091.8  697.861094.147  698.161094.168   748.1    1098
#Mann= 11 ,-1 , 0
       0     .12       0   42.21    .016       0   74.77     .12       0
  203.86     .06       0   235.5    .045       0   260.5     .06       0
  299.21     .08       0  320.64    .016       0  425.16     .06       0
  697.86     .12       0  698.16     .06       0
#XS Ineff= 2 , 0
          218.78 1080.08
Permanent Ineff=
       F       F
Bank Sta=235.5,260.5
XS Rating Curve= 0 ,0
Exp/Cntr=0.3,0.1

Type RM Length L Ch R = 1 ,46540.8 ,217.9,221.6,225.1
XS GIS Cut Line= 2
     1795683.143      234416.606     1795791.216      234834.574
#Sta/Elev= 30
       0 1088.39    29.4 1082.96   43.871081.075    58.9 1079.71    68.7 1079.58
   75.831079.725    98.1 1080.45   107.9 1080.58   117.7 1080.47  133.461079.963
  154.521078.772     206  1074.1   215.9 1073.04  237.461070.353   245.3  1069.6
   255.1 1069.55  262.281070.348   264.9 1070.64   274.7  1072.6   284.5 1075.39
   294.4 1079.21   304.2 1083.43   308.21084.536  308.331084.572     314 1086.14
   323.8 1086.73   342.61087.033  373.151087.794  399.471087.907   431.7 1087.83
#Mann= 12 ,-1 , 0
       0     .12       0   43.87    .016       0   75.83     .06       0
  133.46     .12       0  154.52     .06       0  237.46    .045       0
  262.28     .06       0   308.2     .08       0  308.33    .016       0
   342.6     .08       0  373.15    .016       0  399.47     .12       0
Bank Sta=237.46,262.28
XS Rating Curve= 0 ,0
Exp/Cntr=0.3,0.1

Type RM Length L Ch R = 1 ,46319.3 ,176.9,181.3,185.6
XS GIS Cut Line= 3
     1795568.559      234424.418     1795517.778      234568.949
     1795545.122       234863.22
#Sta/Elev= 30
       0 1084.75    2.521084.417    19.2 1082.38    38.3 1080.44    47.9  1079.7
   61.371079.184    86.2  1079.2   92.861079.068   105.3  1078.5  140.491076.189
   162.7 1075.12   210.4 1072.16  241.221070.605   267.6 1069.18  279.011068.403
   286.7 1067.89   296.2 1067.72  304.121068.386   305.7 1068.52   315.3 1070.63
   324.8    1073  333.421074.924   353.4 1079.29  363.051081.182   372.5  1081.9
     382 1081.68  392.671080.625   401.1  1079.8   410.6 1079.25   448.7 1078.51
#Mann= 11 ,-1 , 0
       0     .12       0    2.52     .06       0   61.37    .016       0
   92.86     .12       0  140.49     .06       0  241.22     .12       0
  279.01    .045       0  304.12     .12       0  333.42     .08       0
  363.05    .016       0  392.67     .12       0
Bank Sta=279.01,304.12
XS Rating Curve= 0 ,0
Exp/Cntr=0.3,0.1

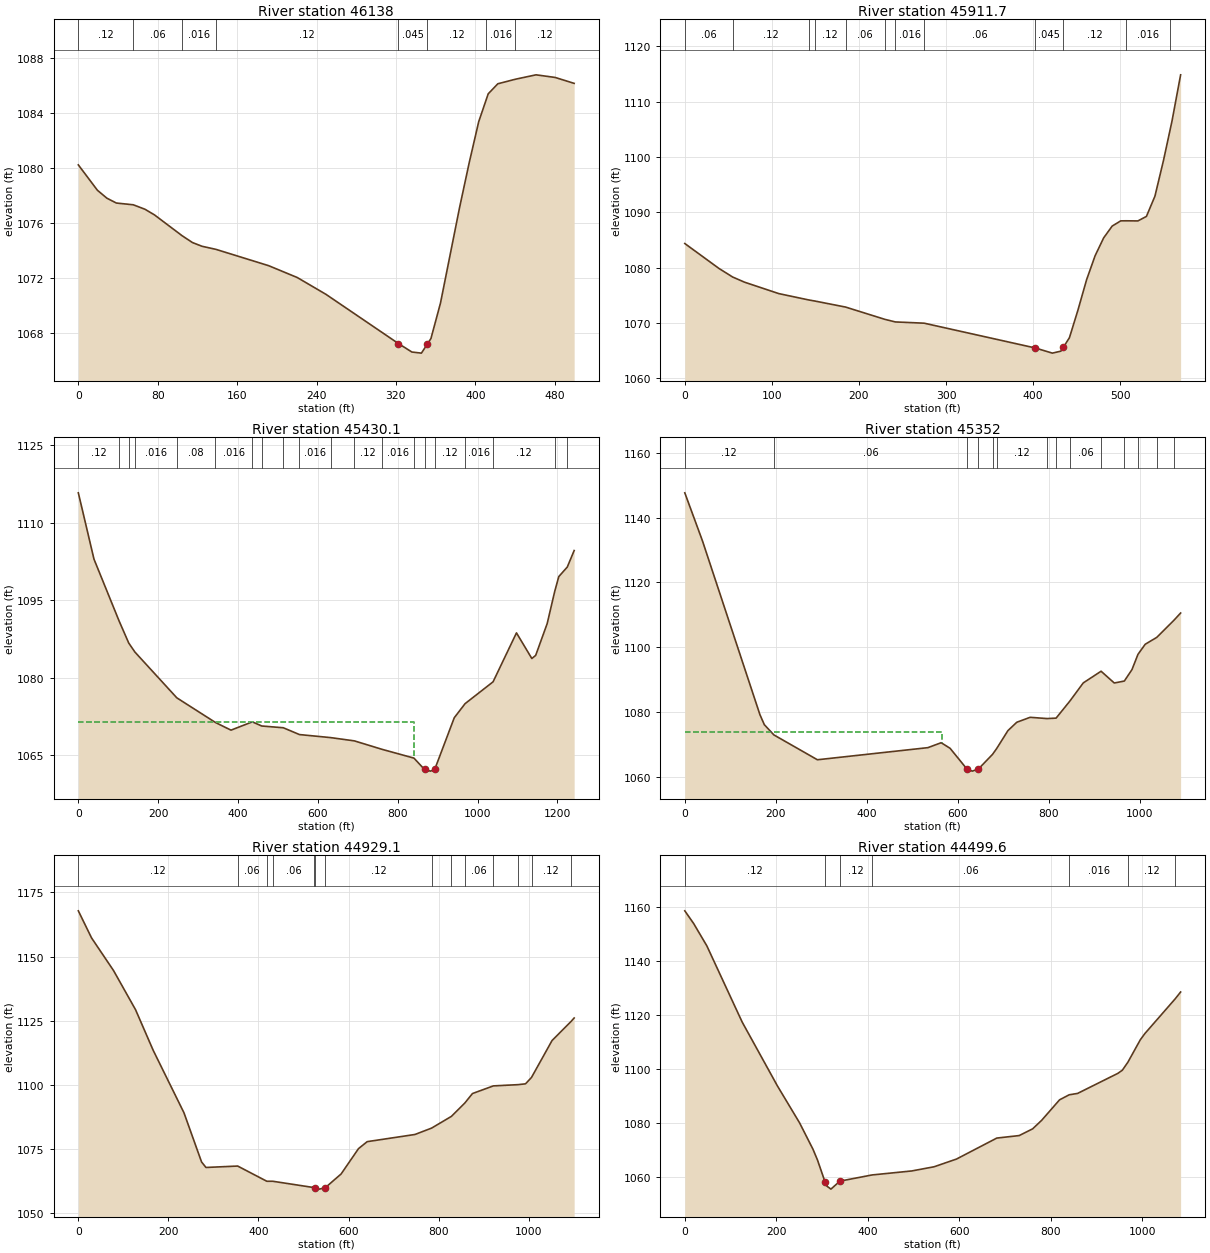
Type RM Length L Ch R = 1 ,46138   ,221.2,226.3,231.5
XS GIS Cut Line= 3
      1795450.07      234393.168     1795366.737       234544.21
     1795334.184      234869.731
#Sta/Elev= 30
       0 1080.24    19.2  1078.4    28.8 1077.82    38.3 1077.47   55.381077.342
    67.1 1077.02    76.7 1076.61  104.631075.093     115  1074.6   124.6 1074.33
  138.681074.105   191.8 1072.92   220.6 1072.06   249.5 1070.84  322.491067.268
   336.1 1066.65   345.7 1066.57  351.761067.237   355.3 1067.63   364.9  1070.2
   384.2 1077.16   393.8 1080.38   403.4 1083.37   410.61084.893     413  1085.4
   422.7 1086.13  440.341086.459   461.2 1086.78   480.4 1086.59   499.6 1086.16
#Mann= 8 ,-1 , 0
       0     .12       0   55.38     .06       0  104.63    .016       0
  138.68     .12       0  322.49    .045       0  351.76     .12       0
   410.6    .016       0  440.34     .12       0
Bank Sta=322.49,351.76
XS Rating Curve= 0 ,0
Exp/Cntr=0.3,0.1

Type RM Length L Ch R = 1 ,45911.7 ,362.1,481.6,519.8
XS GIS Cut Line= 2
      1795269.08      234257.751     1795085.487      234796.814
#Sta/Elev= 30
       0 1084.37    39.3 1079.86    54.91078.323    68.7 1077.38     108 1075.32
  142.271074.179  149.351073.981   184.71072.889  229.641070.678   241.81070.205
  274.88 1069.98   402.6  1065.5   422.2 1064.57     432 1064.93   434.8 1065.62
   441.8 1067.36   451.6 1072.36   461.5 1077.83   471.3 1082.17   481.1 1085.39
   490.9 1087.52   500.7 1088.46  506.571088.472   520.4 1088.45   530.2 1089.26
     540 1092.92   549.8 1099.36  557.341104.846   559.6 1106.49   569.5 1114.84
#Mann= 12 ,-1 , 0
       0     .06       0    54.9     .12       0  142.27     .06       0
  149.35     .12       0   184.7     .06       0  229.64     .12       0
   241.8    .016       0  274.88     .06       0   402.6    .045       0
   434.8     .12       0  506.57    .016       0  557.34     .12       0
Bank Sta=402.6,434.8
XS Rating Curve= 0 ,0
Exp/Cntr=0.3,0.1

Type RM Length L Ch R = 1 ,45430.1 ,164,78.1,75
XS GIS Cut Line= 4
     1795228.716      234098.897     1795108.924      234533.793
     1794534.705      234460.876     1794495.643       234669.21
#Sta/Elev= 30
       0 1115.79    39.2 1102.96  101.811091.054  126.241086.725  141.761084.977
  246.681076.123  343.491071.348   382.4 1069.87  435.831071.475   459.4 1070.67
  513.281070.333  553.931069.014  631.681068.428  691.361067.794  761.321066.144
  840.561064.461   867.1 1062.26   882.1 1061.94   892.6 1062.26   941.6 1072.27
  968.711074.996 1038.821079.221  1097.4 1088.69  1135.9 1083.73  1145.5 1084.33
  1174.4  1090.5 1193.031096.662  1203.4 1099.58 1224.691101.431  1241.9 1104.62
#Mann= 20 ,-1 , 0
       0     .12       0  101.81     .06       0  126.24     .12       0
  141.76    .016       0  246.68     .08       0  343.49    .016       0
  435.83     .12       0   459.4     .06       0  513.28     .12       0
  553.93    .016       0  631.68     .06       0  691.36     .12       0
  761.32    .016       0  840.56     .06       0   867.1    .045       0
   892.6     .12       0  968.71    .016       0 1038.82     .12       0
 1193.03    .016       0 1224.69     .12       0
#XS Ineff= 2 , 0
          840.87 1071.35
Permanent Ineff=
       F       F
Bank Sta=867.1,892.6
XS Rating Curve= 0 ,0
Exp/Cntr=0.3,0.1

Type RM Length L Ch R = 1 ,45352   ,452.7,422.9,390.6
XS GIS Cut Line= 4
     1794910.617      233906.449     1794715.304      234424.678
     1794491.346      234403.845     1794441.867      234711.137
#Sta/Elev= 30
       0 1147.63    38.9 1132.77   165.2 1079.11   174.9 1076.01  195.931072.857
   291.5 1065.19   534.4 1068.93   563.6 1070.45   583.2 1068.73  620.171062.339
     632 1061.68  645.351062.318   676.51066.856  685.581068.643   710.3 1074.18
   729.8 1076.77   759.2  1078.3  796.241077.911  816.241078.053  846.241083.263
     876 1088.93  915.161092.533   944.1  1088.9  966.251089.498     983 1093.02
  996.251097.747  1012.2 1100.87 1037.551102.983 1075.651108.323    1090 1110.51
#Mann= 14 ,-1 , 0
       0     .12       0  195.93     .06       0  620.17    .045       0
  645.35     .12       0   676.5     .06       0  685.58     .12       0
  796.24    .016       0  816.24     .12       0  846.24     .06       0
  915.16     .12       0  966.25     .06       0  996.25    .016       0
 1037.55     .06       0 1075.65    .016       0
#XS Ineff= 2 , 0
          564.71 1073.68
Permanent Ineff=
       F       F
Bank Sta=620.17,645.35
XS Rating Curve= 0 ,0
Exp/Cntr=0.3,0.1

Type RM Length L Ch R = 1 ,44929.1 ,445.3,429.5,413.8
XS GIS Cut Line= 4
     1794298.638      233666.866     1794381.971      234028.845
       1794212.7      234364.783     1794249.158      234716.345
#Sta/Elev= 30
       0 1167.85    29.3  1157.3    78.2 1144.55   127.1 1129.27   166.2 1113.45
   234.6 1089.06   273.7 1069.87   283.5 1067.73  353.841068.281  418.581062.353
  432.261062.338  522.691059.902   525.8 1059.69   535.4 1059.28   548.6 1059.87
   583.6  1065.2   622.2 1075.08   641.5  1077.8   747.6  1080.6  784.461083.079
  828.531087.665  858.181092.848   875.3 1096.57  921.561099.549  976.771100.039
   993.1 1100.36 1006.42 1102.86    1052 1117.25 1094.531124.746  1101.1 1126.04
#Mann= 14 ,-1 , 0
       0     .12       0  353.84     .06       0  418.58     .12       0
  432.26     .06       0  522.69     .12       0   525.8    .045       0
   548.6     .12       0  784.46     .06       0  828.53    .016       0
  858.18     .06       0  921.56     .12       0  976.77    .016       0
 1006.42     .12       0 1094.53     .06       0
Bank Sta=525.8,548.6
XS Rating Curve= 0 ,0
Exp/Cntr=0.3,0.1

Type RM Length L Ch R = 1 ,44499.6 ,386,380.9,375.1
XS GIS Cut Line= 3
     1793954.888      233674.678     1793934.054      233924.678
      1794118.95      234737.178
#Sta/Elev= 30
       0 1158.73    19.3 1154.04    48.2 1145.75   125.4 1117.53   202.6 1093.82
   250.9 1080.18   280.3 1070.37   290.1  1066.4  306.391058.389   309.7 1056.84
   319.5  1055.6   339.1 1058.56  409.481060.854     496 1062.33     545 1063.88
     594 1066.74   682.2 1074.52   731.2 1075.45   760.6 1077.95   780.2 1081.09
   819.4 1088.69  840.551090.562   858.7 1091.06   946.9  1098.5   956.7 1099.67
  968.711102.612   995.9 1110.92  1005.7  1113.2 1072.111126.095  1084.1 1128.65
#Mann= 7 ,-1 , 0
       0     .12       0  306.39    .045       0   339.1     .12       0
  409.48     .06       0  840.55    .016       0  968.71     .12       0
 1072.11     .06       0
Bank Sta=306.39,339.1
XS Rating Curve= 0 ,0
Exp/Cntr=0.3,0.1

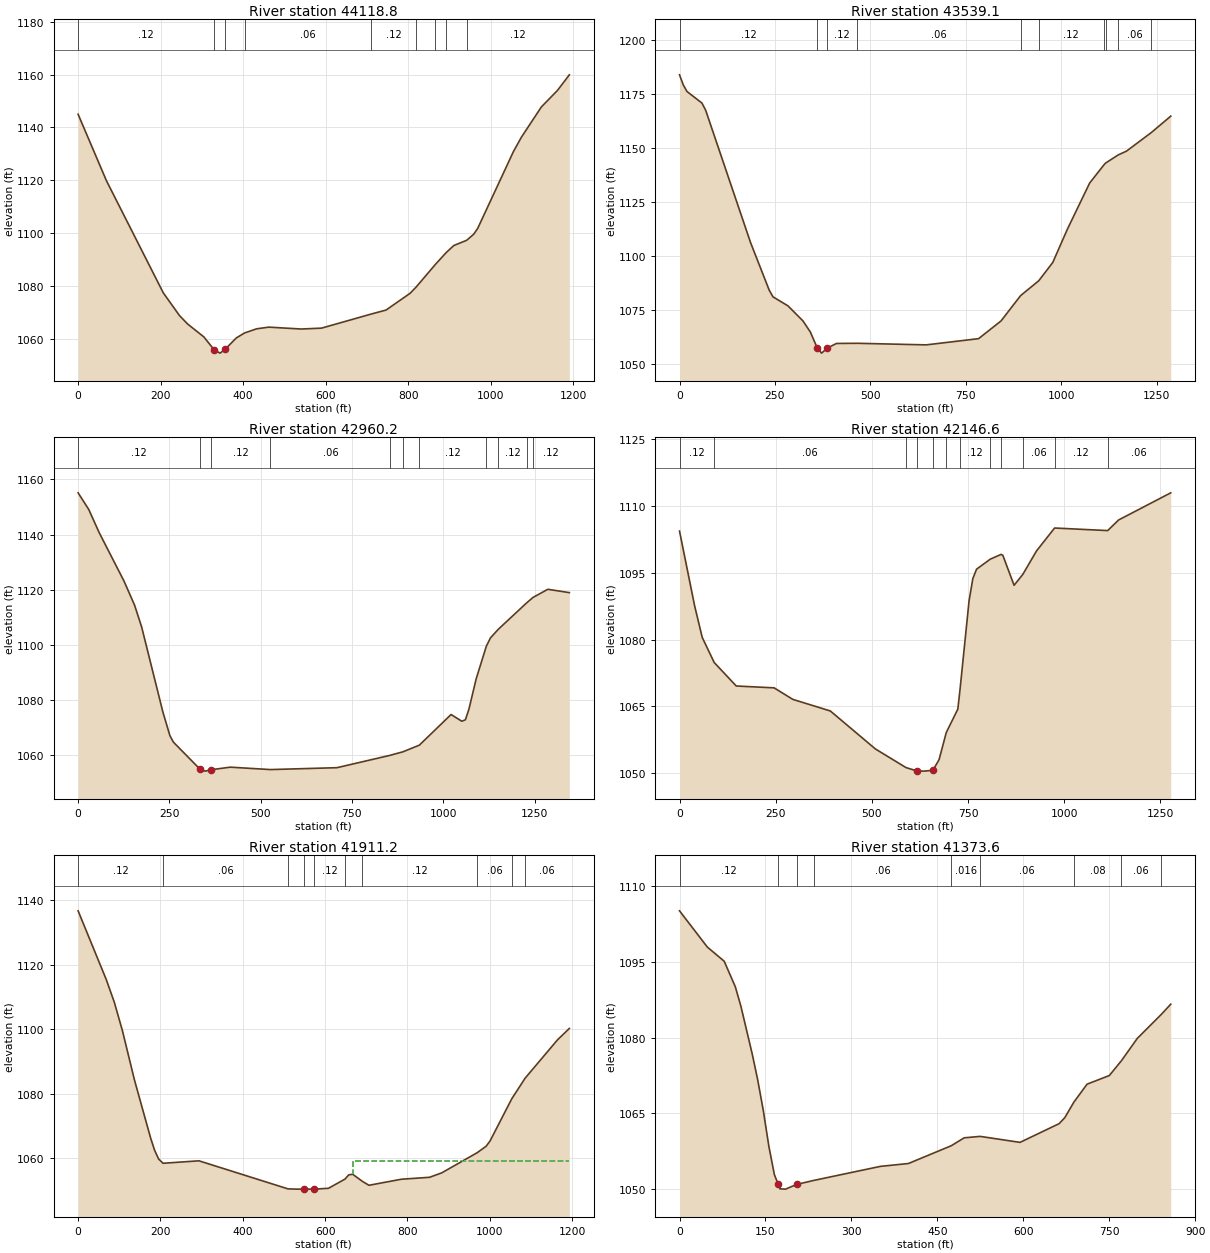
Type RM Length L Ch R = 1 ,44118.8 ,578.8,579.6,580.4
XS GIS Cut Line= 3
      1793431.45      233784.053     1793749.158      234416.866
     1793783.013      234898.637
#Sta/Elev= 30
       0 1145.01    68.8 1119.86   206.5 1077.54   245.9 1068.92   265.5 1065.76
   304.9 1060.88  329.761056.011   344.2 1054.75   356.11056.161   383.6 1060.49
  403.441062.356   432.7 1063.93   462.2 1064.57   540.9 1063.86   590.1 1064.19
  711.091069.531   746.7 1071.03   804.7 1077.33  819.07 1079.63  866.421088.298
  892.261092.717   910.9 1095.41   941.91097.363   959.2 1099.68   968.9 1101.91
  1055.8 1131.01  1075.1 1136.41  1123.4 1147.81  1162.1 1153.98    1191  1159.9
#Mann= 9 ,-1 , 0
       0     .12       0  329.76    .045       0   356.1     .12       0
  403.44     .06       0  711.09     .12       0  819.07     .06       0
  866.42     .12       0  892.26    .016       0   941.9     .12       0
Bank Sta=329.76,356.1
XS Rating Curve= 0 ,0
Exp/Cntr=0.3,0.1

Type RM Length L Ch R = 1 ,43539.1 ,582.2,578.9,575.5
XS GIS Cut Line= 3
     1792887.179      233948.116     1793251.763      234739.783
     1793509.575      235065.303
#Sta/Elev= 30
       0 1183.75     9.8 1179.12    19.6 1176.03    58.8 1170.67    68.6 1167.31
   186.1 1106.09     235 1084.06   244.8 1080.99     284 1076.82   323.2 1069.88
   342.8 1064.68  360.751057.332   372.1 1054.93   387.61057.316   411.3 1059.41
  465.221059.485   646.3 1058.75   783.4 1061.63   842.2 1069.83  893.361081.528
  941.061088.439   977.8 1096.91  1016.4 1112.44  1074.4 1133.67 1111.281141.961
 1116.121142.899 1149.071146.666    1171 1148.44  1235.91157.035  1286.8 1164.62
#Mann= 10 ,-1 , 0
       0     .12       0  360.75    .045       0   387.6     .12       0
  465.22     .06       0  893.36    .016       0  941.06     .12       0
 1111.28     .06       0 1116.12     .12       0 1149.07     .06       0
  1235.9     .12       0
Bank Sta=360.75,387.6
XS Rating Curve= 0 ,0
Exp/Cntr=0.3,0.1

Type RM Length L Ch R = 1 ,42960.2 ,811,813.6,815.6
XS GIS Cut Line= 4
     1792434.054      234125.199     1792470.513      234393.428
     1792832.492      234948.116     1792858.533      235359.574
#Sta/Elev= 30
       0 1155.15      29 1149.15      58 1140.63   125.7 1123.11   154.7 1114.34
     174 1106.46     232 1075.65   251.4 1066.97     261 1064.62   333.8  1054.8
   348.6 1054.09  362.861054.569   416.8 1055.53  526.751054.654     709 1055.34
   854.81059.839  889.691061.109  934.461063.514  1021.4 1074.65  1050.8 1072.21
  1060.7 1072.74  1070.5 1076.68  1090.1 1087.57 1118.031099.469  1129.4 1102.48
 1150.69 1105.59 1228.02 1115.14 1245.58 1117.14  1286.4 1120.12  1345.3 1118.91
#Mann= 11 ,-1 , 0
       0     .12       0   333.8    .045       0  362.86     .12       0
  526.75     .06       0   854.8     .12       0  889.69    .016       0
  934.46     .12       0 1118.03    .016       0 1150.69     .12       0
 1228.02     .06       0 1245.58     .12       0
Bank Sta=333.8,362.86
XS Rating Curve= 0 ,0
Exp/Cntr=0.3,0.1

Type RM Length L Ch R = 1 ,42146.6 ,237.2,235.4,233.7
XS GIS Cut Line= 4
     1791923.638      234580.928     1792144.992      234687.699
      1792431.45      235252.803     1792801.242      235398.637
#Sta/Elev= 30
       0 1104.35    39.3 1087.57      59  1080.5   90.171074.862   147.5 1069.59
   245.8 1069.18   294.5 1066.59     392 1063.99   508.9 1055.48  588.531051.293
   616.2 1050.55   635.6 1050.49  658.491050.669   674.6 1053.06  693.281059.142
   723.4 1064.41  729.111068.819   752.6 1088.73   762.4  1093.7   772.1 1095.81
  807.611098.051   835.61099.119   840.3 1098.93   869.6 1092.19   892.41094.655
   927.8 1099.89  974.881105.043 1112.961104.467  1141.1 1106.84  1276.8 1112.94
#Mann= 12 ,-1 , 0
       0     .12       0   90.17     .06       0  588.53     .12       0
   616.2    .045       0  658.49     .12       0  693.28    .016       0
  729.11     .12       0  807.61     .06       0   835.6    .016       0
   892.4     .06       0  974.88     .12       0 1112.96     .06       0
Bank Sta=616.2,658.49
XS Rating Curve= 0 ,0
Exp/Cntr=0.3,0.1

Type RM Length L Ch R = 1 ,41911.2 ,539,537.6,536
XS GIS Cut Line= 4
     1791741.346      234711.137     1791949.679       234856.97
     1792329.888      235476.762     1792311.658      235687.699
#Sta/Elev= 30
       0 1136.71    68.5 1115.39      88 1108.37   107.6 1099.61   136.9  1084.3
   176.1 1066.34   185.8 1062.53   195.6 1059.82  206.331058.502   293.6 1059.26
   509.61050.575   529.4 1050.49   548.3 1050.49   573.3 1050.49     608 1050.74
   648.31053.606   657.2 1054.91     667 1055.09  689.991052.943   706.3 1051.68
   784.9 1053.55   853.7 1054.16   883.2 1055.53  969.111061.762     991 1063.77
  1000.7 1065.45 1053.261078.477  1085.61084.843  1164.3 1096.73  1193.1 1100.27
#Mann= 10 ,-1 , 0
       0     .12       0  206.33     .06       0   509.6     .12       0
   548.3    .045       0   573.3     .12       0   648.3    .016       0
  689.99     .12       0  969.11     .06       0 1053.26    .016       0
  1085.6     .06       0
#XS Ineff= 2 , 0
                          668.73         1059.09
Permanent Ineff=
       F       F
Bank Sta=548.3,573.3
XS Rating Curve= 0 ,0
Exp/Cntr=0.3,0.1

Type RM Length L Ch R = 1 ,41373.6 ,274.8,276.5,275.9
XS GIS Cut Line= 2
     1791535.617      235026.241     1792061.658      235703.324
#Sta/Elev= 30
       0 1105.05    48.7 1097.87      78 1095.09    97.4 1090.04   107.2 1086.17
   126.7 1076.85   136.4 1071.69   146.2 1065.61   155.9 1058.54   165.6  1052.9
  171.951051.092   175.4 1050.11   185.1 1050.05   204.6 1050.98  234.391051.773
   350.8 1054.55   399.5 1055.11  474.271058.624   496.9 1060.19  524.631060.475
   594.3 1059.29   662.6 1062.99   672.3 1064.15   688.51067.274   711.3 1070.79
   750.2  1072.5  771.321075.426     799 1079.84  840.091084.485   857.4  1086.6
#Mann= 9 ,-1 , 0
       0     .12       0  171.95    .045       0   204.6     .12       0
  234.39     .06       0  474.27    .016       0  524.63     .06       0
   688.5     .08       0  771.32     .06       0  840.09    .016       0
Bank Sta=171.95,204.6
XS Rating Curve= 0 ,0
Exp/Cntr=0.3,0.1

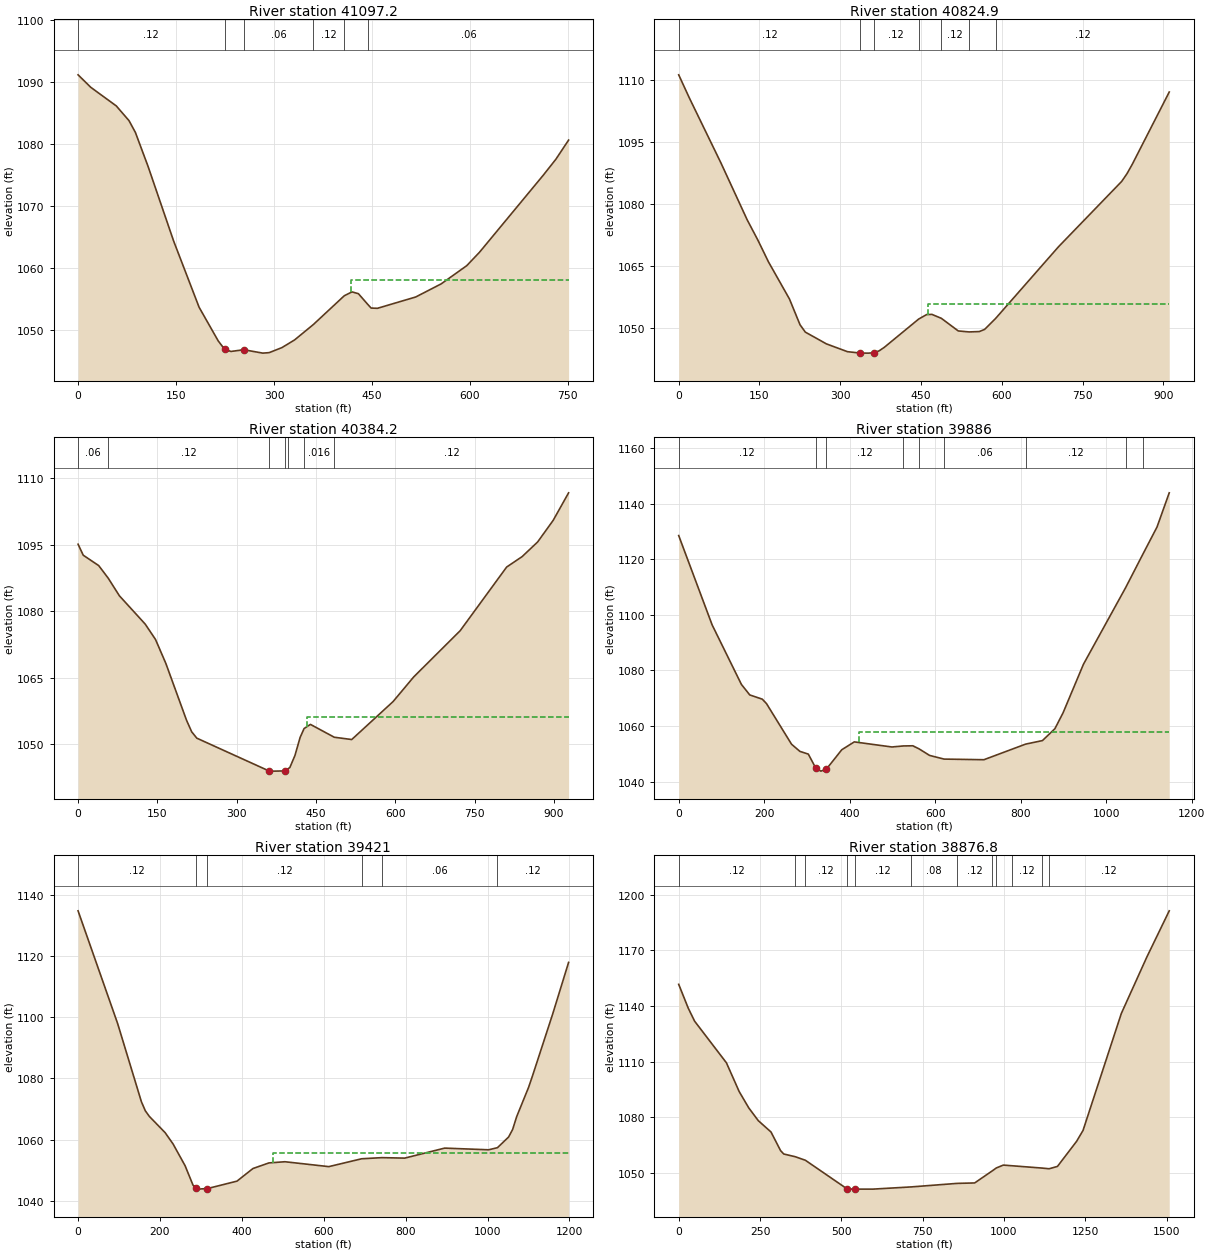
Type RM Length L Ch R = 1 ,41097.2 ,271.7,272.3,274.3
XS GIS Cut Line= 2
     1791381.971      235226.762     1791835.096       235825.72
#Sta/Elev= 30
       0 1091.19    19.5 1089.17    58.5 1086.17      78 1083.79    87.8 1081.88
   107.3 1076.36   146.3 1064.35   185.3 1053.65   214.6 1048.21   224.3 1046.87
   234.1 1046.51   253.6 1046.79   282.9 1046.24   292.6 1046.32   312.1 1047.13
   331.6 1048.38  360.331050.868  407.531055.503   419.4 1056.13   429.2 1055.84
  443.941054.064   448.7 1053.52   458.4 1053.48     517 1055.31     556 1057.43
     595 1060.36   614.5 1062.52     712 1074.95   731.5 1077.55     751 1080.65
#Mann= 6 ,-1 , 0
       0     .12       0   224.3    .045       0   253.6     .06       0
  360.33     .12       0  407.53    .016       0  443.94     .06       0
#XS Ineff= 2 , 0
                          418.58         1058.04
Permanent Ineff=
       F       F
Bank Sta=224.3,253.6
XS Rating Curve= 0 ,0
Exp/Cntr=0.3,0.1

Type RM Length L Ch R = 1 ,40824.9 ,441,440.8,439.3
XS GIS Cut Line= 2
     1791168.429      235315.303     1791658.013      236083.533
#Sta/Elev= 30
       0 1111.32    19.6 1105.77    78.4    1090   127.3 1076.19   146.9 1071.35
   166.5  1066.1   205.7 1057.06   225.3 1050.83   235.1 1049.05   274.3  1046.2
   313.4 1044.31   337.21043.975   352.6 1043.96   362.21044.058   372.2 1044.51
     382 1045.38  445.671052.207   460.4 1053.29   470.2 1053.34  487.761052.386
   519.2 1049.33   539.2 1049.09   558.3 1049.18   568.1  1049.7  588.411052.332
   705.3  1069.7   822.8 1085.54   832.6 1087.41   842.4 1089.68     911 1107.16
#Mann= 7 ,-1 , 0
       0     .12       0   337.2    .045       0   362.2     .12       0
  445.67    .016       0  487.76     .12       0   539.2     .04       0
  588.41     .12       0
#XS Ineff= 2 , 0
                          463.36         1055.81
Permanent Ineff=
       F       F
Bank Sta=337.2,362.2
XS Rating Curve= 0 ,0
Exp/Cntr=0.3,0.1

Type RM Length L Ch R = 1 ,40384.2 ,498.1,498.1,498
XS GIS Cut Line= 2
     1790871.554      235557.491     1791394.992      236323.116
#Sta/Elev= 30
       0 1095.13     9.8 1092.64      39  1090.3   56.991087.459    78.1 1083.48
   126.9 1077.08   146.4 1073.61     166 1068.18     205 1055.37   214.8 1052.74
   224.5  1051.3   361.2 1043.88     371 1043.85   390.5  1043.9  397.391044.427
   400.3 1044.65     410 1047.37   419.8 1051.46  427.331053.473   439.3 1054.41
  484.371051.508   517.4 1050.99   595.5 1059.56   634.6 1065.14   722.4 1075.58
   810.3 1089.97   839.6 1092.33   868.9 1095.64   898.2 1100.51   927.4 1106.74
#Mann= 7 ,-1 , 0
       0     .06       0   56.99     .12       0   361.2    .045       0
   390.5     .12       0  397.39     .08       0  427.33    .016       0
  484.37     .12       0
#XS Ineff= 2 , 0
                           432.4         1056.08
Permanent Ineff=
       F       F
Bank Sta=361.2,390.5
XS Rating Curve= 0 ,0
Exp/Cntr=0.3,0.1

Type RM Length L Ch R = 1 ,39886   ,459.8,465,469.6
XS GIS Cut Line= 3
     1790441.867      235718.949     1790921.033      236445.512
     1791131.971      236625.199
#Sta/Elev= 30
       0  1128.5    78.2 1096.38   146.7 1074.98   166.2 1071.21   195.6 1069.68
   205.4 1068.08     264 1053.48   283.6 1050.91   303.2 1049.94   320.31044.983
   332.5 1043.82   345.31044.509   381.4  1051.5   410.7 1054.33   498.7  1052.5
  525.29 1052.87   547.6 1052.93  562.721051.775   586.8 1049.47  620.691048.146
   713.9 1047.92  811.341053.522   850.8  1054.8   879.9 1059.06     899 1064.76
   946.8 1082.26 1045.281109.739 1086.631122.069  1118.8 1131.56  1147.4 1143.86
#Mann= 9 ,-1 , 0
       0     .12       0   320.3    .045       0   345.3     .12       0
  525.29    .016       0  562.72     .12       0  620.69     .06       0
  811.34     .12       0 1045.28    .016       0 1086.63     .12       0
#XS Ineff= 2 , 0
                          421.05         1057.84
Permanent Ineff=
       F       F
Bank Sta=320.3,345.3
XS Rating Curve= 0 ,0
Exp/Cntr=0.3,0.1

Type RM Length L Ch R = 1 ,39421   ,551.9,544.2,535.5
XS GIS Cut Line= 4
     1790184.054      235734.574     1790194.471      235966.345
     1790444.471      236612.178     1790439.263      236885.616
#Sta/Elev= 30
       0 1134.71    96.7 1097.87   154.7 1072.33   164.3 1069.38     174 1067.56
   212.7 1062.23     232 1058.55   261.3 1051.46   280.8 1045.08  288.761044.022
   290.5 1043.79  315.831043.969   388.1  1046.4   427.1 1050.52   466.1 1052.35
   505.1 1052.74   612.4 1051.14  692.651053.708  741.991054.076   797.7 1053.92
   895.3 1057.19  1002.7 1056.64  1024.31057.334  1051.5 1060.82  1061.3 1063.27
    1071  1067.4  1100.4 1077.08  1110.1  1080.9    1159 1100.94    1198 1117.86
#Mann= 6 ,-1 , 0
       0     .12       0  288.76    .045       0  315.83     .12       0
  692.65    .016       0  741.99     .06       0  1024.3     .12       0
#XS Ineff= 2 , 0
                          476.78         1055.71
Permanent Ineff=
       F       F
Bank Sta=288.76,315.83
XS Rating Curve= 0 ,0
Exp/Cntr=0.3,0.1

Type RM Length L Ch R = 1 ,38876.8 ,771.4,768.1,764.1
XS GIS Cut Line= 3
     1789470.513      235830.928     1790217.908      236672.074
     1790207.492      237054.887
#Sta/Elev= 30
       0 1151.65    29.4 1138.79    48.9 1131.82   146.8 1109.37   185.9 1093.93
   215.3 1085.15   244.6 1078.26   283.8 1072.14   313.1 1062.15   322.9  1060.3
  358.551058.818  389.411056.926   518.6  1041.4  541.98 1041.39   596.9 1041.38
  715.331042.574  856.021044.468     910 1044.71  964.311051.242  976.541052.774
     998 1054.32 1025.861053.948 1117.361052.714 1138.821052.341  1164.5  1053.6
  1223.4 1067.13  1243.1 1072.96  1360.9 1135.97  1439.4 1166.37  1508.2 1191.23
#Mann= 12 ,-1 , 0
       0     .12       0  358.55     .06       0  389.41     .12       0
   518.6    .045       0  541.98     .12       0  715.33     .08       0
  856.02     .12       0  964.31     .08       0  976.54    .016       0
 1025.86     .12       0 1117.36     .06       0 1138.82     .12       0
Bank Sta=518.6,541.98
XS Rating Curve= 0 ,0
Exp/Cntr=0.3,0.1