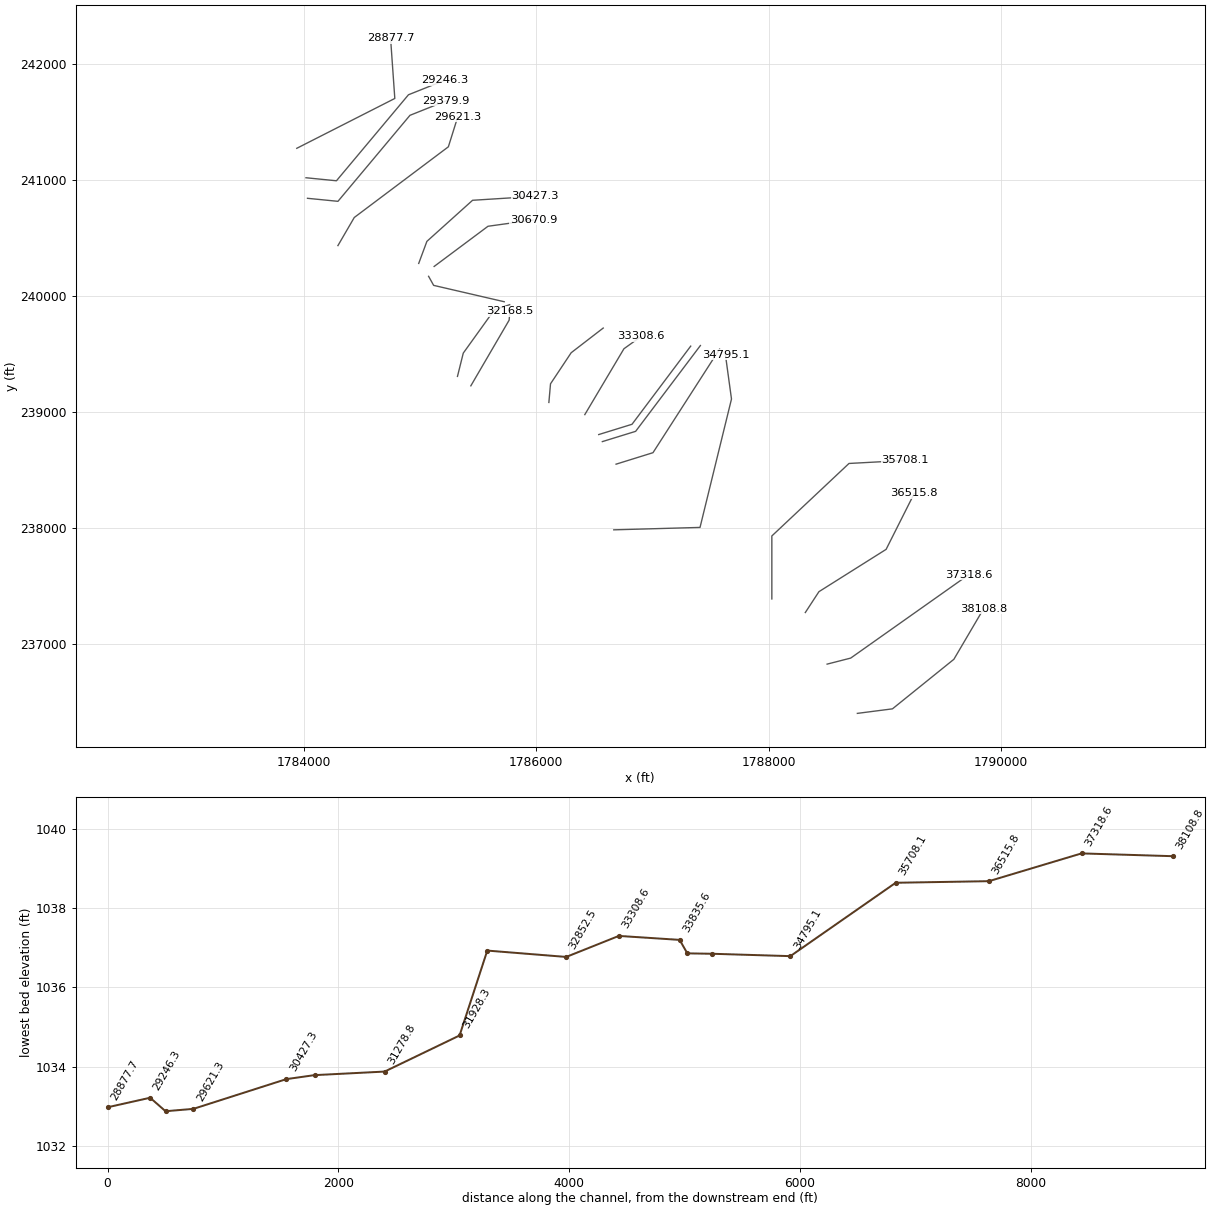
HEC-RAS study ELKCK.prj: ELKCK

--- ELKCK.g01 (geometry) --- (continued)

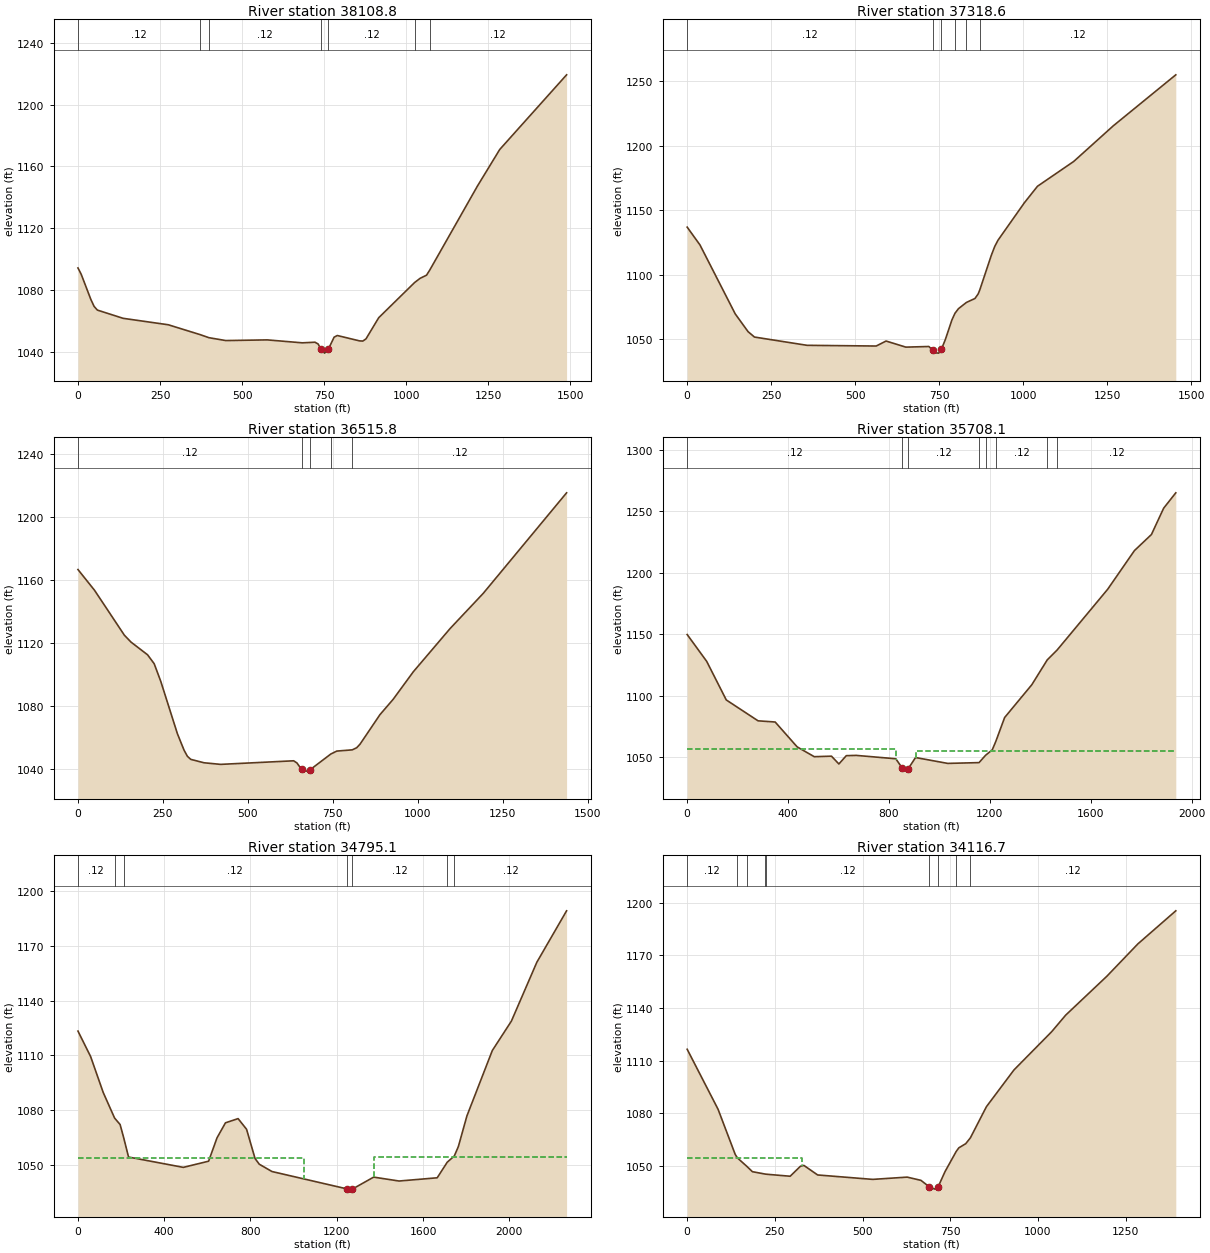
Type RM Length L Ch R = 1 ,38108.8 ,791.2,790.1,789
XS GIS Cut Line= 4
     1788764.783      236401.241     1789066.867      236440.303
     1789595.513      236867.387     1789850.721      237302.283
#Sta/Elev= 30
       0 1094.38     9.8 1090.33    39.3    1074    49.1 1069.54      59 1067.15
   137.6 1061.81   275.1 1057.65  372.441051.252  398.731049.302   450.2 1047.43
   576.4 1047.87   683.2 1045.97   722.1 1046.36   731.8 1045.17     740 1041.81
   751.2 1039.31  763.061042.058   780.3 1049.62     790  1050.7     858 1047.21
   867.7 1047.11   877.4 1048.53   916.2 1062.23 1025.341084.933  1042.4  1087.7
  1061.8 1089.71 1072.081093.187  1216.9 1147.35  1284.8 1170.99  1488.4 1219.26
#Mann= 7 ,-1 , 0
       0     .12       0  372.44     .07       0  398.73     .12       0
     740    .045       0  763.06     .12       0 1025.34    .016       0
 1072.08     .12       0
Bank Sta=740,763.06
XS Rating Curve= 0 ,0
Exp/Cntr=0.3,0.1

Type RM Length L Ch R = 1 ,37318.6 ,805.3,802.9,798.5
XS GIS Cut Line= 3
     1788504.367       236825.72     1788707.492      236877.803
     1789723.117      237596.553
#Sta/Elev= 30
       0 1137.01    38.1 1123.21     143 1069.78   181.1 1056.05   200.2 1051.84
   356.6 1045.43   562.4 1044.88   591.8 1048.75   650.6 1044.03   719.1 1044.51
   731.71041.457   738.7  1039.6   748.5 1039.38   756.71042.466   768.1 1049.82
   787.7 1065.08  796.911070.286   807.3 1073.84  830.961078.667   856.3 1081.72
   866.1 1085.35  871.161088.711   905.3 1115.41   915.1    1122   924.9 1126.89
  1003.3 1155.88  1042.4  1168.7  1150.2 1187.92  1267.8  1215.5  1453.9 1255.05
#Mann= 6 ,-1 , 0
       0     .12       0   731.7    .045       0   756.7     .12       0
  796.91     .08       0  830.96    .016       0  871.16     .12       0
Bank Sta=731.7,756.7
XS Rating Curve= 0 ,0
Exp/Cntr=0.3,0.1

Type RM Length L Ch R = 1 ,36515.8 ,803.2,807.7,811.8
XS GIS Cut Line= 4
     1788316.867      237270.512     1788434.054      237450.199
     1789012.179      237814.783     1789254.367      238296.553
#Sta/Elev= 30
       0 1166.48    48.8 1153.31   136.5 1124.86     156 1120.49   204.8 1112.42
   224.3 1106.73   243.8 1095.43   292.6 1062.33   312.2 1051.89   321.9 1048.09
   331.7 1046.14   370.8 1043.98   419.6 1042.96   634.4 1045.23   644.1 1043.86
   657.6  1039.8   663.7 1038.69   672.6 1038.68   683.2 1039.63  743.831049.544
   761.3 1051.39  806.831052.165   819.9 1053.52   829.7 1055.78   888.2 1074.46
   927.4 1084.29   986.2 1101.62  1094.1 1128.96  1192.1 1151.39  1437.2 1215.12
#Mann= 5 ,-1 , 0
       0     .12       0   657.6    .045       0   683.2     .12       0
  743.83    .016       0  806.83     .12       0
Bank Sta=657.6,683.2
XS Rating Curve= 0 ,0
Exp/Cntr=0.3,0.1

Type RM Length L Ch R = 1 ,35708.1 ,900,913.1,925.9
XS GIS Cut Line= 4
     1788028.672      237387.699     1788028.672      237930.234
     1788692.735      238555.234     1789174.506      238581.276
#Sta/Elev= 30
       0 1149.73    77.5 1127.87     155 1096.53     281 1079.55   348.8 1078.59
     436 1058.35   503.8 1050.38     572  1050.8   601.4 1044.45   630.8 1051.22
     670 1051.44   826.9 1048.69  853.411040.881   866.1 1038.64   875.9  1040.5
   905.3  1049.7  1032.8 1044.92 1156.991045.563 1182.771051.509  1209.3 1055.94
 1223.221062.675  1258.4 1082.23  1366.2 1108.92  1427.31129.095 1466.331137.103
  1666.8 1186.52  1772.9 1217.99  1840.4 1231.09  1888.7 1252.46  1936.9 1264.99
#Mann= 8 ,-1 , 0
       0     .12       0  853.41    .045       0   875.9     .12       0
 1156.99     .08       0 1182.77    .016       0 1223.22     .12       0
  1427.3    .016       0 1466.33     .12       0
#XS Ineff= 2 , 0
          829.72 1056.25  908.15         1055.24
Permanent Ineff=
       F       F
Bank Sta=853.41,875.9
XS Rating Curve= 0 ,0
Exp/Cntr=0.3,0.1

Type RM Length L Ch R = 1 ,34795.1 ,685.8,678.4,670.6
XS GIS Cut Line= 4
     1786668.429      237983.185     1787410.617      238004.019
      1787681.45       239110.79     1787629.367      239490.998
#Sta/Elev= 30
       0 1123.37    58.6 1109.44   117.2  1089.7   169.81075.733   195.4 1072.17
  212.211064.888   234.5 1054.37   488.5 1048.71   605.7 1052.09   644.8 1064.89
   683.9 1073.12   742.5 1075.42   781.8 1069.58   821.1 1053.57   840.7 1050.44
   899.6 1046.43    1247 1036.93  1253.3 1036.79    1272 1036.79  1371.1 1043.37
    1489 1041.23  1665.8    1043 1712.241051.526 1745.181054.966    1764 1060.14
  1803.3 1076.81  1921.3 1112.72  2009.8 1128.84  2127.9 1161.11  2265.7 1189.26
#Mann= 7 ,-1 , 0
       0     .12       0   169.8    .016       0  212.21     .12       0
    1247    .045       0    1272     .12       0 1712.24    .016       0
 1745.18     .12       0
#XS Ineff= 2 , 0
         1047.47 1054.05 1372.55         1054.36
Permanent Ineff=
       F       F
Bank Sta=1247,1272
XS Rating Curve= 0 ,0
Exp/Cntr=0.3,0.1

Type RM Length L Ch R = 1 ,34116.7 ,217.2,214.6,211.3
XS GIS Cut Line= 3
     1786688.105      238549.187     1787005.814      238648.145
      1787578.73      239540.506
#Sta/Elev= 30
       0 1116.53    88.1 1082.34     137 1056.62  143.291054.624   169.61049.918
     186 1046.78  222.65 1045.42  225.92 1045.34   293.6 1044.19     323 1049.89
   332.8 1050.36     372 1044.92   529.1  1042.4   627.3 1043.69   666.6 1041.85
  690.221038.174   705.9 1036.85   715.7 1038.23   735.3 1046.87  766.991058.283
   774.6 1060.38   794.2 1062.73   807.51066.059   853.2  1083.8   931.7 1104.73
  1039.7 1126.62    1079 1135.92  1196.8 1158.16  1285.2 1176.58  1393.2  1195.4
#Mann= 9 ,-1 , 0
       0     .12       0  143.29    .016       0   169.6     .12       0
  222.65     .06       0  225.92     .12       0  690.22    .045       0
   715.7     .12       0  766.99    .016       0   807.5     .12       0
#XS Ineff= 2 , 0
          327.97 1054.36
Permanent Ineff=
       F       F
Bank Sta=690.22,715.7
XS Rating Curve= 0 ,0
Exp/Cntr=0.3,0.1

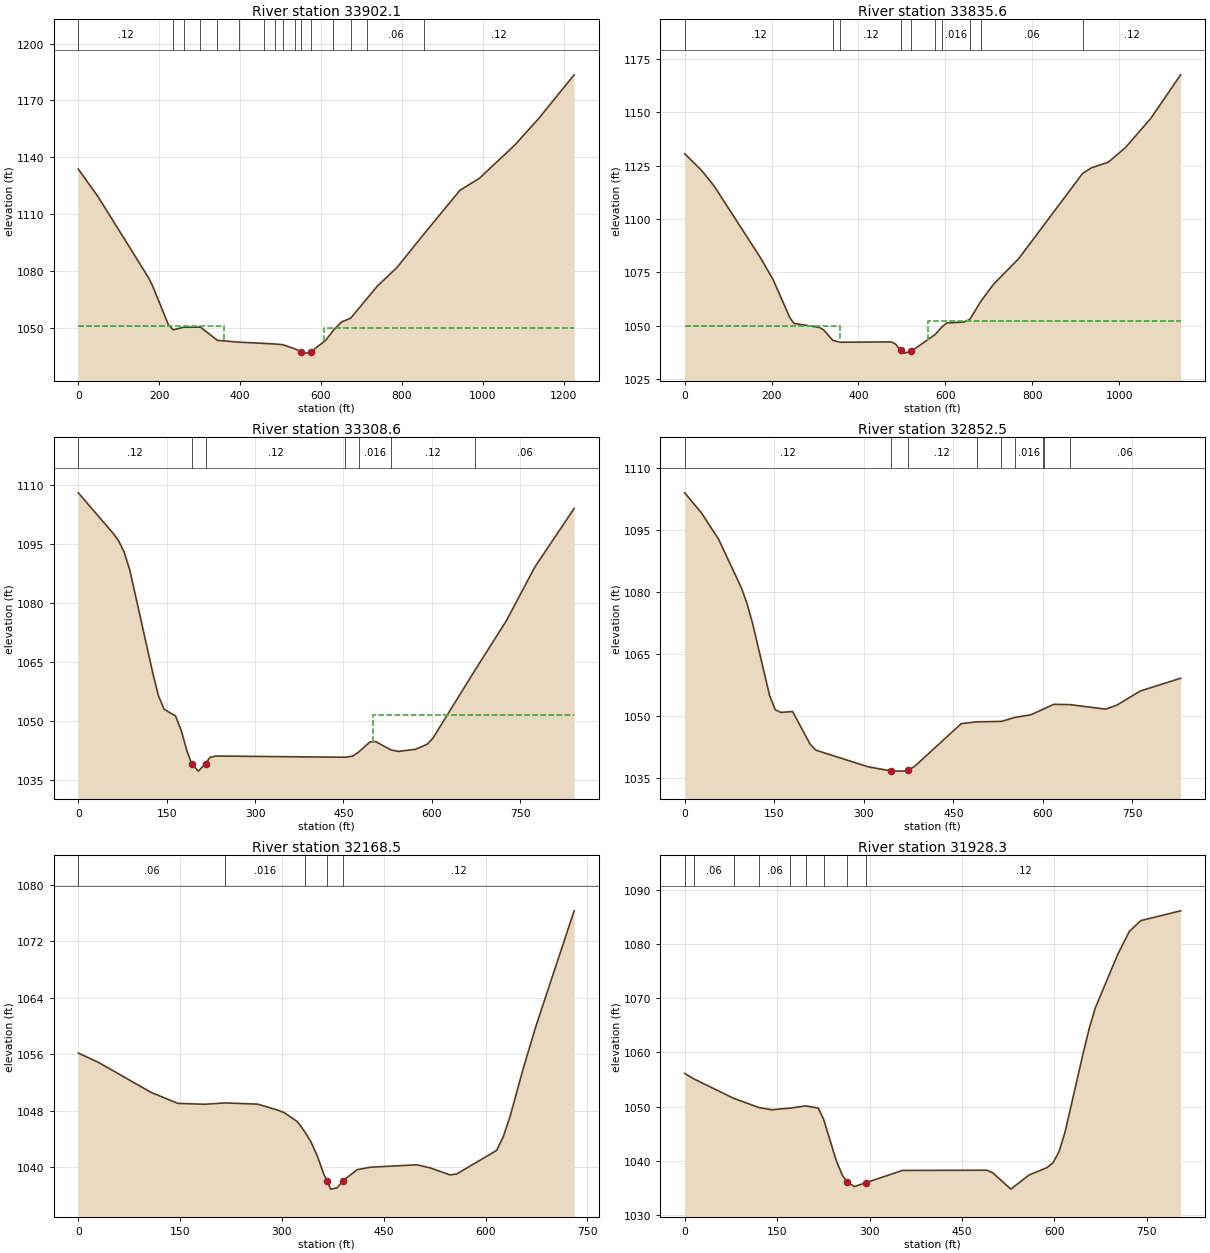
Type RM Length L Ch R = 1 ,33902.1 ,65.7,66.5,68.3
XS GIS Cut Line= 3
      1786570.05      238743.631     1786856.508      238832.173
       1787413.8      239571.756
#Sta/Elev= 30
       0  1133.8    48.4 1119.43   174.1 1076.43   183.8 1072.24   222.4 1051.95
  234.351049.131  260.131050.495  301.891050.561  343.931043.612  396.561042.644
  458.891041.989  486.671041.645  505.651041.307  536.871038.996   549.61037.606
     563 1036.86   574.61037.523   611.8 1043.64  630.291048.839   650.8  1053.3
  673.171055.245  713.621065.578   738.5 1072.01   787.2 1081.85  855.741099.935
   943.2 1122.63   991.9 1129.05  1079.7 1146.62  1138.1 1160.48  1225.9 1183.52
#Mann= 16 ,-1 , 0
       0     .12       0  234.35     .08       0  260.13    .016       0
  301.89     .12       0  343.93    .016       0  396.56     .06       0
  458.89    .016       0  486.67     .12       0  505.65     .06       0
  536.87     .12       0   549.6    .045       0   574.6     .12       0
  630.29    .016       0  673.17     .12       0  713.62     .06       0
  855.74     .12       0
#XS Ineff= 2 , 0
           361.2 1051.01  608.26          1050.1
Permanent Ineff=
       F       F
Bank Sta=549.6,574.6
XS Rating Curve= 0 ,0
Exp/Cntr=0.3,0.1

Type RM Length L Ch R = 1 ,33835.6 ,523.5,527.1,530
XS GIS Cut Line= 3
       1786538.8      238804.395     1786825.258      238892.937
     1787330.466      239566.548
#Sta/Elev= 30
       0 1130.61    38.7 1122.79    67.7 1115.47   174.1 1081.94   203.1 1071.75
   241.8 1053.87   251.5 1051.12   309.6 1049.26   319.4 1048.15  340.841043.192
  357.991042.305   476.1 1042.46   485.9 1041.35   496.81038.456   505.4  1037.2
   521.81038.104  576.821045.996  592.581049.537   603.4 1051.36   642.5 1051.74
  656.581053.068   682.61061.734     711 1069.46   769.8 1081.68  916.041121.382
   936.2 1123.99   975.4 1126.67  1014.6 1133.47  1073.3 1147.23  1141.8 1167.58
#Mann= 10 ,-1 , 0
       0     .12       0  340.84     .06       0  357.99     .12       0
   496.8    .045       0   521.8     .12       0  576.82     .08       0
  592.58    .016       0  656.58     .12       0   682.6     .06       0
  916.04     .12       0
#XS Ineff= 2 , 0
          356.66    1050  559.75         1052.16
Permanent Ineff=
       F       F
Bank Sta=496.8,521.8
XS Rating Curve= 0 ,0
Exp/Cntr=0.3,0.1

Type RM Length L Ch R = 1 ,33308.6 ,452.6,456,455.8
XS GIS Cut Line= 3
     1786419.008       238976.27     1786755.814      239543.978
     1786903.383      239649.881
#Sta/Elev= 30
       0 1108.09    58.2 1097.94      68 1095.96    77.7 1093.06    87.4 1088.44
   126.2  1062.4   135.9 1056.52   145.6 1053.04     165 1051.34   174.7 1047.63
   184.4 1042.46   192.7 1039.07   203.8  1037.3  215.921039.216   223.3 1040.76
     233 1041.14  453.491040.831     466 1041.13  476.251042.207   495.1 1044.73
   504.8 1044.81     5311042.669   543.6 1042.32   572.7 1042.86   592.2 1044.15
   601.9 1045.67  672.63  1062.8     727 1075.65   774.8 1089.17   841.7 1104.13
#Mann= 7 ,-1 , 0
       0     .12       0   192.7    .045       0  215.92     .12       0
  453.49     .08       0  476.25    .016       0     531     .12       0
  672.63     .06       0
#XS Ineff= 2 , 0
                          500.52         1051.62
Permanent Ineff=
       F       F
Bank Sta=192.7,215.92
XS Rating Curve= 0 ,0
Exp/Cntr=0.3,0.1

Type RM Length L Ch R = 1 ,32852.5 ,684.1,684.1,684.8
XS GIS Cut Line= 4
     1786109.734      239081.117      1786123.84      239241.707
     1786301.792      239509.719     1786577.399      239722.393
#Sta/Elev= 30
       0 1104.06    28.4  1099.1    56.9 1092.78    94.8  1081.1   104.3 1077.29
   113.8 1072.38   142.2 1055.01   151.7 1051.59   161.2 1050.96   180.7 1051.18
     210  1043.3   219.7 1041.84   307.4 1037.81   346.4 1036.81   365.9 1036.77
   373.6 1036.95   385.4 1037.94   463.4 1048.26  488.921048.685  530.721048.797
  554.031049.781   579.6 1050.38  601.031051.751  601.961051.824   618.3 1052.92
  644.941052.859   705.3 1051.76   724.7 1052.77   763.4 1056.14     831 1059.23
#Mann= 9 ,-1 , 0
       0     .12       0   346.4    .045       0   373.6     .12       0
  488.92    .016       0  530.72     .12       0  554.03    .016       0
  601.03     .08       0  601.96    .016       0  644.94     .06       0
Bank Sta=346.4,373.6
XS Rating Curve= 0 ,0
Exp/Cntr=0.3,0.1

Type RM Length L Ch R = 1 ,32168.5 ,243.4,240.1,234.9
XS GIS Cut Line= 3
     1785438.076      239224.346     1785767.937      239790.752
     1785773.363      239865.622
#Sta/Elev= 30
       0 1056.17    29.4 1054.87   107.6 1050.59   146.7 1049.06   185.9 1048.93
  216.041049.125   264.1 1048.95   293.5 1048.11   303.3 1047.75   322.8 1046.47
  333.81 1045.02   342.4 1043.67   352.2  1041.6     362 1038.96   366.4 1038.05
   371.8 1036.93   381.4 1037.11  389.481038.098   410.9 1039.68   430.4 1040.03
   498.9 1040.37   518.5 1039.93   547.8 1038.94   557.6 1039.08   616.3 1042.41
   626.1 1044.36   635.9 1047.15   655.5    1054   674.2 1059.98   730.5 1076.29
#Mann= 5 ,-1 , 0
       0     .06       0  216.04    .016       0  333.81     .12       0
   366.4    .045       0  389.48     .12       0
Bank Sta=366.4,389.48
XS Rating Curve= 0 ,0
Exp/Cntr=0.3,0.1

Type RM Length L Ch R = 1 ,31928.3 ,675.5,649.5,625
XS GIS Cut Line= 4
     1785323.059      239305.726     1785372.972      239506.464
     1785640.796      239879.641     1785772.414      239923.801
#Sta/Elev= 30
       0 1056.13   14.591055.137   79.251051.552  119.891049.861     141 1049.43
   171.21049.738     1961050.151   216.6 1049.74  225.241047.712   245.9 1040.07
   255.7 1037.37  263.411036.127   275.3 1035.26   294.8 1036.01   353.4 1038.24
   490.3 1038.28     500 1037.79   529.4 1034.79   558.7 1037.38     588 1038.76
   597.8 1039.65   607.6 1041.69   617.3  1045.3   646.6 1059.78   656.4 1064.34
   666.2 1068.15   703.2 1078.18   721.7 1082.33   740.2 1084.33     805 1086.14
#Mann= 9 ,-1 , 0
       0    .016       0   14.59     .06       0   79.25     .05       0
  119.89     .06       0   171.2     .08       0     196     .06       0
  225.24     .12       0  263.41    .045       0   294.8     .12       0
Bank Sta=263.41,294.8
XS Rating Curve= 0 ,0
Exp/Cntr=0.3,0.1

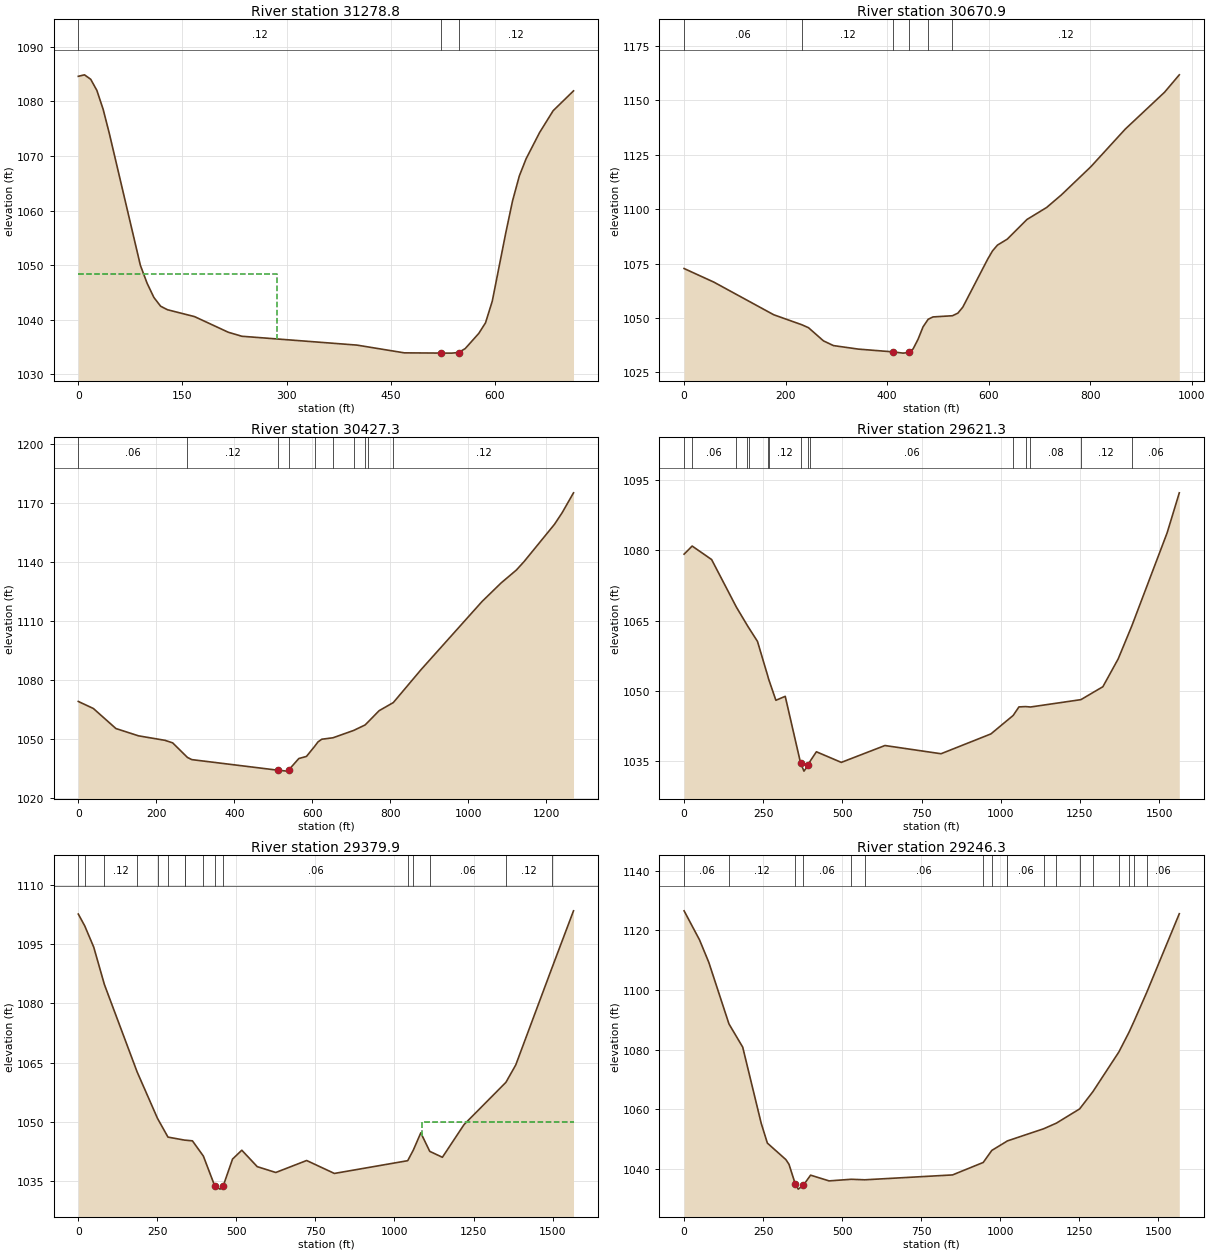
Type RM Length L Ch R = 1 ,31278.8 ,588.1,607.9,627.6
XS GIS Cut Line= 3
     1785074.578      240168.356     1785117.981      240090.231
      1785725.62      239949.172
#Sta/Elev= 30
       0 1084.59     8.9 1084.86    17.9 1084.04    26.8 1081.99    35.8 1078.54
    44.7 1074.11    89.4 1049.97    99.1 1046.68   108.9 1044.07   118.6 1042.47
   128.4 1041.83   167.4 1040.57   216.1  1037.7   235.6 1036.97   401.3 1035.35
   469.5 1033.93   522.7 1033.89   537.7 1033.88   547.71033.995   557.2 1034.71
   576.7 1037.48   586.5 1039.44   596.2  1043.4   615.7 1055.94   625.4 1061.77
   635.2 1066.35   644.9 1069.48   664.4  1074.3   683.9 1078.29   713.2 1081.92
#Mann= 3 ,-1 , 0
       0     .12       0   522.7    .045       0   547.7     .12       0
#XS Ineff= 2 , 0
          286.48 1048.45
Permanent Ineff=
       F       F
Bank Sta=522.7,547.7
XS Rating Curve= 0 ,0
Exp/Cntr=0.3,0.1

Type RM Length L Ch R = 1 ,30670.9 ,244.5,243.6,245.6
XS GIS Cut Line= 3
     1785122.292      240253.324     1785585.834      240599.678
     1785979.063      240654.366
#Sta/Elev= 30
       0  1072.7    58.8 1066.43   176.5 1051.45  232.341046.811   245.2 1045.47
   274.6 1039.43   294.2 1037.26   343.3 1035.64   411.9 1034.36   431.5 1033.79
   442.61034.096   451.2 1035.72     461 1040.18   470.8 1045.87   480.91049.354
   490.4 1050.44  528.761050.987   539.4 1052.18   549.2 1054.96     598 1076.94
   607.7 1080.82   617.4 1083.47   636.8 1086.22   675.5 1095.25   714.2 1100.76
   743.3 1106.55   801.4 1119.52   869.1  1136.8   946.6 1153.78   975.7 1161.79
#Mann= 6 ,-1 , 0
       0     .06       0  232.34     .12       0   411.9    .045       0
   442.6     .12       0   480.9    .016       0  528.76     .12       0
Bank Sta=411.9,442.6
XS Rating Curve= 0 ,0
Exp/Cntr=0.3,0.1

Type RM Length L Ch R = 1 ,30427.3 ,804.6,806,804.5
XS GIS Cut Line= 4
      1784989.48      240279.366     1785059.792       240469.47
     1785453.021      240823.637      1785989.48      240857.491
#Sta/Elev= 30
       0 1069.15    38.6 1065.57    96.5 1055.36   154.4 1051.65   222.3 1049.36
   241.9 1048.07  279.651040.682   290.9 1039.55   511.81034.152   535.9 1033.69
  539.481034.318   565.3  1040.1   584.9 1041.18  606.051046.351   614.3 1048.54
   624.1 1049.92  652.931050.668  705.761054.393  735.05 1057.17  742.121058.568
     771 1064.43  807.481068.581   878.5 1085.32  1034.9 1120.01  1083.7 1129.44
  1122.8 1136.01  1142.4 1140.27  1220.6  1159.3  1240.1 1165.15  1269.4 1175.33
#Mann= 10 ,-1 , 0
       0     .06       0  279.65     .12       0   511.8    .045       0
  539.48     .12       0  606.05    .016       0  652.93     .08       0
  705.76     .06       0  735.05     .08       0  742.12    .016       0
  807.48     .12       0
Bank Sta=511.8,539.48
XS Rating Curve= 0 ,0
Exp/Cntr=0.3,0.1

Type RM Length L Ch R = 1 ,29621.3 ,235.7,241.3,246.8
XS GIS Cut Line= 4
     1784294.167      240433.012     1784434.792      240675.199
     1785244.688      241284.574     1785325.417      241542.387
#Sta/Elev= 30
       0 1079.12   25.461080.852    86.9 1077.98  165.211067.843  199.051064.024
   203.61063.525   231.8 1060.55  264.161053.217  266.711052.581   289.9 1048.02
   319.4 1048.86   367.81034.691   378.5 1032.94   392.81034.227  396.481034.896
   417.8 1037.06   496.5  1034.8   634.3 1038.39   811.4 1036.64   968.9 1040.86
 1039.251044.795  1057.4 1046.61 1078.331046.677 1093.83 1046.59 1253.031048.155
  1322.5 1050.91  1370.8 1056.83 1413.731063.831  1525.2 1083.63  1563.8 1092.18
#Mann= 15 ,-1 , 0
       0     .12       0   25.46     .06       0  165.21     .05       0
  199.05      .1       0   203.6     .12       0  264.16     .08       0
  266.71     .12       0   367.8    .045       0   392.8     .12       0
  396.48     .06       0 1039.25    .016       0 1078.33     .06       0
 1093.83     .08       0 1253.03     .12       0 1413.73     .06       0
Bank Sta=367.8,392.8
XS Rating Curve= 0 ,0
Exp/Cntr=0.3,0.1

Type RM Length L Ch R = 1 ,29379.9 ,133.6,133.6,133.6
XS GIS Cut Line= 4
     1784032.304      240840.709     1784294.456      240814.667
     1784914.248      241555.986     1785226.748      241680.986
#Sta/Elev= 30
       0 1102.66   20.281099.671    48.8 1094.28   82.511084.795  185.891062.651
   250.61050.815  283.641046.077  337.051045.301  338.011045.303     361 1045.13
  395.61 1041.26  431.311033.734   448.3 1032.88   458.6 1033.76   487.9 1040.51
   517.2 1042.75     566 1038.58   624.6  1037.1   722.2 1040.14     810 1036.86
 1041.881040.097 1059.59 1042.78  1083.3 1047.16 1111.62 1042.46  1151.6 1040.96
    1220 1049.25 1352.47 1059.97  1383.6 1064.38 1498.551089.085  1566.3 1103.48
#Mann= 16 ,-1 , 0
       0     .12       0   20.28     .06       0   82.51     .12       0
  185.89    .016       0   250.6     .05       0  283.64     .06       0
  337.05     .08       0  338.01    .016       0  395.61     .12       0
  431.31    .045       0   458.6     .06       0 1041.88     .08       0
 1059.59    .016       0 1111.62     .06       0 1352.47     .12       0
 1498.55    .016       0
#XS Ineff= 2 , 0
                         1088.13            1050
Permanent Ineff=
       F       F
Bank Sta=431.31,458.6
XS Rating Curve= 0 ,0
Exp/Cntr=0.3,0.1

Type RM Length L Ch R = 1 ,29246.3 ,377.8,368.6,359.5
XS GIS Cut Line= 4
     1784019.283      241017.792     1784281.436       240991.75
     1784901.227       241733.07     1785213.727       241858.07
#Sta/Elev= 30
       0 1126.49    48.8 1116.76    78.1 1109.24  141.951088.586   185.4 1080.81
   243.9 1055.29   263.4 1048.65     322 1043.11   331.8 1041.54   351.71034.936
     361 1033.22   376.71034.444   400.1  1037.9   458.6 1035.98  529.051036.522
  571.481036.346   849.1 1037.98  946.141042.158  973.291046.199 1020.28 1049.22
 1022.091049.364 1137.371053.453 1177.521055.337 1251.091060.103 1293.131065.901
 1375.22  1079.2 1407.251085.794 1423.161089.485 1463.681099.248  1566.3 1125.52
#Mann= 18 ,-1 , 0
       0     .06       0  141.95     .12       0   351.7    .045       0
   376.7     .06       0  529.05     .12       0  571.48     .06       0
  946.14     .08       0  973.29    .016       0 1020.28     .08       0
 1022.09     .06       0 1137.37     .12       0 1177.52     .06       0
 1251.09    .016       0 1293.13     .06       0 1375.22     .12       0
 1407.25     .08       0 1423.16     .12       0 1463.68     .06       0
Bank Sta=351.7,376.7
XS Rating Curve= 0 ,0
Exp/Cntr=0.3,0.1

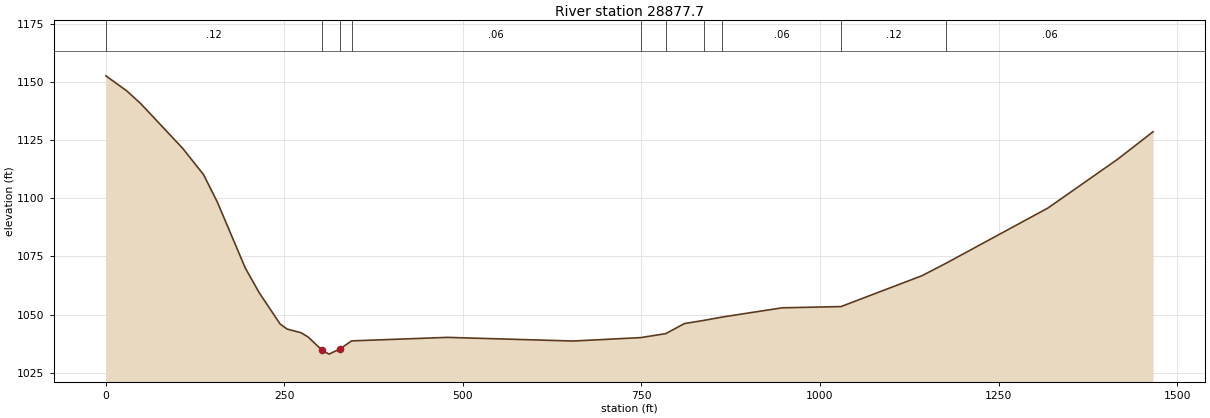
Type RM Length L Ch R = 1 ,28877.7 ,493.6,495.5,497.3
XS GIS Cut Line= 3
        1783940.      241271.553      1784783.75      241701.241
     1784747.292       242219.47
#Sta/Elev= 30
       0 1152.56    29.3 1146.07    48.8 1140.61   107.4 1121.45   136.7 1110.14
   156.2 1098.22   195.2 1069.99   214.8 1059.31     244 1045.93   253.8 1043.75
   273.3 1042.17   283.1 1040.36   302.6 1034.71   312.4 1032.98   327.61035.177
  344.121038.672   478.3 1040.18     654 1038.61  748.951040.075  784.071041.789
   810.2 1046.12  836.981047.451  863.411048.926   946.9 1052.88  1029.41053.409
  1142.9 1066.69 1176.951072.097  1319.3 1095.78  1417.4 1116.85  1466.4 1128.54
#Mann= 10 ,-1 , 0
       0     .12       0   302.6    .045       0   327.6     .12       0
  344.12     .06       0  748.95     .12       0  784.07    .016       0
  836.98     .08       0  863.41     .06       0  1029.4     .12       0
 1176.95     .06       0
Bank Sta=302.6,327.6
XS Rating Curve= 0 ,0
Exp/Cntr=0.3,0.1