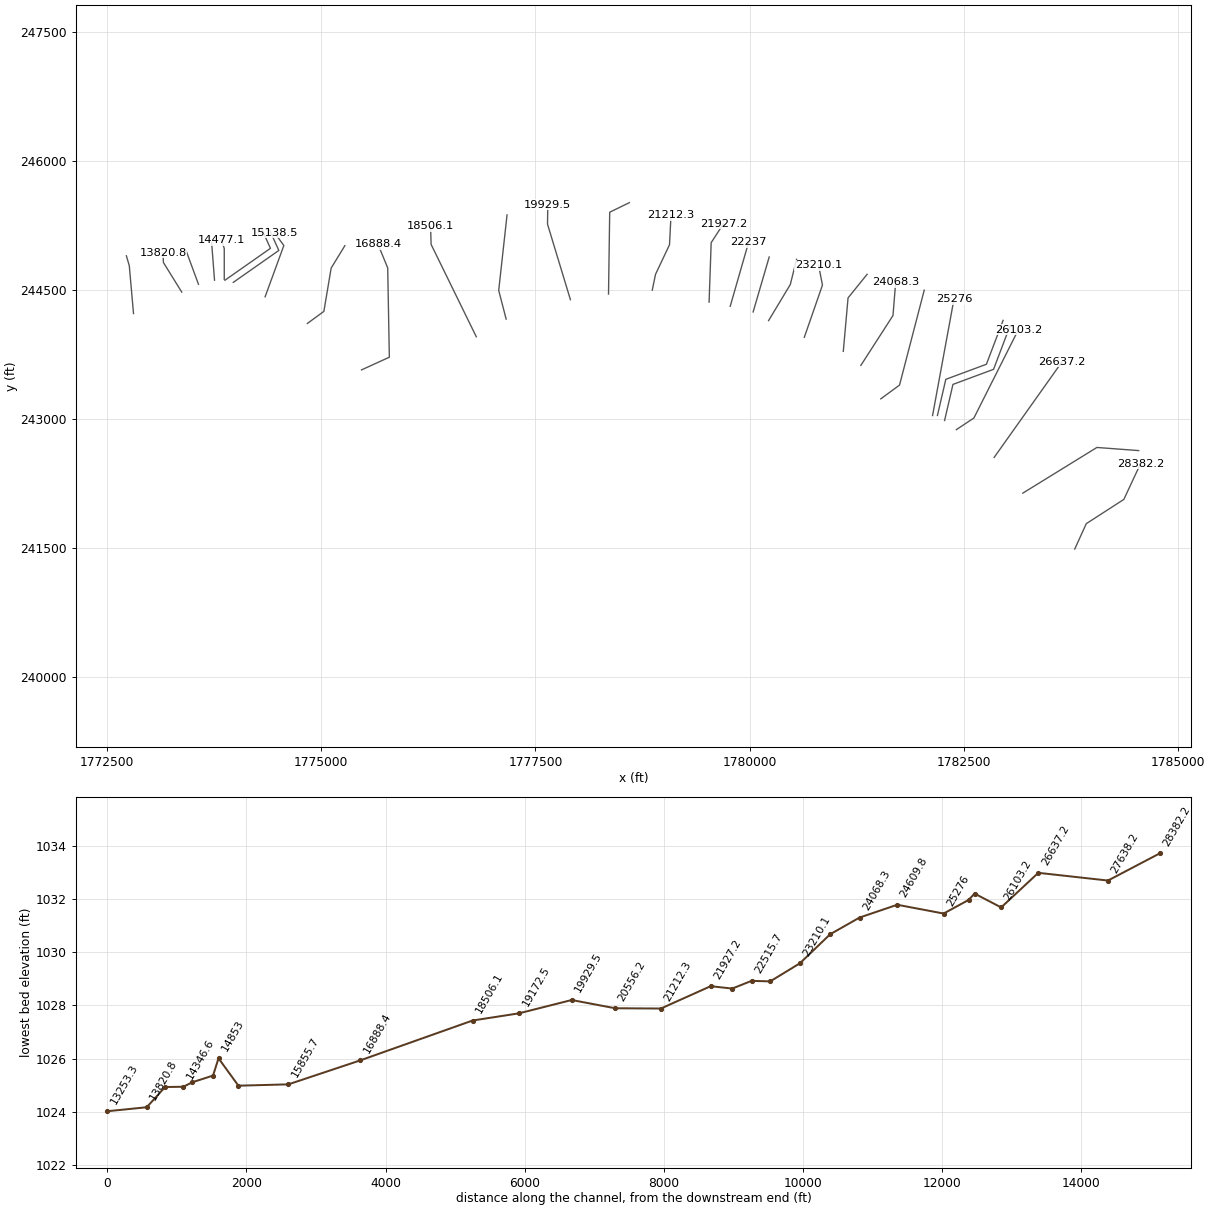
HEC-RAS study ELKCK.prj: ELKCK

--- ELKCK.g01 (geometry) --- (continued)

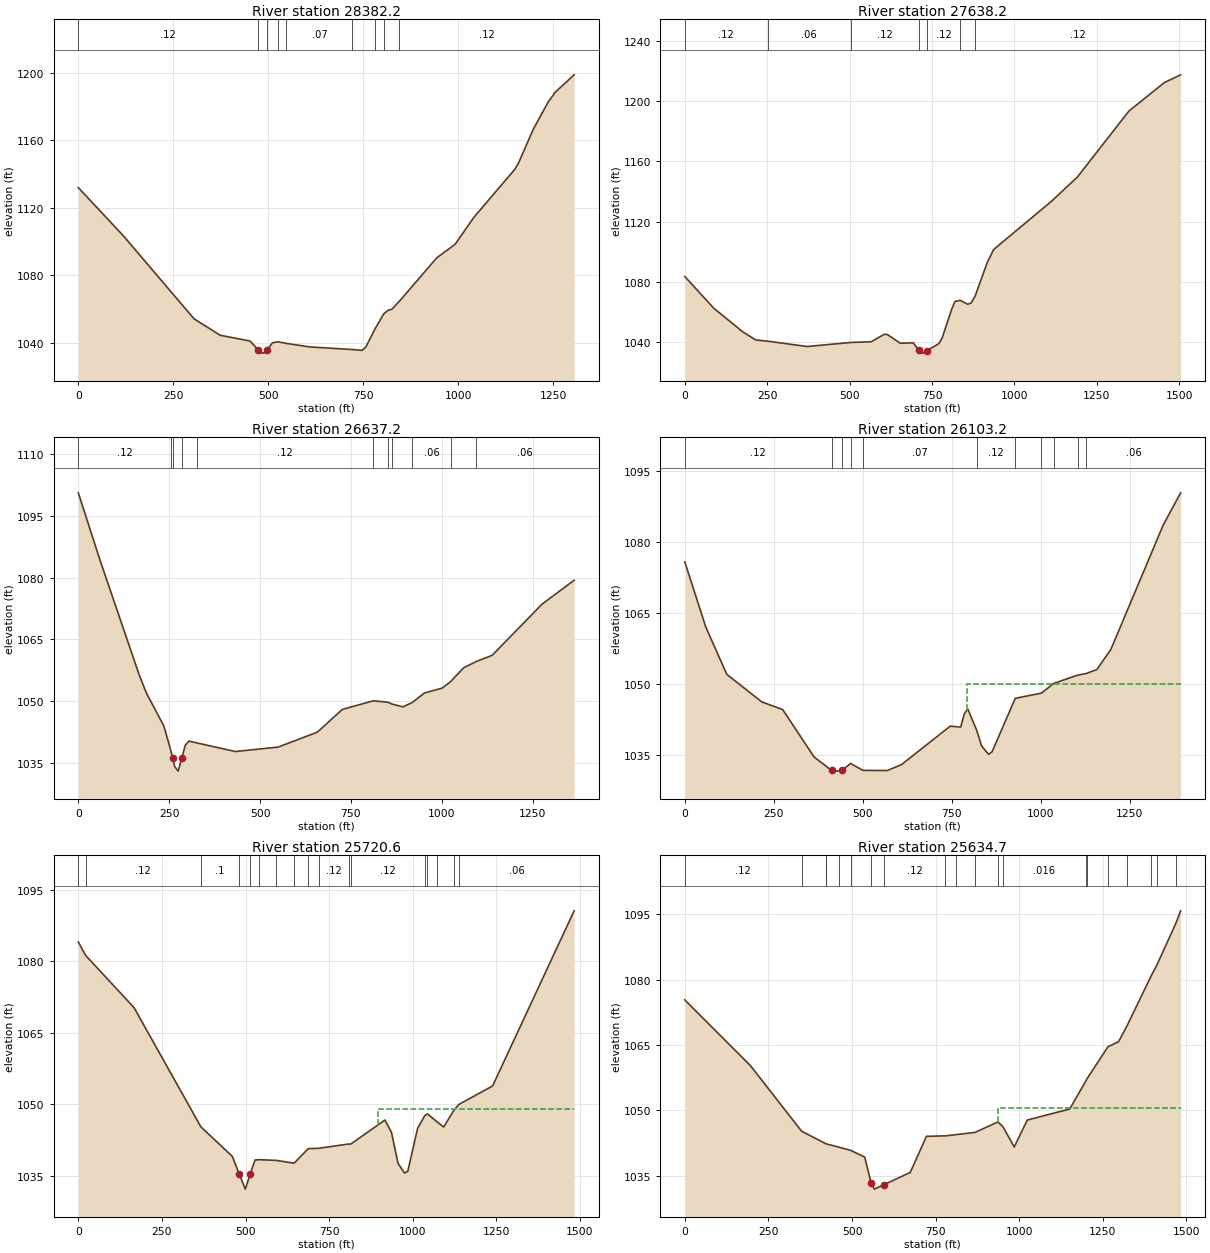
Type RM Length L Ch R = 1 ,28382.2 ,744.6,744,743.3
XS GIS Cut Line= 4
     1783793.444      241482.346     1783927.992      241777.485
      1784366.36      242059.603     1784561.673       242476.27
#Sta/Elev= 30
       0  1131.9     118 1103.46   304.7 1054.09   373.5 1044.31   452.2 1040.89
  473.761035.711   481.7 1033.71   491.6 1033.94  497.771035.845   511.2 1039.82
  525.361040.462  547.721039.489   609.6 1037.38  721.751035.841   747.3 1035.37
   757.1  1037.3  780.731047.814   804.21056.979   816.2 1059.19     826 1059.74
  845.461064.482   943.6 1090.15   992.5 1098.33  1041.5 1114.18  1149.2 1142.68
    1159 1146.36  1198.1 1166.47  1237.3 1182.63  1256.9 1188.68  1305.8  1198.8
#Mann= 9 ,-1 , 0
       0     .12       0  473.76    .045       0  497.77     .12       0
  525.36     .06       0  547.72     .07       0  721.75     .12       0
  780.73     .08       0   804.2    .016       0  845.46     .12       0
Bank Sta=473.76,497.77
XS Rating Curve= 0 ,0
Exp/Cntr=0.3,0.1

Type RM Length L Ch R = 1 ,27638.2 ,991.2,1001.1,1010.1
XS GIS Cut Line= 3
     1783187.541       242132.52     1784052.124       242663.77
     1784539.972      242627.312
#Sta/Elev= 30
       0 1083.57    87.8 1062.53   175.6 1046.88   214.7 1041.47   251.81040.613
   370.8 1037.09   503.21039.761   565.9 1040.28     605 1045.21   614.7 1045.03
   653.7 1039.25   692.8 1039.54   709.41034.675     722 1032.69   734.41034.309
   770.8 1039.05   780.6 1042.72   809.8 1062.02   819.6 1067.01  835.161067.727
   858.6 1065.13   868.4    1066  881.091070.797   917.2 1092.77   936.7 1101.47
  1112.6  1133.6  1190.9 1149.65  1347.4  1193.5    1455 1212.41    1504 1217.52
#Mann= 7 ,-1 , 0
       0     .12       0   251.8     .06       0   503.2     .12       0
   709.4    .045       0   734.4     .12       0  835.16    .016       0
  881.09     .12       0
Bank Sta=709.4,734.4
XS Rating Curve= 0 ,0
Exp/Cntr=0.3,0.1

Type RM Length L Ch R = 1 ,26637.2 ,530.4,534,537.5
XS GIS Cut Line= 2
      1782853.05      242548.029     1783644.717       243659.14
#Sta/Elev= 30
       0 1100.65    58.9 1084.48   166.9 1056.53   186.5 1052.11   235.6  1043.9
  254.391038.008  259.711036.056     265 1034.12   274.8 1032.98   284.6 1036.16
   294.4  1039.3   304.3 1040.29  326.091039.842   431.9 1037.75   549.6 1038.82
   657.6 1042.45   726.3 1047.98  811.32 1050.07  851.421049.743  863.811049.276
   893.2 1048.61  918.741049.664   952.1 1051.97  1001.1 1053.17 1024.171054.725
    1060 1058.09 1094.871059.633  1138.6 1061.14    1276 1073.58  1364.3  1079.4
#Mann= 11 ,-1 , 0
       0     .12       0  254.39     .08       0  259.71    .045       0
   284.6     .06       0  326.09     .12       0  811.32     .06       0
  851.42     .08       0  863.81    .016       0  918.74     .06       0
 1024.17     .12       0 1094.87     .06       0
Bank Sta=259.71,284.6
XS Rating Curve= 0 ,0
Exp/Cntr=0.3,0.1

Type RM Length L Ch R = 1 ,26103.2 ,399.6,382.6,365.5
XS GIS Cut Line= 3
     1782412.078      242870.946     1782616.939      243006.362
       1783134.3      244030.668
#Sta/Elev= 30
       0 1075.85    58.9 1062.11   117.9 1052.12   216.1  1046.3     275 1044.68
   363.3 1034.66   412.3 1031.84   427.6 1031.68   441.7 1031.86  465.92  1033.3
  500.741031.838   569.2 1031.81   608.5 1033.04   745.8 1041.17   775.2 1040.98
     785  1043.7   794.8 1044.85  819.831040.374   834.1 1036.96   853.7 1035.23
   863.5 1035.78  928.421047.043 1002.11 1048.15 1036.391050.187 1103.581051.935
 1127.621052.274  1157.7 1053.12    1197 1057.34  1344.1 1083.61  1393.1 1090.42
#Mann= 11 ,-1 , 0
       0     .12       0   412.3    .045       0   441.7     .06       0
  465.92     .12       0  500.74     .07       0  819.83     .12       0
  928.42     .06       0 1002.11    .016       0 1036.39     .06       0
 1103.58     .12       0 1127.62     .06       0
#XS Ineff= 2 , 0
                          793.19         1049.98
Permanent Ineff=
       F       F
Bank Sta=412.3,441.7
XS Rating Curve= 0 ,0
Exp/Cntr=0.3,0.1

Type RM Length L Ch R = 1 ,25720.6 ,85.6,85.9,85.9
XS GIS Cut Line= 4
     1782274.708      242977.066     1782372.364      243396.987
     1782846.106      243572.335      1783040.55      244082.751
#Sta/Elev= 30
       0    1084   21.621081.209   166.6 1070.24  366.331045.265   460.3 1039.07
  481.161035.387   499.1  1032.2  514.111035.385   528.3  1038.3  541.621038.369
  592.27 1038.22  645.181037.635  687.351040.685  719.041040.759  808.071041.656
  814.121041.627   916.8 1046.68   936.3 1044.11   955.8 1037.62   975.3 1035.57
     985 1035.91  1014.3 1044.92 1035.691047.593  1043.91047.974 1071.94 1046.34
  1092.3 1045.22 1122.461048.673 1138.141049.967  1238.6 1053.82  1482.5 1090.53
#Mann= 17 ,-1 , 0
       0      .1       0   21.62     .12       0  366.33      .1       0
  481.16    .045       0  514.11      .1       0  541.62    .016       0
  592.27      .1       0  645.18    .016       0  687.35      .1       0
  719.04     .12       0  808.07      .1       0  814.12     .12       0
 1035.69     .08       0  1043.9     .06       0 1071.94    .016       0
 1122.46     .08       0 1138.14     .06       0
#XS Ineff= 2 , 0
                          896.59         1048.92
Permanent Ineff=
       F       F
Bank Sta=481.16,514.11
XS Rating Curve= 0 ,0
Exp/Cntr=0.3,0.1

Type RM Length L Ch R = 1 ,25634.7 ,335.5,358.7,382.2
XS GIS Cut Line= 4
     1782191.375      243036.093     1782289.031      243456.015
     1782762.772      243631.362     1782957.217      244141.779
#Sta/Elev= 30
       0 1075.34     196  1060.3  349.051045.258  421.361042.378  422.471042.341
  460.871041.589  495.871040.857     538  1039.3   557.4 1033.28   567.1 1031.96
   596.3 1033.01     674 1035.78   722.6 1044.07  777.811044.168   809.51044.442
  867.841044.964  936.28 1047.37  951.191046.271     985 1041.63  1024.1  1047.8
  1150.9 1050.33 1198.511056.674 1201.691057.153 1265.311064.608  1297.2 1065.78
 1321.621069.307  1394.7 1080.89 1411.141083.284  1467.71092.806  1482.5 1095.77
#Mann= 20 ,-1 , 0
       0     .12       0  349.05     .06       0  421.36      .1       0
  422.47     .12       0  460.87     .06       0  495.87     .12       0
   557.4    .045       0   596.3     .12       0  777.81     .06       0
   809.5     .08       0  867.84    .016       0  936.28      .1       0
  951.19    .016       0 1198.51     .08       0 1201.69    .016       0
 1265.31     .08       0 1321.62     .06       0  1394.7     .08       0
 1411.14     .06       0  1467.7     .12       0
#XS Ineff= 2 , 0
                          937.87         1050.46
Permanent Ineff=
       F       F
Bank Sta=557.4,596.3
XS Rating Curve= 0 ,0
Exp/Cntr=0.3,0.1

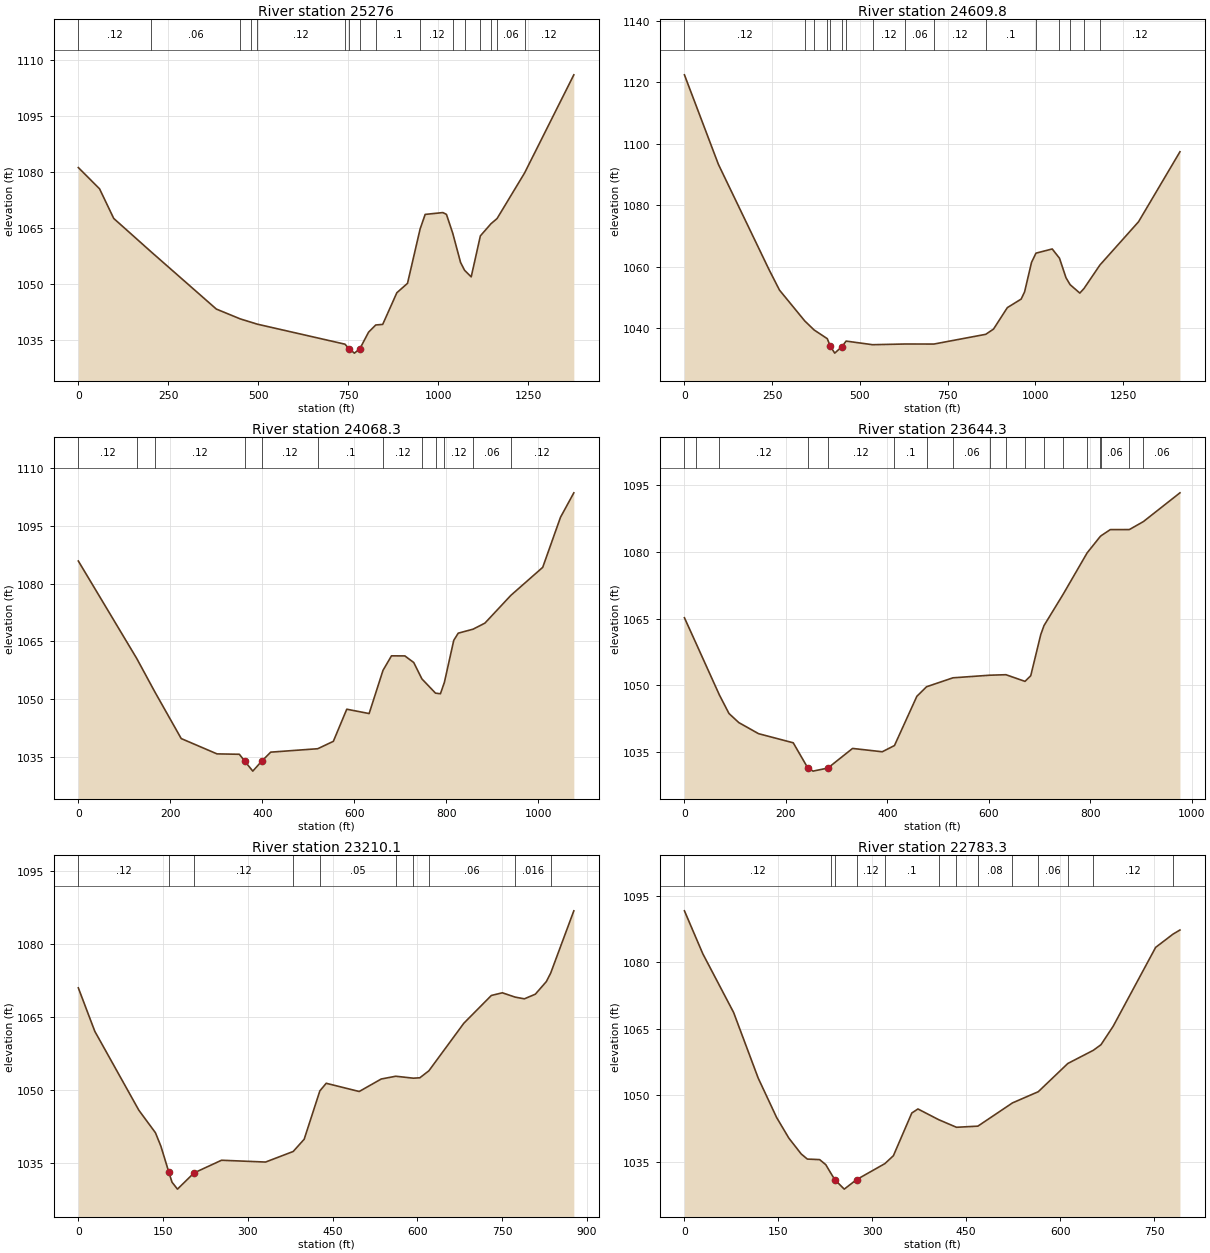
Type RM Length L Ch R = 1 ,25276   ,666.5,666.2,663.7
XS GIS Cut Line= 2
     1782134.445      243034.864     1782384.445       244389.03
#Sta/Elev= 30
       0 1081.24      59 1075.54    98.4 1067.59  202.981058.576   383.6 1043.27
  449.831040.641  479.781039.747  497.521039.217  740.961033.851   752.11032.658
   767.2 1031.45   782.11032.579   806.6 1037.07  826.511038.999   845.9 1039.16
   885.2 1047.66   914.8 1050.17   949.81064.752   963.9 1068.67  1013.1 1069.16
    1023 1068.68 1040.391063.652  1062.3 1055.77  1073.31053.696  1091.8 1051.91
 1117.261062.899 1146.661066.161 1163.64 1067.55  1240.21079.796    1377 1106.12
#Mann= 16 ,-1 , 0
       0     .12       0  202.98     .06       0  449.83     .05       0
  479.78     .06       0  497.52     .12       0  740.96     .08       0
   752.1    .045       0   782.1     .12       0  826.51      .1       0
   949.8     .12       0 1040.39     .08       0  1073.3    .016       0
 1117.26     .06       0 1146.66     .12       0 1163.64     .06       0
  1240.2     .12       0
Bank Sta=752.1,782.1
XS Rating Curve= 0 ,0
Exp/Cntr=0.3,0.1

Type RM Length L Ch R = 1 ,24609.8 ,548.9,541.4,534.1
XS GIS Cut Line= 3
     1781530.278      243229.308     1781749.028       243389.03
     1782037.223      244493.197
#Sta/Elev= 30
       0 1122.46    96.7 1093.31   241.8 1058.82   270.9 1052.31  342.891042.265
  369.591039.321  407.041036.488  415.971033.951   428.3 1031.78   448.61033.879
  460.781035.701  536.051034.525  628.461034.749  710.951034.739  858.551037.908
   880.8 1039.62   920.1  1046.6   959.5 1049.39   969.3 1051.74     989 1061.33
 1001.671064.351    1048 1065.72 1068.751062.706  1087.4 1056.31 1099.151054.067
  1126.7 1051.34 1138.56 1052.84 1184.161060.522    1294 1074.58    1412 1097.39
#Mann= 16 ,-1 , 0
       0     .12       0  342.89      .1       0  369.59     .12       0
  407.04     .08       0  415.97    .045       0   448.6     .08       0
  460.78     .06       0  536.05     .12       0  628.46     .06       0
  710.95     .12       0  858.55      .1       0 1001.67     .12       0
 1068.75     .08       0 1099.15    .016       0 1138.56     .06       0
 1184.16     .12       0
Bank Sta=415.97,448.6
XS Rating Curve= 0 ,0
Exp/Cntr=0.3,0.1

Type RM Length L Ch R = 1 ,24068.3 ,412.9,424.1,434.9
XS GIS Cut Line= 3
     1781297.639      243618.197     1781672.639      244198.058
     1781703.889      244583.475
#Sta/Elev= 30
       0 1085.91  127.151060.545  166.621051.835   223.7 1039.76   301.5 1035.78
   350.1 1035.68     3621033.864   379.3  1031.3   398.8  1033.9   418.2 1036.23
  520.461037.122   554.4 1039.04   583.6 1047.39   632.2 1046.26  662.34 1057.48
   680.8 1061.26   709.9 1061.24   729.2 1059.52   746.91055.271   776.51051.562
   787.2 1051.41  795.821054.369   816.2  1065.3   825.9 1067.15  858.081068.182
   883.9 1069.76  940.331076.978  1009.6 1084.26  1048.2 1097.26  1077.2 1103.62
#Mann= 12 ,-1 , 0
       0     .12       0  127.15      .1       0  166.62     .12       0
     362    .045       0   398.8     .12       0  520.46      .1       0
  662.34     .12       0   746.9     .08       0   776.5    .016       0
  795.82     .12       0  858.08     .06       0  940.33     .12       0
Bank Sta=362,398.8
XS Rating Curve= 0 ,0
Exp/Cntr=0.3,0.1

Type RM Length L Ch R = 1 ,23644.3 ,439.7,434.2,428.5
XS GIS Cut Line= 3
     1781092.778      243781.391     1781148.334      244402.919
     1781370.556      244677.225
#Sta/Elev= 30
       0 1065.21   22.781059.472   68.811047.846    87.8 1043.65   107.2  1041.6
   146.2  1039.1   214.5 1037.05     243 1031.43   253.5 1030.67   282.8 1031.36
   331.5 1035.78     390 1035.03  414.081036.426   458.2 1047.51  477.391049.671
  529.421051.681   602.2 1052.27   633.91052.381  671.411050.885   682.8 1052.15
   702.5  1061.4  708.931063.441  746.441070.448  793.981079.816  819.731083.494
  821.471083.676   839.7 1085.06  877.161085.063  904.851086.857     977 1093.34
#Mann= 18 ,-1 , 0
       0     .12       0   22.78      .1       0   68.81     .12       0
     243    .045       0   282.8     .12       0  414.08      .1       0
  477.39     .05       0  529.42     .06       0   602.2     .08       0
   633.9    .016       0  671.41     .12       0  708.93      .1       0
  746.44     .12       0  793.98     .06       0  819.73     .12       0
  821.47     .06       0  877.16     .05       0  904.85     .06       0
Bank Sta=243,282.8
XS Rating Curve= 0 ,0
Exp/Cntr=0.3,0.1

Type RM Length L Ch R = 1 ,23210.1 ,431.5,426.8,421.8
XS GIS Cut Line= 3
     1780637.917      243944.586     1780849.723      244552.225
     1780804.584      244781.391
#Sta/Elev= 30
       0 1070.98    29.2 1062.04   107.2  1045.8   136.5 1041.18   146.2  1038.4
   160.41033.005   165.8 1031.02   175.5 1029.58   204.8 1032.91   253.5 1035.52
   331.5 1035.15  380.351037.323   399.8 1039.84  427.561049.786   438.8 1051.35
   497.2 1049.66   536.2 1052.23  561.921052.799  593.03  1052.4   604.5 1052.48
  620.481053.912   682.4  1063.7   731.1 1069.41   750.6 1069.96  773.311069.071
   789.5 1068.72   808.9 1069.67   828.4 1072.26  836.141074.015   877.1 1086.82
#Mann= 10 ,-1 , 0
       0     .12       0   160.4    .045       0   204.8     .12       0
  380.35      .1       0  427.56     .05       0  561.92     .08       0
  593.03    .016       0  620.48     .06       0  773.31    .016       0
  836.14     .12       0
Bank Sta=160.4,204.8
XS Rating Curve= 0 ,0
Exp/Cntr=0.3,0.1

Type RM Length L Ch R = 1 ,22783.3 ,261.7,267.6,273.3
XS GIS Cut Line= 3
      1780221.25       244139.03     1780474.723      244559.169
     1780547.639      244850.836
#Sta/Elev= 30
       0  1091.6    29.4 1081.91    78.5 1068.71   117.8 1053.91   147.2 1045.04
   166.8 1040.38   186.5 1036.82   196.3 1035.67   215.9 1035.55   225.7 1034.41
  233.691032.518  240.191031.013   255.2  1028.9   274.8 1031.03  320.181034.655
   333.7 1036.43   363.1 1046.05   372.9 1046.96  405.881044.555  434.431042.834
  468.581043.089  523.851048.326  565.061050.849  612.231057.205  653.011060.181
   665.2 1061.44   684.6 1065.58   752.5 1083.37  780.341086.362   791.3 1087.28
#Mann= 13 ,-1 , 0
       0     .12       0  233.69     .08       0  240.19    .045       0
   274.8     .12       0  320.18      .1       0  405.88    .016       0
  434.43     .05       0  468.58     .08       0  523.85    .016       0
  565.06     .06       0  612.23    .016       0  653.01     .12       0
  780.34     .06       0
Bank Sta=240.19,274.8
XS Rating Curve= 0 ,0
Exp/Cntr=0.3,0.1

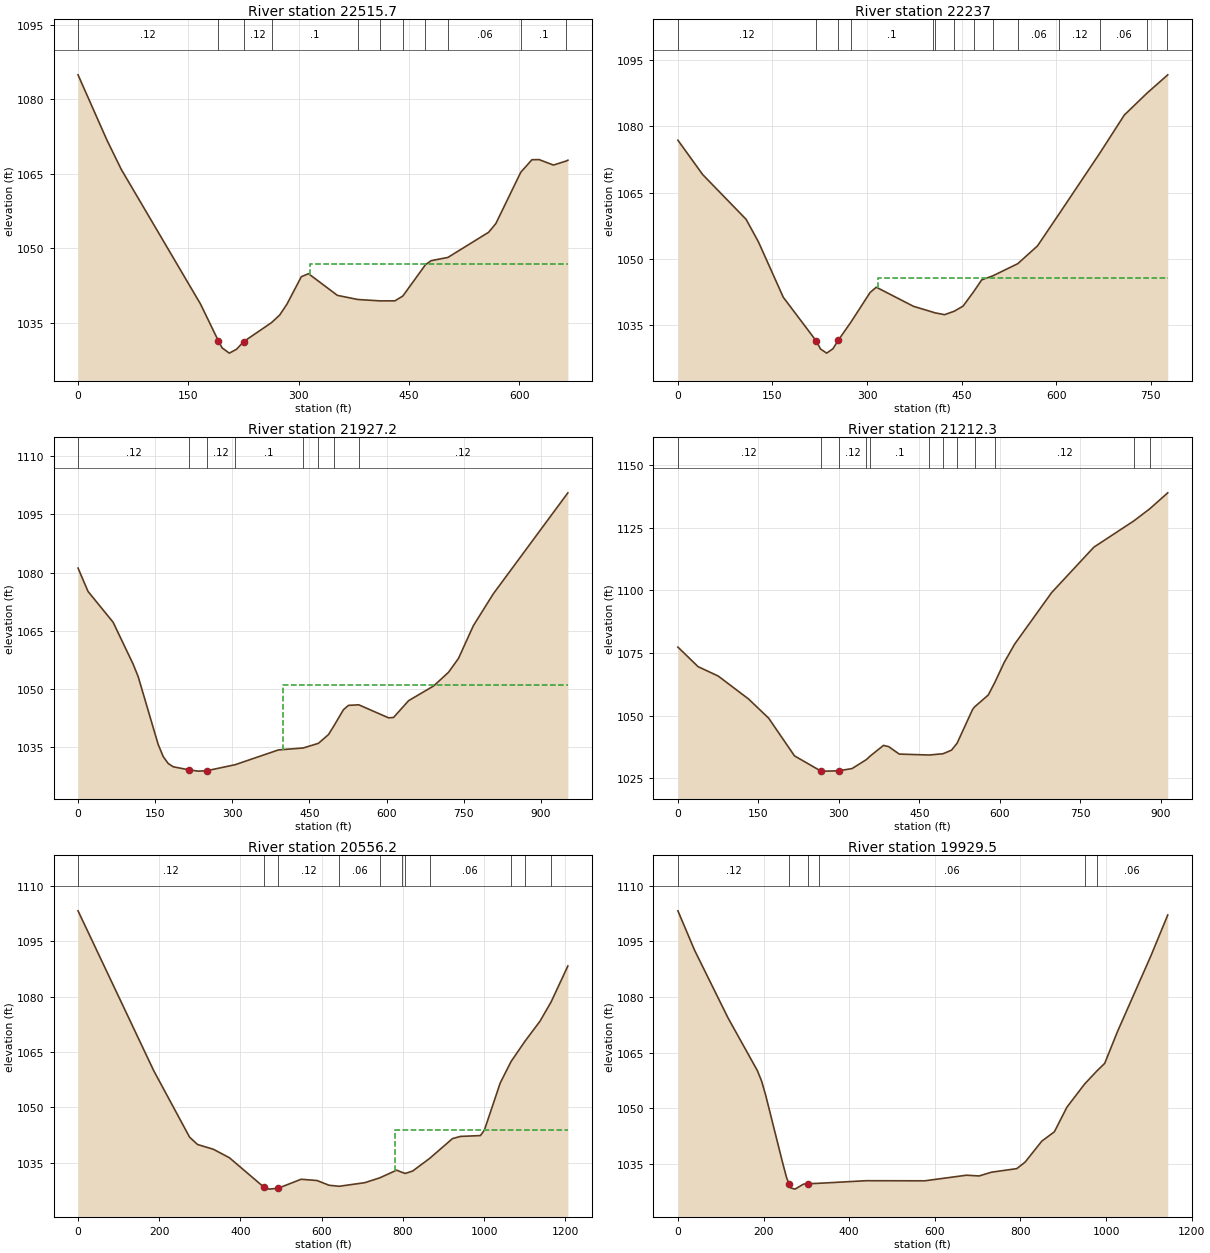
Type RM Length L Ch R = 1 ,22515.7 ,278.5,278.7,278.7
XS GIS Cut Line= 2
     1780040.695      244239.725     1780228.195      244878.614
#Sta/Elev= 30
       0  1084.9    39.2  1071.8    58.8 1065.87   166.5 1038.79   190.81031.378
   195.8 1029.98   205.6 1028.92   215.4 1029.69   225.2 1031.24  262.981035.055
   274.2  1036.6     284 1038.78   303.5 1044.29   313.3  1044.9   352.5 1040.54
  380.24 1039.71  410.871039.427   430.8 1039.44  441.511040.409  472.15 1046.69
   479.8 1047.51  502.781048.174   558.1 1053.23   567.9 1054.98  601.771065.298
   616.9 1067.82   626.7 1067.85   646.2 1066.75  663.781067.573   665.8 1067.73
#Mann= 11 ,-1 , 0
       0     .12       0   190.8    .045       0   225.2     .12       0
  262.98      .1       0  380.24    .016       0  410.87     .06       0
  441.51     .08       0  472.15    .016       0  502.78     .06       0
  601.77      .1       0  663.78    .016       0
#XS Ineff= 2 , 0
                          315.69         1046.84
Permanent Ineff=
       F       F
Bank Sta=190.8,225.2
XS Rating Curve= 0 ,0
Exp/Cntr=0.3,0.1

Type RM Length L Ch R = 1 ,22237   ,304.2,309.8,315.2
XS GIS Cut Line= 2
     1779773.334      244305.697     1779988.612      245052.225
#Sta/Elev= 30
       0 1076.85    39.3 1069.07   108.2 1058.93   127.8 1053.81   167.2 1041.27
   219.71031.338   226.2 1029.56     236 1028.63   245.9 1029.62   254.71031.622
  274.111035.579   304.9 1042.37   314.7 1043.56   373.7 1039.23  404.611037.904
  407.811037.756   422.9 1037.34  438.411038.122   452.4 1039.29     4691042.519
   481.9 1045.22   499.61046.139  539.141048.889   570.4 1052.92  605.261060.288
  669.231073.925   708.1 1082.55     7441087.499  776.081091.535     777 1091.66
#Mann= 14 ,-1 , 0
       0     .12       0   219.7    .045       0   254.7     .12       0
  274.11      .1       0  404.61     .05       0  407.81    .016       0
  438.41     .08       0     469    .016       0   499.6     .12       0
  539.14     .06       0  605.26     .12       0  669.23     .06       0
     744    .016       0  776.08     .12       0
#XS Ineff= 2 , 0
                          317.03         1045.54
Permanent Ineff=
       F       F
Bank Sta=219.7,254.7
XS Rating Curve= 0 ,0
Exp/Cntr=0.3,0.1

Type RM Length L Ch R = 1 ,21927.2 ,724.5,715,705.3
XS GIS Cut Line= 3
     1779526.806      244354.308     1779551.112       245045.28
     1779693.473       245264.03
#Sta/Elev= 30
       0 1081.15    19.5 1075.11    68.2 1067.17   107.1 1056.36   116.9 1053.14
   155.8 1035.63   165.6 1032.48   175.3 1030.69     185 1029.85   215.31029.056
   233.7 1028.72   250.31028.823   305.41030.373   389.5 1034.19  437.841034.696
  467.381035.899   486.9 1038.15  496.921040.277   516.1 1044.59   525.8  1045.7
  545.781045.846   603.8 1042.48   613.5 1042.58   642.7 1046.91   691.4 1050.71
   720.4 1054.25   739.7 1057.82   768.7 1066.29   807.4  1074.5   952.4 1100.58
#Mann= 8 ,-1 , 0
       0     .12       0   215.3    .045       0   250.3     .12       0
   305.4      .1       0  437.84    .016       0  467.38     .06       0
  496.92    .016       0  545.78     .12       0
#XS Ineff= 2 , 0
                          398.35         1050.86
Permanent Ineff=
       F       F
Bank Sta=215.3,250.3
XS Rating Curve= 0 ,0
Exp/Cntr=0.3,0.1

Type RM Length L Ch R = 1 ,21212.3 ,645.7,656.1,666
XS GIS Cut Line= 4
     1778863.612      244493.197     1778901.806      244677.225
        1779065.      245020.975     1779082.362      245364.725
#Sta/Elev= 30
       0 1077.34    37.6 1069.55    75.2 1065.79   131.6 1056.66   169.2 1048.98
   217.2 1033.97     266 1027.95   275.8 1027.88  299.361027.997   324.6 1028.91
  351.261032.496     3581033.849   383.1 1038.15   392.8 1037.64   412.4 1034.68
  467.941034.306  494.021034.815   509.9 1036.26  520.221039.026     549 1052.45
  552.671053.475   578.3 1058.25  590.771063.373   607.8 1071.17   627.5 1078.56
   696.3 1099.08     775  1117.2  849.611127.692  879.171132.506   912.7 1138.88
#Mann= 12 ,-1 , 0
       0     .12       0     266    .045       0  299.36     .12       0
  351.26     .06       0     358      .1       0  467.94    .016       0
  494.02     .12       0  520.22     .08       0  552.67    .016       0
  590.77     .12       0  849.61     .08       0  879.17     .06       0
Bank Sta=266,299.36
XS Rating Curve= 0 ,0
Exp/Cntr=0.3,0.1

Type RM Length L Ch R = 1 ,20556.2 ,619.7,626.6,633.5
XS GIS Cut Line= 3
     1778353.195      244448.058     1778367.084      245399.447
      1778596.25      245510.558
#Sta/Elev= 30
       0 1103.22   186.4 1059.95   274.7 1041.96   294.3 1039.97   333.5 1038.67
   372.8 1036.38   457.91028.408   470.8 1027.89   492.9 1028.13   549.3 1030.56
   588.6 1030.22     618 1028.94  643.131028.658   706.3 1029.64  742.951030.941
   784.7 1033.03  797.361032.447  805.99 1032.14     824 1032.79  865.641036.189
   922.1 1041.57   941.7 1042.16   990.7 1042.38  1000.5 1043.82  1039.6 1056.62
 1066.251062.415 1100.421067.894  1137.6 1073.35 1164.961078.571  1206.2 1088.29
#Mann= 11 ,-1 , 0
       0     .12       0   457.9    .045       0   492.9     .12       0
  643.13     .06       0  742.95    .016       0  797.36     .06       0
  805.99     .12       0  865.64     .06       0 1066.25    .016       0
 1100.42     .08       0 1164.96     .06       0
#XS Ineff= 2 , 0
                          780.19         1043.82
Permanent Ineff=
       F       F
Bank Sta=457.9,492.9
XS Rating Curve= 0 ,0
Exp/Cntr=0.3,0.1

Type RM Length L Ch R = 1 ,19929.5 ,765.8,757,747.6
XS GIS Cut Line= 3
      1777908.75      244382.086     1777641.389      245260.558
     1777644.862      245486.253
#Sta/Elev= 30
       0  1103.2    39.1 1092.54   117.2 1074.31   185.6 1060.14   195.4 1057.34
   205.1 1053.46   244.2 1035.48     254 1031.21   259.71029.652   263.8 1028.53
   273.5  1028.2   293.1 1029.54   302.8 1029.66  328.97 1029.77   439.6 1030.47
   576.4 1030.44     674 1031.95   703.4 1031.75   732.6 1032.77   791.3 1033.72
   810.8 1035.47   849.9 1041.14   879.2 1043.65   908.5 1050.28  949.661056.498
  978.011059.989   996.8  1062.1  1026.2 1070.55  1104.7 1091.09    1144 1102.07
#Mann= 6 ,-1 , 0
       0     .12       0   259.7    .045       0   302.8     .12       0
  328.97     .06       0  949.66    .016       0  978.01     .06       0
Bank Sta=259.7,302.8
XS Rating Curve= 0 ,0
Exp/Cntr=0.3,0.1

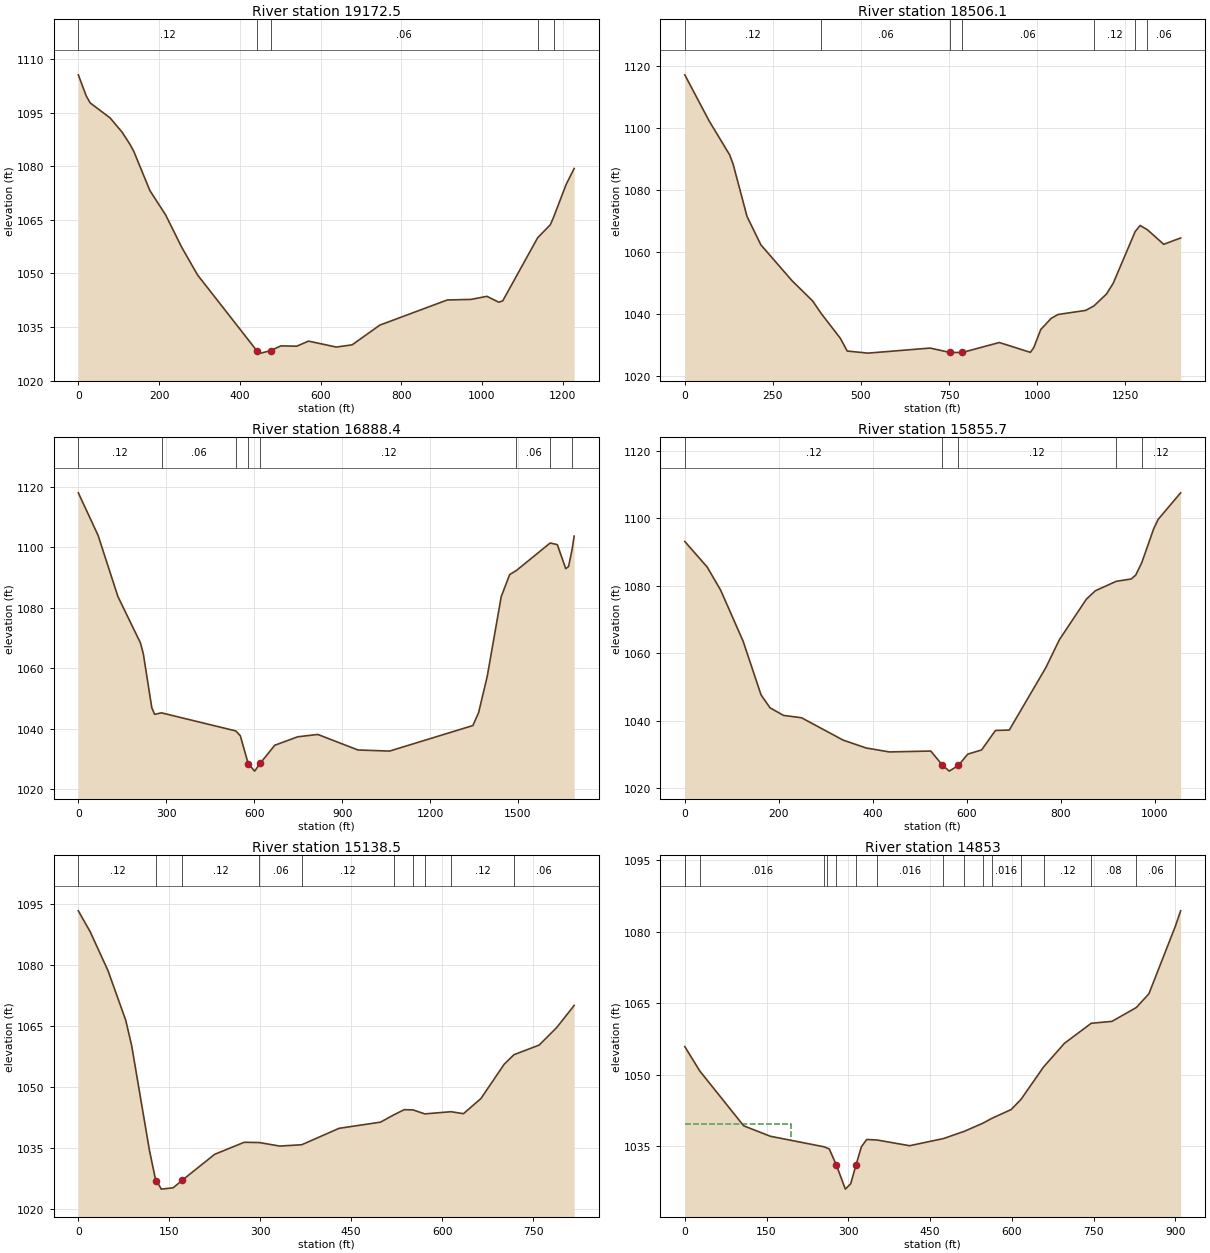
Type RM Length L Ch R = 1 ,19172.5 ,653.2,666.5,679.6
XS GIS Cut Line= 3
      1777158.75      244156.391     1777071.945      244489.725
     1777169.167      245368.197
#Sta/Elev= 30
       0  1105.6    19.7 1099.66    29.5 1097.73    78.7 1093.54   108.3 1089.57
   127.9 1086.15   137.8 1084.07   177.2 1073.22   216.5 1066.34   255.9 1057.38
   295.2 1049.61   441.91028.417   452.5  1027.7   476.91028.424   501.6 1029.73
   540.9 1029.64   570.3 1031.06   639.1  1029.4   678.3 1030.02   747.1 1035.55
     914 1042.58     973 1042.74  1012.2  1043.6  1041.7 1041.95  1051.5 1042.36
 1137.861059.991  1169.4 1063.66 1177.651065.832  1208.6 1074.96  1228.3 1079.39
#Mann= 5 ,-1 , 0
       0     .12       0   441.9    .045       0   476.9     .06       0
 1137.86    .016       0 1177.65     .06       0
Bank Sta=441.9,476.9
XS Rating Curve= 0 ,0
Exp/Cntr=0.3,0.1

Type RM Length L Ch R = 1 ,18506.1 ,1627.6,1617.7,1607.1
XS GIS Cut Line= 3
     1776810.487      243950.749     1776283.143      245024.968
     1776276.632      245235.471
#Sta/Elev= 30
       0 1117.09    68.7 1102.32   127.5 1091.27   137.3 1088.27   176.6 1071.46
   215.8 1062.34   304.1 1050.79   362.9 1044.24     3871040.227   441.4 1032.22
     461  1028.1   519.9 1027.43   696.4 1029.06     7531027.639     7881027.644
   892.6 1030.85   980.9 1027.68   990.7 1029.26  1010.3 1035.04  1039.7 1038.61
  1059.4 1039.88  1137.8  1041.2 1161.09 1042.62  1196.7 1046.45  1215.8  1049.9
 1278.431066.629  1292.4 1068.56 1313.241067.161  1359.4 1062.49  1407.3 1064.53
#Mann= 7 ,-1 , 0
       0     .12       0     387     .06       0     753    .045       0
     788     .06       0 1161.09     .12       0 1278.43    .016       0
 1313.24     .06       0
Bank Sta=753,788
XS Rating Curve= 0 ,0
Exp/Cntr=0.3,0.1

Type RM Length L Ch R = 1 ,16888.4 ,1036.3,1032.7,1028.4
XS GIS Cut Line= 4
     1775471.077      243565.766      1775795.73      243713.336
     1775776.632       244751.53     1775663.785      245025.836
#Sta/Elev= 30
       0 1118.07    67.5 1103.96   134.9 1083.77     212 1068.36   221.7 1064.79
   250.6 1046.94   260.2 1044.74  283.761045.227  537.011039.245   552.5 1037.68
  579.51 1028.43   601.5 1025.93   621.1 1028.59   670.1 1034.49   748.5  1037.3
     817 1038.07   954.2 1032.93  1061.9 1032.57    1346 1041.02  1365.6 1045.29
    1395 1057.28  1442.8  1083.7  1471.5 1090.99 1494.84 1092.38 1609.791101.456
  1634.2 1100.92  1662.9 1092.97  1672.5 1093.67 1684.421099.245  1691.6 1103.74
#Mann= 8 ,-1 , 0
       0     .12       0  283.76     .06       0  537.01     .12       0
  579.51    .045       0   621.1     .12       0 1494.84     .06       0
 1609.79    .016       0 1684.42     .08       0
Bank Sta=579.51,621.1
XS Rating Curve= 0 ,0
Exp/Cntr=0.3,0.1

Type RM Length L Ch R = 1 ,15855.7 ,721.1,717.1,712.9
XS GIS Cut Line= 4
     1774839.132      244105.697     1775031.841      244246.322
      1775116.91      244749.794     1775276.632      245010.211
#Sta/Elev= 30
       0 1093.08    47.7 1085.49    76.3 1078.65     124 1063.55   162.2 1047.63
   181.3  1043.8   209.9 1041.55   248.4 1040.84   336.8 1034.22   385.8 1031.89
     435 1030.72   523.3 1030.98  547.931026.809   562.6 1025.03   582.2 1026.75
   601.9 1030.07   631.3  1031.3   660.8 1037.09   690.2  1037.2   768.3 1055.78
   796.9    1064   854.2 1075.98   873.3 1078.48   917.71081.273   949.6 1081.97
   959.2 1083.12   972.1 1086.83   997.4 1096.85  1006.9 1099.63  1054.7  1107.5
#Mann= 5 ,-1 , 0
       0     .12       0  547.93    .045       0   582.2     .12       0
   917.7    .016       0   972.1     .12       0
Bank Sta=547.93,582.2
XS Rating Curve= 0 ,0
Exp/Cntr=0.3,0.1

Type RM Length L Ch R = 1 ,15138.5 ,299.2,285.5,271.7
XS GIS Cut Line= 3
     1774346.048      244415.766     1774564.798      245012.121
     1774456.725      245159.256
#Sta/Elev= 30
       0 1093.29    19.5 1088.17    48.9 1078.62    78.2 1066.43      88 1060.18
   117.3  1034.5     127 1027.58   128.91027.076   136.8 1024.98   156.4 1025.31
  171.021027.118   224.8 1033.52   273.6 1036.48  298.321036.416   332.3 1035.55
  368.521035.877     430  1039.9   498.4 1041.42  520.84 1043.25   537.5 1044.48
  552.111044.422   571.51043.448  614.661043.983   635.2  1043.5     664 1047.21
   702.5 1055.66  718.611057.982   760.1 1060.34   788.9 1064.62   817.8 1070.07
#Mann= 10 ,-1 , 0
       0     .12       0   128.9    .045       0  171.02     .12       0
  298.32     .06       0  368.52     .12       0  520.84    .016       0
  552.11     .12       0   571.5     .06       0  614.66     .12       0
  718.61     .06       0
Bank Sta=128.9,171.02
XS Rating Curve= 0 ,0
Exp/Cntr=0.3,0.1

Type RM Length L Ch R = 1 ,14853   ,86.5,79.1,78.6
XS GIS Cut Line= 3
     1773974.954      244583.735     1774506.204      244954.829
     1774398.131       245193.11
#Sta/Elev= 30
       0 1055.92     .621055.799   27.53  1050.8     108  1039.3   157.1  1037.1
  255.821034.885  260.82 1034.64   265.1 1034.43   278.11031.054   294.6 1026.01
   304.4 1027.15   314.2  1031.1     324  1034.9   333.8 1036.43  353.221036.311
   412.4 1035.12  474.57 1036.62  512.761038.139  547.481039.876  563.141040.851
   598.9 1042.72  616.811044.837  658.341051.659   696.5  1056.6   745.71060.814
   783.7 1061.21  828.371064.114   851.5    1067  899.72 1081.08   909.7 1084.41
#Mann= 17 ,-1 , 0
       0     .12       0     .62      .1       0   27.53    .016       0
  255.82     .06       0  260.82    .016       0   278.1    .045       0
   314.2      .1       0  353.22    .016       0  474.57     .06       0
  512.76    .016       0  547.48     .06       0  563.14    .016       0
  616.81     .06       0  658.34     .12       0   745.7     .08       0
  828.37     .06       0  899.72     .12       0
#XS Ineff= 2 , 0
          195.05 1039.75
Permanent Ineff=
       F       F
Bank Sta=278.1,314.2
XS Rating Curve= 0 ,0
Exp/Cntr=0.3,0.1

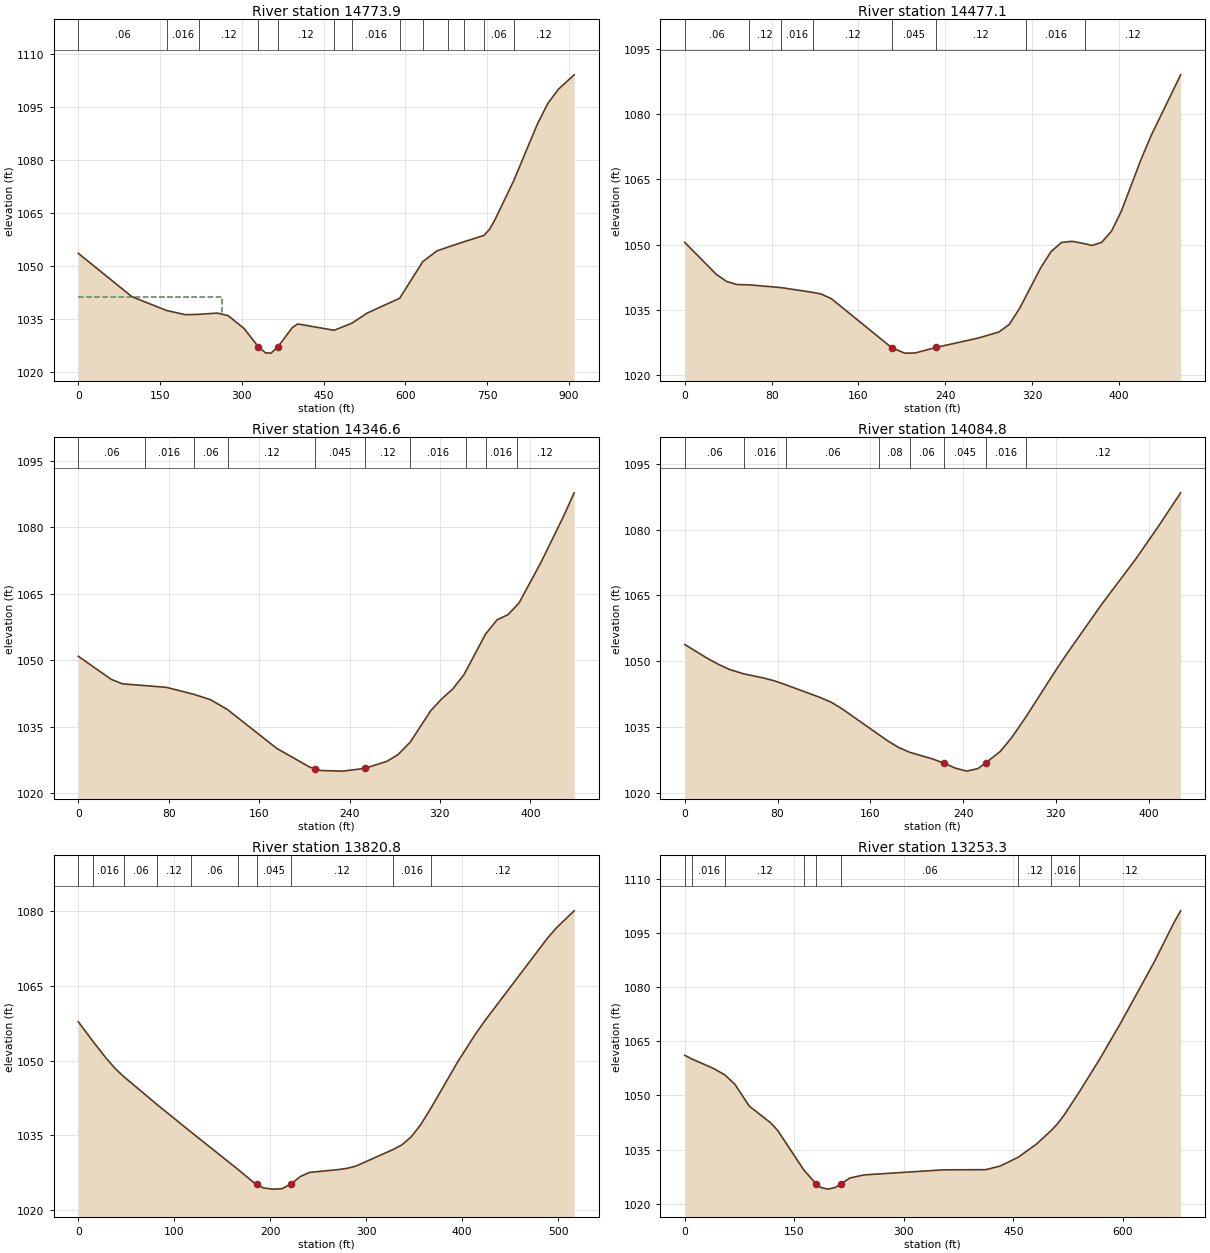
Type RM Length L Ch R = 1 ,14773.9 ,267.4,296.9,319.2
XS GIS Cut Line= 3
     1773877.298      244608.475     1774408.548      244979.568
     1774300.475       245217.85
#Sta/Elev= 30
       0 1053.57    98.2 1041.33  161.851037.417   196.4 1036.23  221.391036.338
   255.3 1036.68   274.9 1035.96   304.4 1032.28  329.87 1027.22   343.6 1025.43
   353.5 1025.36  365.931027.089   392.7 1032.61   402.6 1033.61  469.411031.817
  501.981033.828   530.2 1036.71  589.541040.865  632.051051.233   657.7 1054.25
  678.251055.345  708.34 1056.88  744.211058.645   754.6 1060.38   764.3 1063.05
  798.521073.992   841.8 1089.97   861.2  1095.9   880.6 1099.94   909.7 1104.04
#Mann= 13 ,-1 , 0
       0     .06       0  161.85    .016       0  221.39     .12       0
  329.87    .045       0  365.93     .12       0  469.41     .08       0
  501.98    .016       0  589.54     .06       0  632.05     .12       0
  678.25     .06       0  708.34     .08       0  744.21     .06       0
  798.52     .12       0
#XS Ineff= 2 , 0
          263.16 1041.11
Permanent Ineff=
       F       F
Bank Sta=329.87,365.93
XS Rating Curve= 0 ,0
Exp/Cntr=0.3,0.1

Type RM Length L Ch R = 1 ,14477.1 ,128.7,130.5,132.3
XS GIS Cut Line= 3
     1773869.485      244620.193     1773869.485      244976.964
     1773838.235      245072.016
#Sta/Elev= 30
       0 1050.52    28.9 1043.23    38.6 1041.55    48.2 1040.85   59.121040.789
   88.661040.156   118.21039.046   125.4 1038.69     135 1037.62  190.591026.364
   202.5 1025.11   212.1 1025.14   231.4 1026.41     270 1028.55   289.3 1029.95
   298.9 1031.69   308.6 1035.44  314.511038.272   327.8 1044.66   337.5 1048.44
   347.1 1050.52   356.8 1050.78  369.031050.207     375 1049.82   384.1 1050.55
   393.2 1053.13   402.2 1057.71   420.4 1069.61   429.5 1074.99   456.8    1089
#Mann= 8 ,-1 , 0
       0     .06       0   59.12     .12       0   88.66    .016       0
   118.2     .12       0  190.59    .045       0   231.4     .12       0
  314.51    .016       0  369.03     .12       0
Bank Sta=190.59,231.4
XS Rating Curve= 0 ,0
Exp/Cntr=0.3,0.1

Type RM Length L Ch R = 1 ,14346.6 ,255.5,261.8,268
XS GIS Cut Line= 2
     1773755.944      244608.735      1773722.09      245046.235
#Sta/Elev= 30
       0 1050.86    29.2 1045.64      39 1044.64   58.891044.236      78 1043.84
  102.441042.257     117 1041.06  132.111038.814   175.5 1030.09   204.8 1025.84
   209.7 1025.46   214.5 1025.08     234 1024.94   253.5 1025.56     273 1027.14
   282.8 1028.64  293.691031.472     312 1038.62   321.8  1041.3   331.5 1043.51
   341.3 1046.73  343.141047.601  360.341055.847   370.6 1059.08   380.3 1060.26
  387.811062.288     390 1062.88   409.6 1072.13   429.1 1082.28   438.8 1087.74
#Mann= 10 ,-1 , 0
       0     .06       0   58.89    .016       0  102.44     .06       0
  132.11     .12       0   209.7    .045       0   253.5     .12       0
  293.69    .016       0  343.14     .08       0  360.34    .016       0
  387.81     .12       0
Bank Sta=209.7,253.5
XS Rating Curve= 0 ,0
Exp/Cntr=0.3,0.1

Type RM Length L Ch R = 1 ,14084.8 ,259.5,264,268.6
XS GIS Cut Line= 2
     1773568.444       244561.86     1773420.006      244962.902
#Sta/Elev= 30
       0 1053.82    19.4 1050.67    29.2 1049.27    38.9 1048.09   50.921047.116
      68 1046.17    77.8 1045.49   87.561044.584   116.6 1041.75   126.4 1040.63
   136.1 1039.07  167.68 1033.19   174.9 1031.85   184.7 1030.29  193.911029.236
   213.8  1027.7   223.5 1026.75   233.2 1025.63     243 1024.93   252.7  1025.5
  259.53 1026.81   272.1 1029.44   281.8 1032.53     294 1037.23   320.7 1048.24
   330.4 1052.04   359.6 1063.02   388.8 1073.28   408.2 1080.68   427.6 1088.42
#Mann= 8 ,-1 , 0
       0     .06       0   50.92    .016       0   87.56     .06       0
  167.68     .08       0  193.91     .06       0   223.5    .045       0
  259.53    .016       0     294     .12       0
Bank Sta=223.5,259.53
XS Rating Curve= 0 ,0
Exp/Cntr=0.3,0.1

Type RM Length L Ch R = 1 ,13820.8 ,577.7,567.5,556.5
XS GIS Cut Line= 3
     1773373.131      244470.714      1773159.59      244814.464
     1773154.381      244926.443
#Sta/Elev= 30
       0 1057.77   15.761053.723    28.9 1050.49    38.5 1048.37   47.111046.808
   82.251041.129  117.751035.594  165.911028.208   183.1 1025.46  185.711025.177
   192.7 1024.42   202.3 1024.17     212 1024.23   221.6 1025.19   231.2 1026.68
   240.9 1027.53   269.8 1028.07   279.4 1028.32   289.1 1028.78  328.221032.143
   337.2 1033.05   346.9 1034.66   356.5 1037.02  367.781040.514     395  1049.6
     414 1055.33   423.4  1057.9   488.8 1074.53   498.1  1076.6   516.8 1080.06
#Mann= 10 ,-1 , 0
       0     .06       0   15.76    .016       0   47.11     .06       0
   82.25     .12       0  117.75     .06       0  165.91     .12       0
  185.71    .045       0   221.6     .12       0  328.22    .016       0
  367.78     .12       0
Bank Sta=185.71,221.6
XS Rating Curve= 0 ,0
Exp/Cntr=0.3,0.1

Type RM Length L Ch R = 1 ,13253.3 ,383,383.3,383.3
XS GIS Cut Line= 3
     1772810.631      244220.714     1772761.152      244778.006
     1772727.298      244892.589
#Sta/Elev= 30
       0  1061.1   10.241060.042    39.3 1057.47   55.251055.624    68.7 1053.04
    88.3 1047.03   117.8 1042.36   127.6 1040.17  163.371029.223  180.021025.448
   186.5 1024.45   196.3 1024.02   206.1  1024.5  214.091025.478   225.8 1027.08
   245.4 1027.96   353.4 1029.36   412.2 1029.41   431.9 1030.42  456.781032.879
     481 1036.41  500.93  1040.1   510.4 1042.12   520.2 1044.76  540.02 1050.89
   568.7 1060.22   596.2 1069.81   642.2 1086.71   669.8 1097.84     679 1101.14
#Mann= 9 ,-1 , 0
       0     .12       0   10.24    .016       0   55.25     .12       0
  163.37     .06       0  180.02    .045       0  214.09     .06       0
  456.78     .12       0  500.93    .016       0  540.02     .12       0
Bank Sta=180.02,214.09
XS Rating Curve= 0 ,0
Exp/Cntr=0.3,0.1