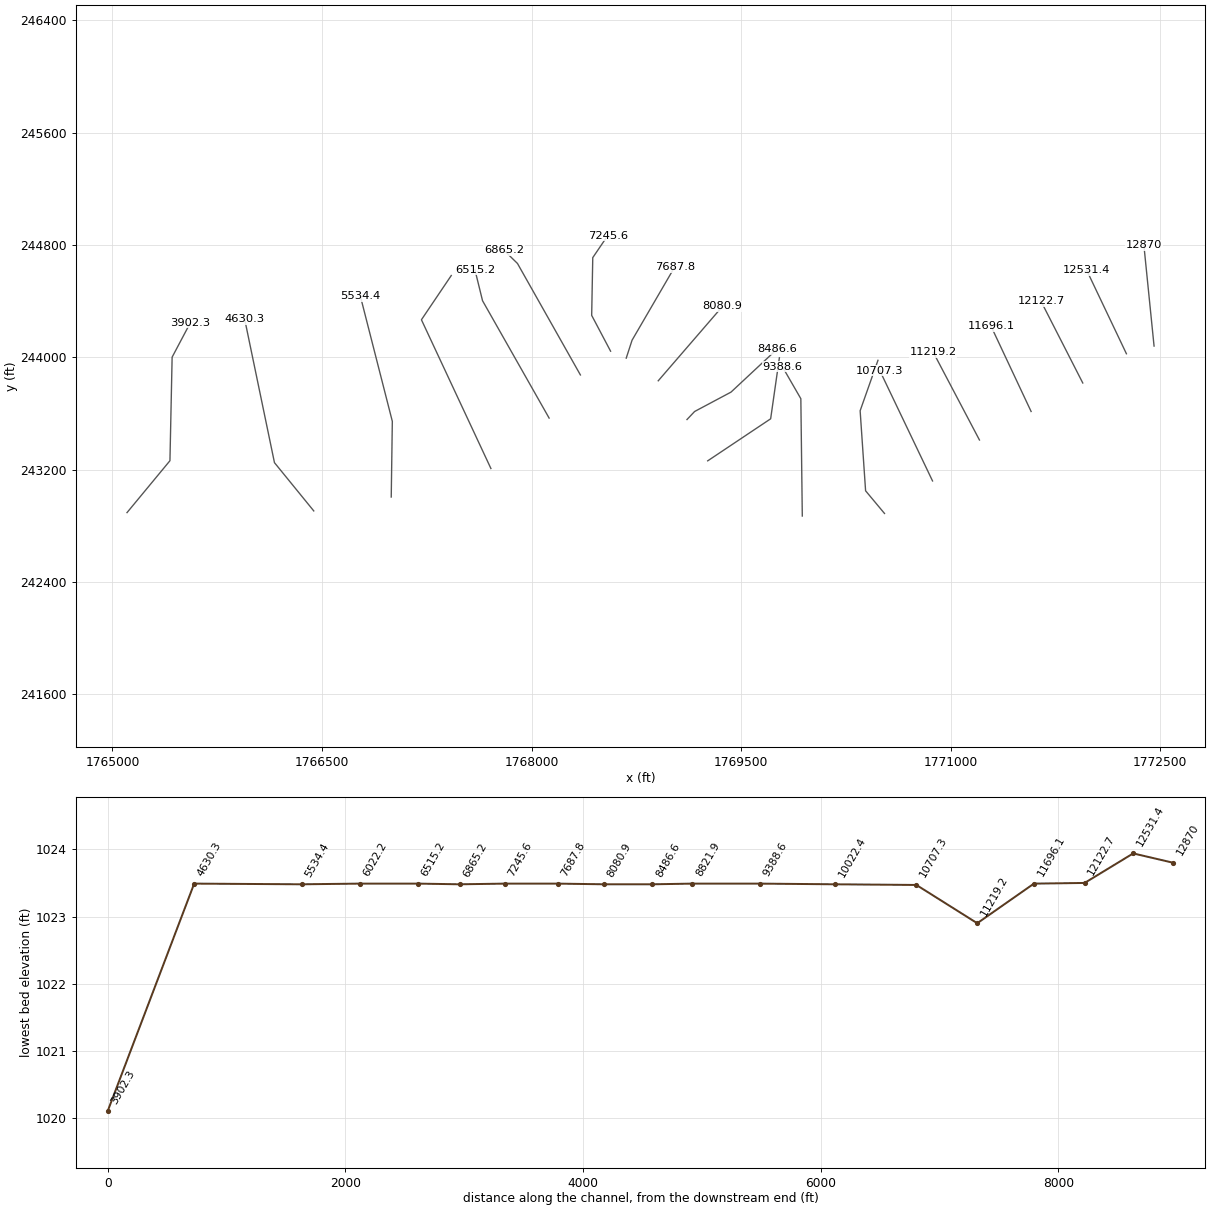
HEC-RAS study ELKCK.prj: ELKCK

--- ELKCK.g01 (geometry) --- (continued)

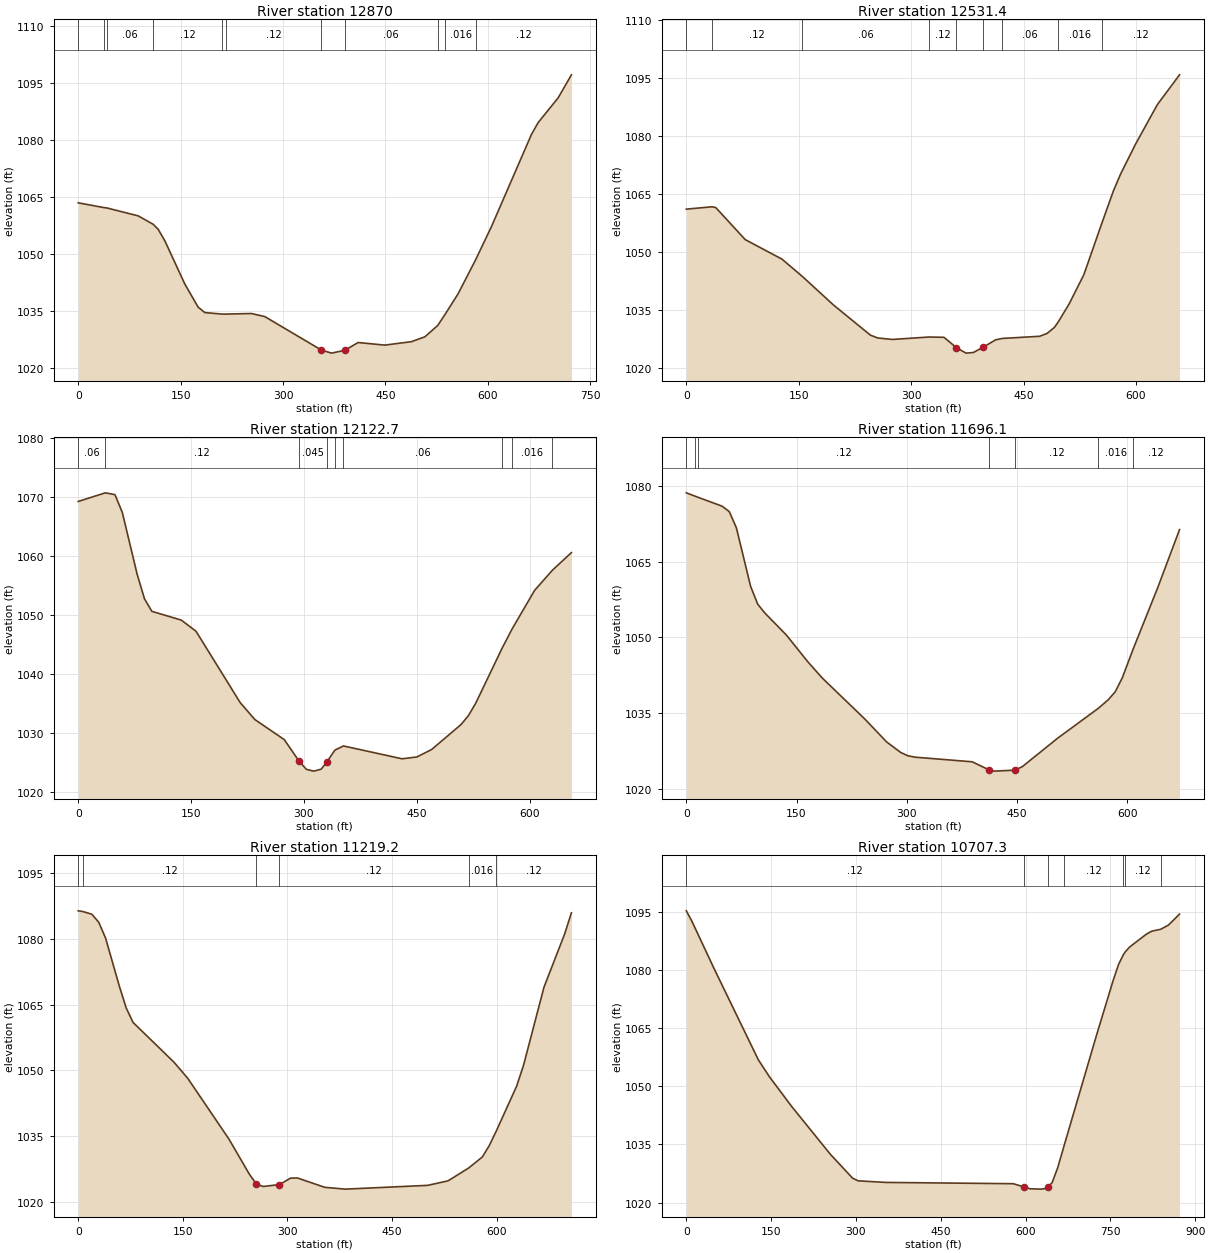
Type RM Length L Ch R = 1 ,12870   ,330.7,338.6,346.3
XS GIS Cut Line= 2
     1772456.465      244080.089     1772383.548      244798.839
#Sta/Elev= 30
       0 1063.41   37.141062.171   42.261062.047    87.9 1059.97  109.93 1057.74
   117.2 1056.42   126.9 1053.41   156.2    1042   175.7 1035.91   185.5 1034.49
  210.56 1034.09  217.03 1034.09   253.8 1034.24   273.4 1033.42  355.921024.633
     371  1023.8   390.5 1024.54     410  1026.6   449.1 1025.91   488.1 1026.82
   507.7 1028.09  526.581031.086  537.721034.115   556.5 1039.46  582.361048.492
   605.3 1057.15   663.9 1081.44   673.6 1084.53   702.9 1091.06   722.4 1097.14
#Mann= 11 ,-1 , 0
       0     .06       0   37.14    .016       0   42.26     .06       0
  109.93     .12       0  210.56     .06       0  217.03     .12       0
  355.92    .045       0   390.5     .06       0  526.58     .12       0
  537.72    .016       0  582.36     .12       0
Bank Sta=355.92,390.5
XS Rating Curve= 0 ,0
Exp/Cntr=0.3,0.1

Type RM Length L Ch R = 1 ,12531.4 ,408,408.7,409.2
XS GIS Cut Line= 2
     1772258.548      244025.402     1771974.694      244619.152
#Sta/Elev= 30
       0 1061.19   34.391061.805    39.3  1061.6    78.6 1053.31   127.7 1048.25
  154.941043.761   196.4 1036.39   245.6  1028.6   255.4 1027.86     275 1027.48
  324.21 1028.11   343.8 1028.03   360.51025.334   373.3 1023.94   383.1 1024.11
   395.51025.402   412.6 1027.37  421.371027.737   471.5  1028.3   481.3 1029.04
   491.1 1030.58  496.461032.063   510.8 1036.68   530.4 1044.21     554  1057.3
   569.7 1065.83   579.5 1070.29   599.2 1077.94   628.6 1088.26   658.1 1095.94
#Mann= 9 ,-1 , 0
       0     .04       0   34.39     .12       0  154.94     .06       0
  324.21     .12       0   360.5    .045       0   395.5     .12       0
  421.37     .06       0  496.46    .016       0     554     .12       0
Bank Sta=360.5,395.5
XS Rating Curve= 0 ,0
Exp/Cntr=0.3,0.1

Type RM Length L Ch R = 1 ,12122.7 ,427.4,426.6,425.9
XS GIS Cut Line= 2
     1771946.048      243817.068     1771646.569      244400.402
#Sta/Elev= 30
       0 1069.22   36.151070.683    48.9 1070.37    58.7 1067.34    78.3 1056.91
    88.1 1052.72    97.9 1050.59     137 1049.11   156.6 1047.22   215.3 1035.13
   234.9 1032.24     274 1028.84   293.6 1025.19   303.4  1023.8   313.2  1023.5
     323 1023.83   330.61025.063  341.281027.064  352.631027.768   430.6 1025.59
   450.2  1025.9   469.8 1027.16   508.9 1031.39   518.7  1032.9   528.5 1035.02
  563.571044.348  576.941047.628   606.8 1054.15  630.361057.556   655.7 1060.55
#Mann= 9 ,-1 , 0
       0     .06       0   36.15     .12       0   293.6    .045       0
   330.6     .06       0  341.28     .12       0  352.63     .06       0
  563.57     .12       0  576.94    .016       0  630.36     .12       0
Bank Sta=293.6,330.6
XS Rating Curve= 0 ,0
Exp/Cntr=0.3,0.1

Type RM Length L Ch R = 1 ,11696.1 ,475.9,476.9,477.9
XS GIS Cut Line= 2
     1771576.256      243613.943     1771289.798      244220.714
#Sta/Elev= 30
       0 1078.69   12.431077.998   15.581077.823    48.6 1076.05    58.4 1074.98
    68.1 1071.76    87.5 1060.13    97.2 1056.59     107 1054.83   136.1 1050.49
   165.3 1045.18   184.8 1041.98   243.1 1033.79   272.3 1029.31   291.7 1027.19
   301.5 1026.53   311.2 1026.26     389 1025.34   411.91023.734   418.2 1023.49
   446.91023.682     457 1024.37   505.7 1030.08  560.161035.905   573.8 1037.61
   583.5 1039.22   593.2 1042.02  607.861047.688   641.8 1060.06     671  1071.4
#Mann= 7 ,-1 , 0
       0     .12       0   12.43     .06       0   15.58     .12       0
   411.9    .045       0   446.9     .12       0  560.16    .016       0
  607.86     .12       0
Bank Sta=411.9,446.9
XS Rating Curve= 0 ,0
Exp/Cntr=0.3,0.1

Type RM Length L Ch R = 1 ,11219.2 ,512.5,511.9,511.2
XS GIS Cut Line= 2
     1771206.465      243410.818     1770875.735      244035.818
#Sta/Elev= 30
       0 1086.38    6.711086.223    19.6  1085.6    29.5 1083.76    39.3 1080.14
    58.9 1069.24    68.8 1064.24    78.6 1060.93   137.5 1051.82   157.1 1048.17
   216.1 1034.32   245.5 1026.28   255.4 1024.08   265.2  1023.5   288.51023.937
   304.4  1025.4   314.3 1025.44   353.6 1023.31     383  1022.9   500.9 1023.76
   530.3 1024.79  559.851027.725   579.4 1030.24   589.3 1032.82  599.231036.104
   628.5 1046.36   638.4 1051.12   667.8 1068.98   697.3 1081.06   707.1 1085.93
#Mann= 6 ,-1 , 0
       0     .06       0    6.71     .12       0   255.4    .045       0
   288.5     .12       0  559.85    .016       0  599.23     .12       0
Bank Sta=255.4,288.5
XS Rating Curve= 0 ,0
Exp/Cntr=0.3,0.1

Type RM Length L Ch R = 1 ,10707.3 ,693.9,684.9,675.9
XS GIS Cut Line= 2
     1770870.527      243119.152     1770492.923       243905.61
#Sta/Elev= 30
       0 1095.24     9.8 1092.58      49 1080.38   127.4 1056.82     147 1052.45
   186.2 1044.82   254.9 1032.44   294.1  1026.3   303.9 1025.61   352.9  1025.2
   578.3 1024.87   597.9 1024.01   607.8 1023.56   627.4 1023.47   637.2 1023.66
  640.241024.116     647 1025.13   656.8 1028.94  668.771034.952   725.4 1063.08
   754.8 1077.19   764.6 1081.43  772.951083.901  776.281084.635   784.2 1085.92
   813.6  1089.2   823.4    1090  838.931090.478   852.8 1091.56   872.4  1094.4
#Mann= 7 ,-1 , 0
       0     .12       0   597.9    .045       0  640.24    .016       0
  668.77     .12       0  772.95     .08       0  776.28     .12       0
  838.93     .06       0
Bank Sta=597.9,640.24
XS Rating Curve= 0 ,0
Exp/Cntr=0.3,0.1

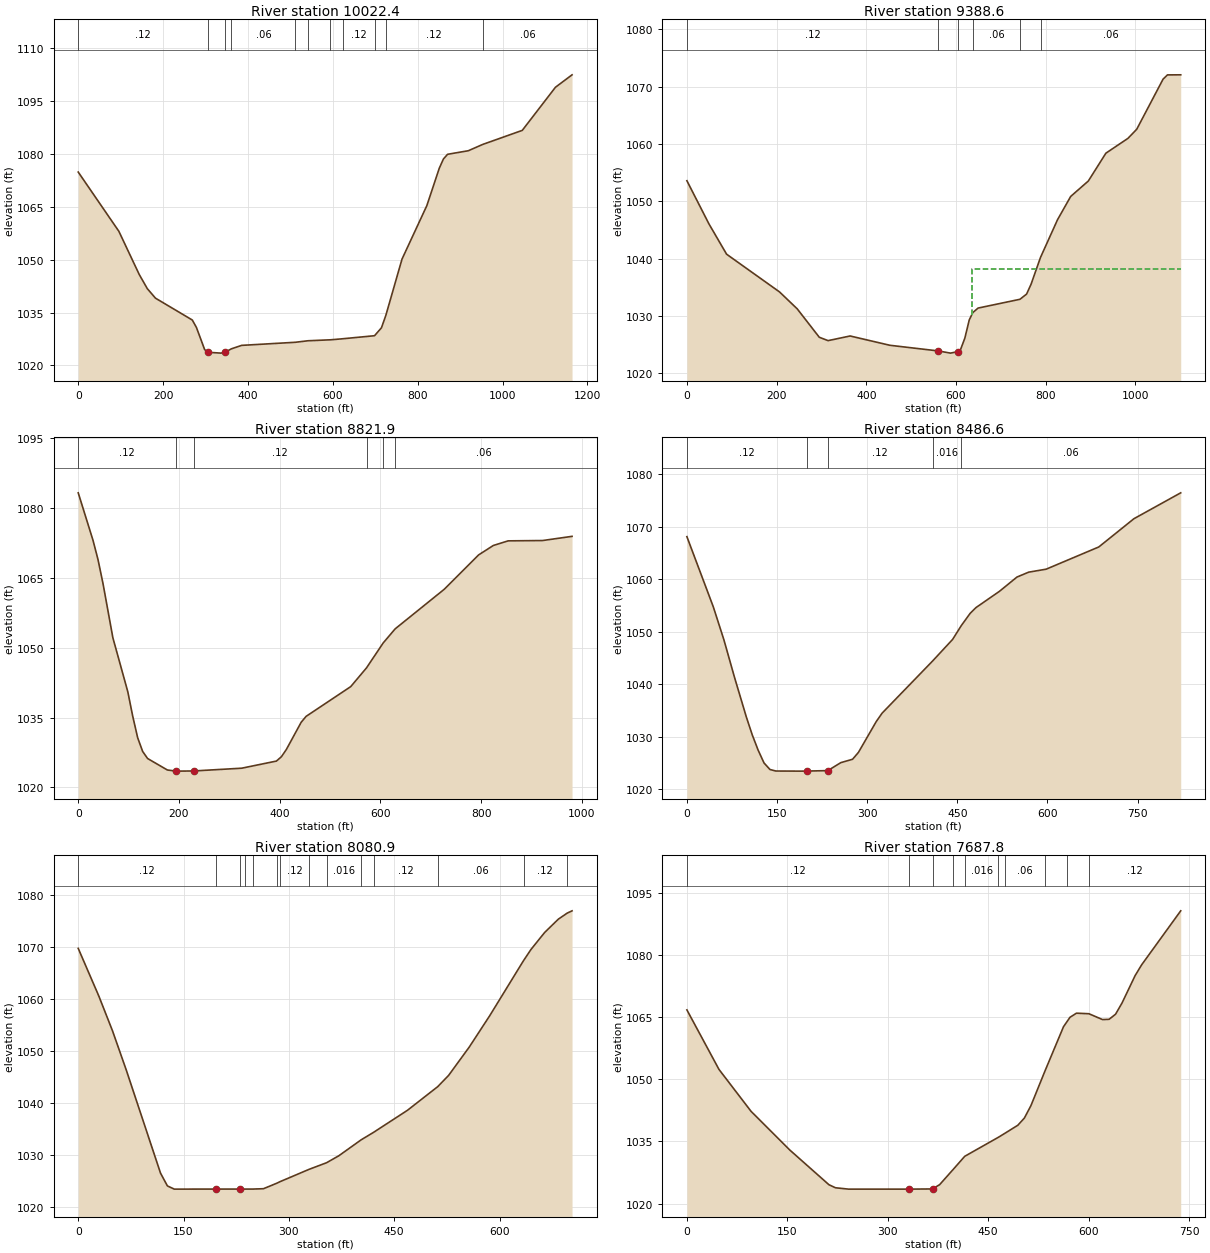
Type RM Length L Ch R = 1 ,10022.4 ,636.2,633.7,631.2
XS GIS Cut Line= 4
     1770526.777      242887.381      1770391.36      243048.839
     1770352.298      243619.152     1770479.902      243978.527
#Sta/Elev= 30
       0 1074.88    95.8 1058.06   143.7 1045.82   162.8 1041.78     182 1039.09
   268.9 1032.87   278.6 1030.75   297.9 1024.49   305.4 1023.72   336.7 1023.48
   346.4 1023.76  360.981024.702   385.1 1025.68  511.611026.559  541.251026.987
   594.2 1027.26  624.211027.567   698.31028.425   714.6 1030.68  724.971034.224
     763 1050.17   821.5 1065.35   850.8 1075.96   860.6  1078.6   870.4 1079.93
   919.3 1080.94  953.351082.737  1046.4 1086.72  1124.6 1098.96  1163.7 1102.49
#Mann= 11 ,-1 , 0
       0     .12       0   305.4    .045       0   346.4     .12       0
  360.98     .06       0  511.61     .08       0  541.25     .12       0
   594.2     .08       0  624.21     .12       0   698.3    .016       0
  724.97     .12       0  953.35     .06       0
Bank Sta=305.4,346.4
XS Rating Curve= 0 ,0
Exp/Cntr=0.3,0.1

Type RM Length L Ch R = 1 ,9388.6  ,589.8,566.7,543.7
XS GIS Cut Line= 3
     1769938.235      242869.152     1769927.819      243705.089
     1769795.006      243934.256
#Sta/Elev= 30
       0 1053.57    49.2 1046.03    88.5 1040.75   206.5 1034.17   245.9 1031.22
   295.1 1026.26   314.7 1025.67   363.9 1026.48   452.4 1024.86   560.6 1023.87
   587.7 1023.49  604.711023.766   609.8 1024.06   619.6  1026.1   629.5 1029.29
  637.411030.565   649.1 1031.35  742.551032.885   757.3  1033.8   767.2  1035.5
   788.31040.188   826.2 1046.76   855.6 1050.83   894.9 1053.52   934.1 1058.38
   983.2 1060.96  1002.8 1062.55  1061.6  1071.3  1071.4 1072.04  1100.9 1072.05
#Mann= 6 ,-1 , 0
       0     .12       0   560.6    .045       0  604.71     .12       0
  637.41     .06       0  742.55    .016       0   788.3     .06       0
#XS Ineff= 2 , 0
                          635.29         1038.24
Permanent Ineff=
       F       F
Bank Sta=560.6,604.71
XS Rating Curve= 0 ,0
Exp/Cntr=0.3,0.1

Type RM Length L Ch R = 1 ,8821.9  ,337.5,335.3,333
XS GIS Cut Line= 3
     1769261.152      243262.381     1769711.673       243561.86
     1769774.173      243996.756
#Sta/Elev= 30
       0 1083.28    29.5 1073.02    39.3 1068.92    49.2 1063.78    68.8 1052.13
    98.4 1040.55   108.2 1035.28     118 1030.66   127.9 1027.72   137.7  1026.2
     177 1023.73   194.41023.497   196.7 1023.49   229.41023.526   324.6 1024.12
   393.4 1025.65   403.3 1026.58   413.1 1028.13   442.6 1033.99   452.4 1035.26
     541 1041.65  572.261045.671  605.451051.035  629.171054.056   726.5 1062.55
   794.8 1069.94   824.1 1071.97   853.4 1072.96   921.8 1073.03   980.3 1073.93
#Mann= 6 ,-1 , 0
       0     .12       0   194.4    .045       0   229.4     .12       0
  572.26    .016       0  605.45     .12       0  629.17     .06       0
Bank Sta=194.4,229.4
XS Rating Curve= 0 ,0
Exp/Cntr=0.3,0.1

Type RM Length L Ch R = 1 ,8486.6  ,397.3,405.7,414.1
XS GIS Cut Line= 4
     1769112.715      243556.652     1769167.402      243613.943
     1769427.819      243751.964     1769755.944      244056.652
#Sta/Elev= 30
       0  1068.1      44 1054.72    61.6 1048.46    79.2 1041.33    98.8 1033.82
   108.7 1030.39   118.5 1027.48   128.3 1025.04   138.2 1023.79     148  1023.5
   187.3 1023.48   199.5 1023.49   234.51023.577     256 1025.09   275.7 1025.74
   285.5 1027.06     315  1032.9   324.8 1034.51  408.741044.426   442.1 1048.54
  456.62 1051.18   471.3  1053.5     481  1054.6     520 1057.69   549.2 1060.41
   568.6 1061.34   597.8 1061.91   685.4 1066.14   743.8 1071.51   821.7 1076.44
#Mann= 5 ,-1 , 0
       0     .12       0   199.5    .045       0   234.5     .12       0
  408.74    .016       0  456.62     .06       0
Bank Sta=199.5,234.5
XS Rating Curve= 0 ,0
Exp/Cntr=0.3,0.1

Type RM Length L Ch R = 1 ,8080.9  ,387.5,393.1,397.8
XS GIS Cut Line= 2
     1768906.985      243832.693     1769367.923      244363.943
#Sta/Elev= 30
       0 1069.78    29.3 1060.62    48.8 1053.93    68.4 1046.39   117.2 1026.56
     127  1024.1   136.8 1023.48   195.8 1023.49   230.8 1023.49  236.81 1023.49
  248.68 1023.49   263.8 1023.56  282.771024.614  287.231024.903  328.721027.283
  353.731028.558   371.2  1029.9   402.91032.958  420.63  1034.4   468.9 1038.64
  512.021043.189   527.5 1045.35   556.8 1050.78   586.1 1056.84  634.221067.427
   644.7 1069.55   664.3 1072.84   683.8  1075.4  696.371076.557   703.3    1077
#Mann= 14 ,-1 , 0
       0     .12       0   195.8    .045       0   230.8     .12       0
  236.81     .06       0  248.68     .12       0  282.77     .08       0
  287.23     .12       0  328.72     .08       0  353.73    .016       0
   402.9     .08       0  420.63     .12       0  512.02     .06       0
  634.22     .12       0  696.37     .08       0
Bank Sta=195.8,230.8
XS Rating Curve= 0 ,0
Exp/Cntr=0.3,0.1

Type RM Length L Ch R = 1 ,7687.8  ,431.3,442.2,453.5
XS GIS Cut Line= 3
     1768677.819      243994.152     1768719.485      244121.756
     1769024.173      244642.589
#Sta/Elev= 30
       0 1066.72    47.9 1052.37    95.9 1042.24   153.7 1032.92   212.1 1024.56
   221.8 1023.82   241.3 1023.49   331.9 1023.49   366.91023.535   377.5 1024.57
  397.611028.217  414.991031.406   465.4 1036.01   475.21036.978   494.3  1038.9
   504.1 1040.64   513.8 1043.61  535.411052.206   562.5 1062.66  567.081063.737
   572.2 1064.94   581.9 1065.93  600.461065.797   620.8 1064.39   630.6 1064.45
   640.3 1065.69     650 1068.41   669.5    1075   679.2 1077.59   737.6 1090.62
#Mann= 10 ,-1 , 0
       0     .12       0   331.9    .045       0   366.9     .12       0
  397.61     .06       0  414.99    .016       0   465.4     .08       0
   475.2     .06       0  535.41     .08       0  567.08    .016       0
  600.46     .12       0
Bank Sta=331.9,366.9
XS Rating Curve= 0 ,0
Exp/Cntr=0.3,0.1

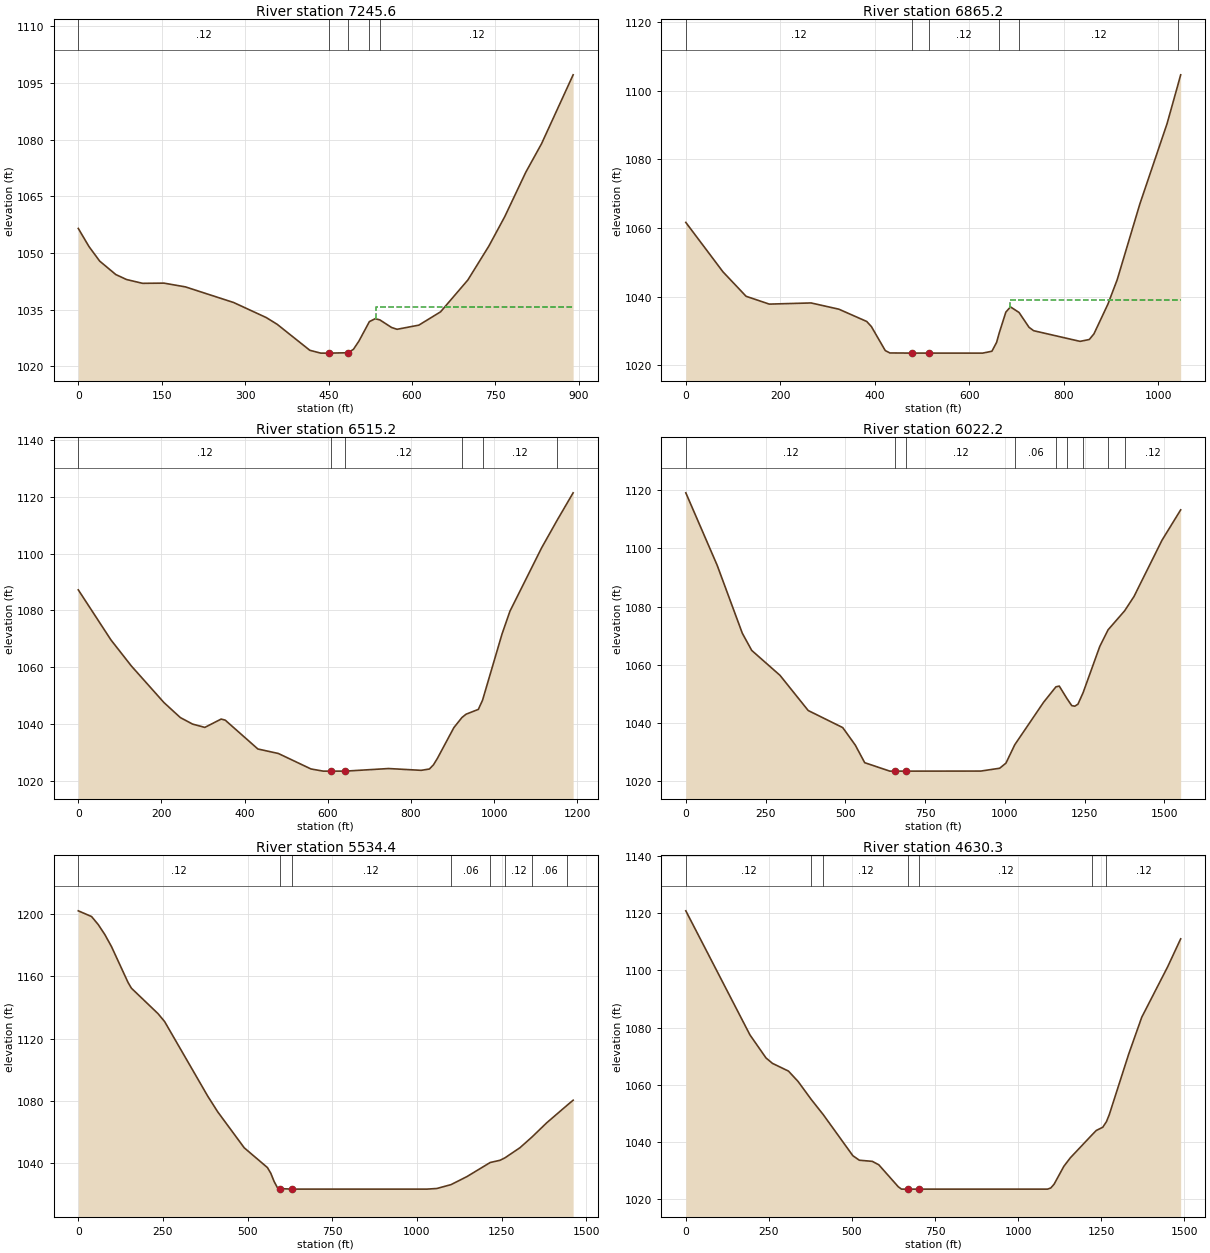
Type RM Length L Ch R = 1 ,7245.6  ,368.2,380.5,392.6
XS GIS Cut Line= 4
      1768565.84      244043.631     1768430.423      244298.839
     1768438.235      244710.298     1768545.006      244866.548
#Sta/Elev= 30
       0  1056.5    19.3 1051.69    38.5 1047.85    67.4  1044.3    86.7 1042.98
   115.6 1041.97   154.1 1042.02   192.6 1041.03   279.3 1036.89   337.9 1032.91
   357.5 1031.13   416.3 1024.24   435.9 1023.49  450.99 1023.49   484.9 1023.59
   494.7  1024.5   504.5 1026.66  523.381031.833   533.9 1032.61  542.221032.287
   563.3 1030.28   573.1  1029.8   612.3  1030.9   651.4 1034.43   700.4 1042.85
   738.3 1051.86   766.7 1059.61   804.5 1071.36   832.9 1078.93   889.7 1097.17
#Mann= 5 ,-1 , 0
       0     .12       0  450.99    .045       0   484.9     .12       0
  523.38    .016       0  542.22     .12       0
#XS Ineff= 2 , 0
                          534.57         1035.68
Permanent Ineff=
       F       F
Bank Sta=450.99,484.9
XS Rating Curve= 0 ,0
Exp/Cntr=0.3,0.1

Type RM Length L Ch R = 1 ,6865.2  ,350,350,350.1
XS GIS Cut Line= 3
     1768349.694       243874.36     1767899.173      244668.631
     1767802.819      244762.381
#Sta/Elev= 30
       0 1061.61    78.6  1047.2   127.6 1040.06   176.7 1037.78   265.1 1038.12
     324  1036.3   382.9 1032.72   392.8 1031.24   422.2 1024.23     432 1023.53
   479.4 1023.49   514.4 1023.49   628.4 1023.48     648 1024.03   657.9 1026.61
  663.521029.385   677.5 1035.44   687.3 1036.97  705.451035.336   726.6 1031.01
   736.4 1030.02   834.6 1026.91   854.2 1027.46     864  1029.1   893.5 1037.75
   913.2 1044.89   961.2    1067  1018.8 1090.43 1041.451101.576  1047.6 1104.67
#Mann= 6 ,-1 , 0
       0     .12       0   479.4    .045       0   514.4     .12       0
  663.52    .016       0  705.45     .12       0 1041.45    .016       0
#XS Ineff= 2 , 0
                          686.07         1038.92
Permanent Ineff=
       F       F
Bank Sta=479.4,514.4
XS Rating Curve= 0 ,0
Exp/Cntr=0.3,0.1

Type RM Length L Ch R = 1 ,6515.2  ,494.8,493,491.2
XS GIS Cut Line= 3
     1768125.735      243567.068     1767649.173      244403.006
     1767594.485       244624.36
#Sta/Elev= 30
       0 1087.24    78.6 1069.63   127.6 1060.48   206.2 1047.58   245.5 1042.32
   274.9 1040.03   304.4 1038.87   343.7  1041.8   353.5 1041.41     432 1031.27
   481.1  1029.7   559.7 1024.25   589.1 1023.49   607.4 1023.49   642.4 1023.49
   746.2  1024.4   824.8 1023.77   844.4 1024.23   854.2 1025.69     864 1028.04
   903.3 1038.78  922.811042.349   932.8 1043.52   962.2  1045.2  972.271048.417
  1019.2 1071.72  1038.2 1079.73  1114.2 1101.96 1152.151111.828  1190.2 1121.36
#Mann= 6 ,-1 , 0
       0     .12       0   607.4    .045       0   642.4     .12       0
  922.81    .016       0  972.27     .12       0 1152.15    .016       0
Bank Sta=607.4,642.4
XS Rating Curve= 0 ,0
Exp/Cntr=0.3,0.1

Type RM Length L Ch R = 1 ,6022.2  ,492,487.8,483.5
XS GIS Cut Line= 3
     1767709.069      243207.693     1767211.673      244267.589
     1767425.215      244582.693
#Sta/Elev= 30
       0 1119.05    98.4 1094.15   177.1 1070.84   206.6 1064.94   295.2 1056.39
   383.7  1044.3   491.9 1038.44   531.3 1032.43   560.8 1026.39   639.5 1023.49
   656.6 1023.49   691.6 1023.49   924.8 1023.51   983.9 1024.48  1003.6 1026.23
  1031.31032.555  1121.6 1047.13 1160.331052.433  1170.8 1052.69 1194.861048.415
  1209.8 1045.99  1219.6 1045.79  1229.4 1046.48 1245.471050.417  1297.7 1066.28
  1323.81072.008 1375.561078.519    1405 1083.44  1492.9 1102.78  1551.4  1113.2
#Mann= 9 ,-1 , 0
       0     .12       0   656.6    .045       0   691.6     .12       0
  1031.3     .06       0 1160.33     .12       0 1194.86    .016       0
 1245.47     .12       0  1323.8    .016       0 1375.56     .12       0
Bank Sta=656.6,691.6
XS Rating Curve= 0 ,0
Exp/Cntr=0.3,0.1

Type RM Length L Ch R = 1 ,5534.4  ,904.8,904.1,902.4
XS GIS Cut Line= 3
     1766995.527      243004.568      1767003.34      243543.631
     1766774.173       244436.86
#Sta/Elev= 30
       0 1201.96    39.2  1198.3    58.8 1193.19    78.4 1186.75      98 1179.05
     147    1156   156.8 1152.36   235.2 1136.08   254.9 1130.96   382.3 1083.11
   411.7 1073.07   490.1 1049.97   558.7 1037.28   568.6 1033.59   578.4 1028.35
   588.2 1024.34   594.71023.829   629.7 1023.49  1029.6 1023.48  1059.1  1023.9
 1100.721026.372  1147.4 1031.48 1216.521040.566  1245.4 1041.98 1259.82 1043.53
  1304.3 1050.04 1340.651057.073  1382.8 1065.93 1444.341077.418  1461.3 1080.51
#Mann= 8 ,-1 , 0
       0     .12       0   594.7    .045       0   629.7     .12       0
 1100.72     .06       0 1216.52    .016       0 1259.82     .12       0
 1340.65     .06       0 1444.34     .12       0
Bank Sta=594.7,629.7
XS Rating Curve= 0 ,0
Exp/Cntr=0.3,0.1

Type RM Length L Ch R = 1 ,4630.3  ,733.2,728.1,723.5
XS GIS Cut Line= 3
      1766440.84       242905.61      1766159.59       243249.36
     1765946.048      244272.798
#Sta/Elev= 30
       0 1120.82   193.1 1077.42   241.4 1069.37   260.7 1067.48     309 1064.77
   337.9 1061.15  377.211054.905  413.951049.506   502.8 1035.18   522.3  1033.6
   561.4  1033.2   580.9    1032   639.6 1024.31   649.3 1023.49   667.8 1023.49
   702.8 1023.49    1089 1023.49  1098.8 1023.91  1108.6 1025.22  1137.9 1031.46
  1157.4 1034.43 1223.661042.587  1235.6 1044.01  1255.1 1045.13 1266.161047.084
  1274.7 1049.55  1333.3 1070.77  1372.4  1083.6  1450.5 1101.27  1489.6 1111.02
#Mann= 7 ,-1 , 0
       0     .12       0  377.21     .06       0  413.95     .12       0
   667.8    .045       0   702.8     .12       0 1223.66    .016       0
 1266.16     .12       0
Bank Sta=667.8,702.8
XS Rating Curve= 0 ,0
Exp/Cntr=0.3,0.1

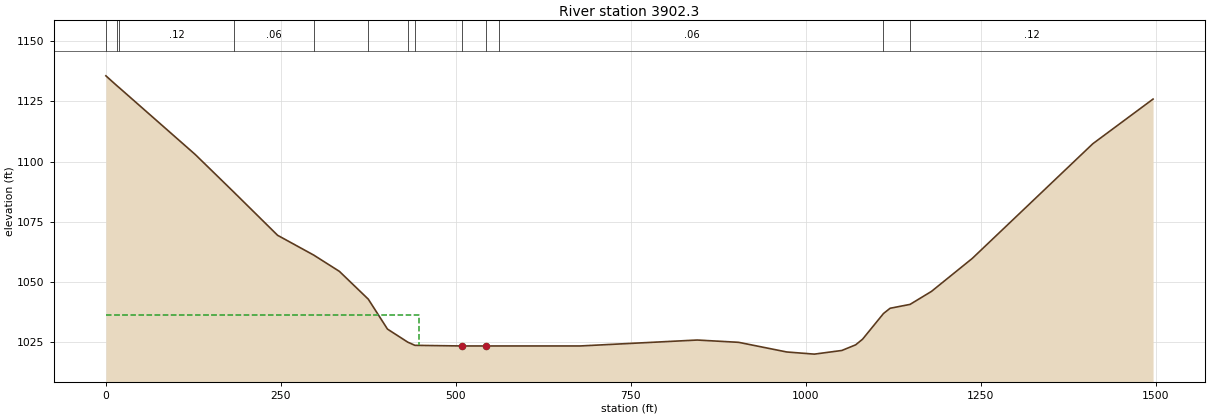
Type RM Length L Ch R = 1 ,3902.3  ,406.5,412.9,415.2
XS GIS Cut Line= 4
     1765104.034      242893.457     1765411.326      243263.249
     1765426.951      244001.096     1765557.159      244245.888
#Sta/Elev= 30
       0  1135.6   15.251131.619   18.961130.699   127.6 1102.96  182.421087.443
   245.3 1069.42  296.991061.191   333.6 1054.45  374.871042.914   402.3 1030.49
  431.271025.075  441.451023.749   508.2 1023.49   543.2 1023.49  562.27 1023.49
   677.6 1023.49   844.9 1025.95   903.9    1025   972.8 1020.99  1012.2  1020.1
  1051.5 1021.62  1071.2 1023.96  1081.1  1026.3 1110.971036.955  1120.4 1039.13
 1148.921040.742  1179.5 1046.13  1237.9 1059.84    1410 1107.41  1496.1 1125.95
#Mann= 13 ,-1 , 0
       0     .12       0   15.25     .06       0   18.96     .12       0
  182.42     .06       0  296.99     .12       0  374.87    .016       0
  431.27     .12       0  441.45     .06       0   508.2    .045       0
   543.2     .12       0  562.27     .06       0 1110.97    .016       0
 1148.92     .12       0
#XS Ineff= 2 , 0
          447.47 1036.42
Permanent Ineff=
       F       F
Bank Sta=508.2,543.2
XS Rating Curve= 0 ,0
Exp/Cntr=0.3,0.1