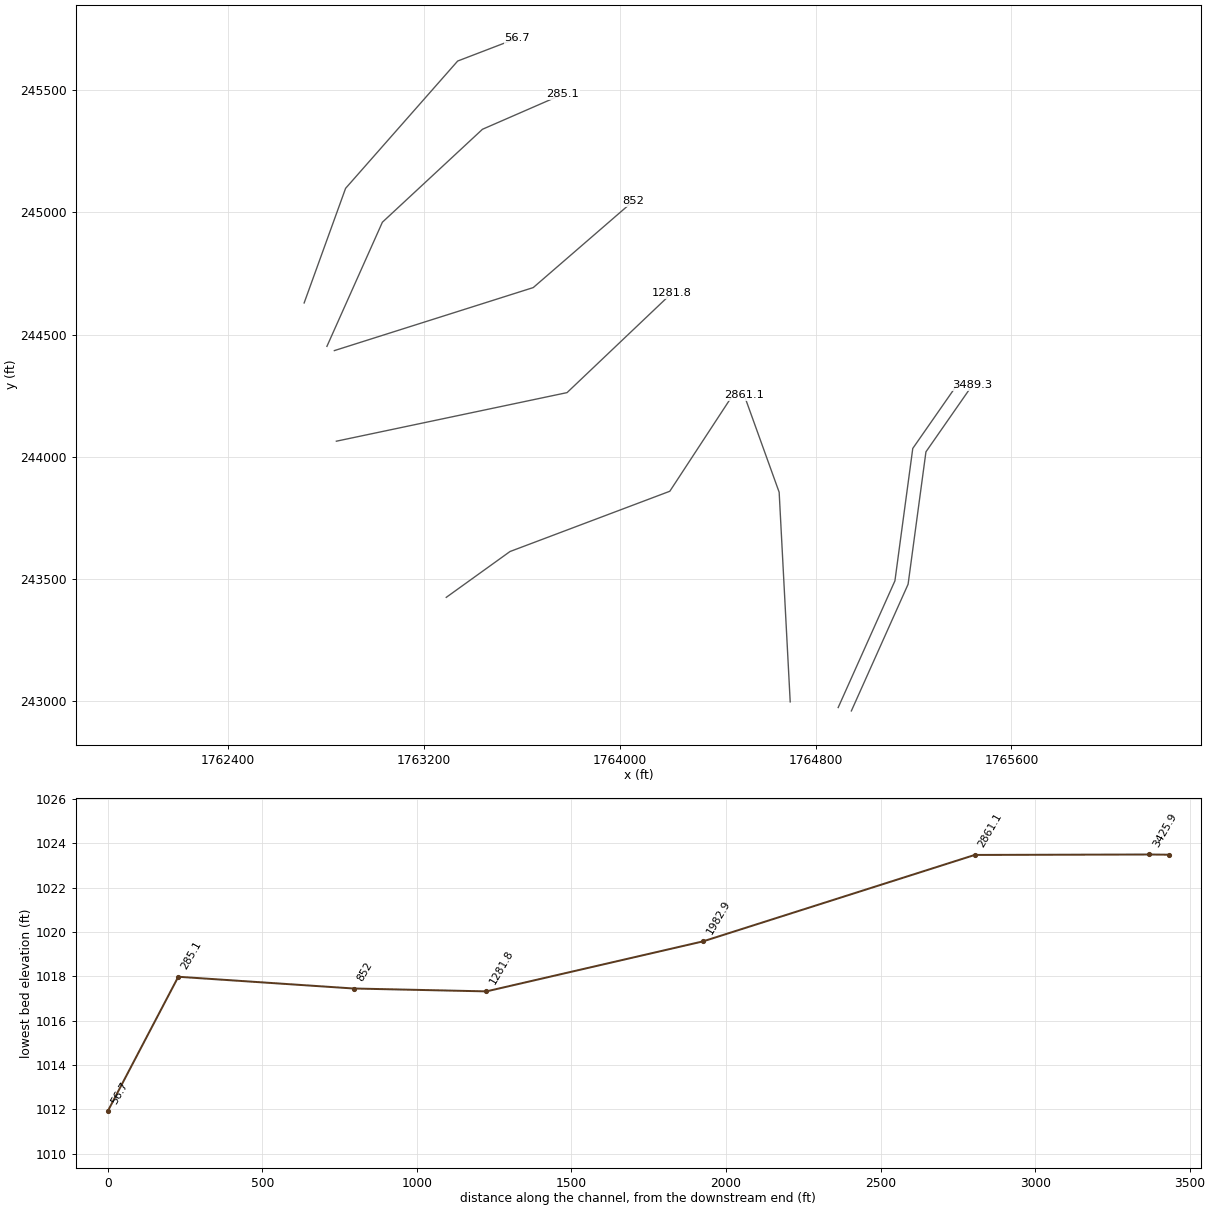
HEC-RAS study ELKCK.prj: ELKCK

--- ELKCK.g01 (geometry) --- (continued)

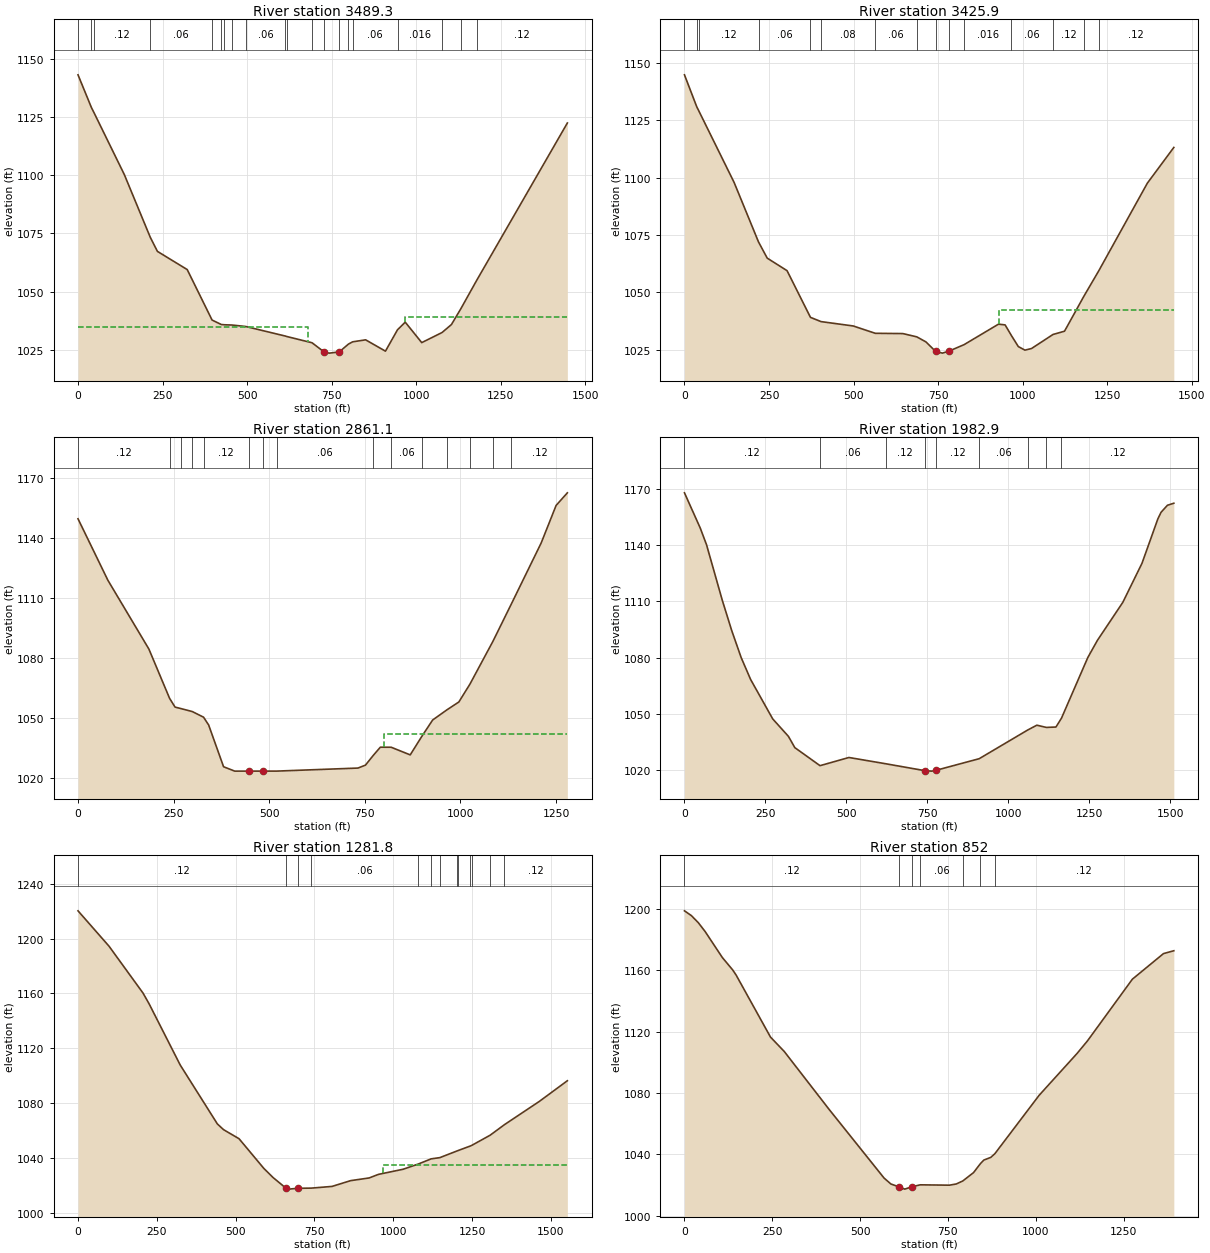
Type RM Length L Ch R = 1 ,3489.3  ,72.1,63.4,58.2
XS GIS Cut Line= 4
     1764945.867      242960.587     1765177.638      243478.816
     1765250.555      244020.483     1765440.659       244293.92
#Sta/Elev= 30
       0 1143.25    39.81129.127   47.51 1126.91     137 1100.32  213.821073.305
   234.9 1067.27     323 1059.45  396.511037.724   423.7 1035.81  432.241035.699
  456.12 1035.57  495.991034.952   613.11030.839  617.58 1030.64  692.171027.949
   728.7  1023.9   743.4 1023.49   772.6    1024  799.931027.389  812.331028.352
   850.7 1029.21   909.3 1024.34  944.921033.528   967.8 1036.82  1016.6 1028.01
 1076.751032.365  1104.5  1035.8 1132.651042.688 1178.831054.732  1447.3 1122.52
#Mann= 20 ,-1 , 0
       0     .12       0    39.8     .06       0   47.51     .12       0
  213.82     .06       0  396.51    .016       0   423.7     .08       0
  432.24     .06       0  456.12     .08       0  495.99     .06       0
   613.1     .08       0  617.58    .016       0  692.17     .12       0
   728.7    .045       0   772.6     .06       0  799.93     .12       0
  812.33     .06       0  944.92    .016       0 1076.75     .12       0
 1132.65    .016       0 1178.83     .12       0
#XS Ineff= 2 , 0
          680.29  1034.9   967.6         1039.16
Permanent Ineff=
       F       F
Bank Sta=728.7,772.6
XS Rating Curve= 0 ,0
Exp/Cntr=0.3,0.1

Type RM Length L Ch R = 1 ,3425.9  ,560.3,564.8,569.1
XS GIS Cut Line= 4
     1764892.048      242974.476     1765123.818      243492.705
     1765196.735      244034.372     1765386.839      244307.809
#Sta/Elev= 30
       0 1144.77   36.291130.858   41.751129.261   146.8 1097.88  218.971071.957
   244.7  1064.9   303.4 1059.43  372.671039.082  403.971037.236   499.2 1035.33
  564.371032.136   645.8 1032.02  687.161030.588   714.1  1028.4   742.91024.233
   762.9  1023.5   782.4 1024.38  827.161027.208   928.8 1036.13   948.3  1035.8
  967.011031.141   987.4 1026.35  1006.9 1024.81  1026.4  1025.5 1090.031031.634
    1124 1033.05 1181.641048.376 1224.981059.287  1368.9 1097.54  1447.3 1113.13
#Mann= 15 ,-1 , 0
       0     .12       0   36.29     .06       0   41.75     .12       0
  218.97     .06       0  372.67    .016       0  403.97     .08       0
  564.37     .06       0  687.16     .12       0   742.9    .045       0
   782.4     .12       0  827.16    .016       0  967.01     .06       0
 1090.03     .12       0 1181.64    .016       0 1224.98     .12       0
#XS Ineff= 2 , 0
                          929.62         1042.47
Permanent Ineff=
       F       F
Bank Sta=742.9,782.4
XS Rating Curve= 0 ,0
Exp/Cntr=0.3,0.1

Type RM Length L Ch R = 1 ,2861.1  ,906.5,878.2,849.4
XS GIS Cut Line= 3
     1764696.048      242997.624     1764650.909      243855.263
     1764508.548      244251.096
#Sta/Elev= 30
       0 1149.49    78.1  1118.8   185.4 1084.42  239.421059.834   253.7 1055.46
  269.031054.713  298.641053.239  328.241050.411   341.6 1046.52   380.6 1025.67
   409.9 1023.48   447.4 1023.49   482.4 1023.49  519.06 1023.49     732 1025.01
   751.5 1026.46  772.36 1031.41   790.5 1035.43  818.861035.403   868.6 1031.59
  898.831040.793   927.3 1049.01  964.511054.069   995.8 1058.01 1024.711066.911
 1084.711088.233 1133.431107.098    1211 1137.39  1250.1 1156.16  1279.5 1162.45
#Mann= 15 ,-1 , 0
       0     .12       0  239.42     .06       0  269.03    .016       0
  298.64     .08       0  328.24     .12       0   447.4    .045       0
   482.4     .12       0  519.06     .06       0  772.36    .016       0
  818.86     .06       0  898.83     .12       0  964.51     .06       0
 1024.71     .12       0 1084.71    .016       0 1133.43     .12       0
#XS Ineff= 2 , 0
                          800.41         1042.16
Permanent Ineff=
       F       F
Bank Sta=447.4,482.4
XS Rating Curve= 0 ,0
Exp/Cntr=0.3,0.1

Type RM Length L Ch R = 1 ,1982.9  ,704.5,701,697.7
XS GIS Cut Line= 4
     1763291.013      243425.156      1763551.43      243612.656
     1764204.208      243859.184     1764473.305      244270.642
#Sta/Elev= 30
       0  1167.7    48.6 1148.99    68.1 1140.06   116.7 1110.53   145.9 1094.35
     175    1080   204.2 1068.35   272.3 1047.39   320.9 1038.07   340.6 1032.08
  418.371022.484   507.6 1026.84  620.451023.524   742.81019.799   763.2 1019.58
   777.81020.085  909.551026.191 1059.081041.438  1087.5 1044.03 1116.781042.842
  1146.5 1043.05 1163.521047.744  1244.8 1080.03  1274.3 1089.13    1353 1109.45
    1412 1130.18  1461.2 1153.92    1471 1157.37  1490.6 1161.08  1510.3 1162.16
#Mann= 9 ,-1 , 0
       0     .12       0  418.37     .06       0  620.45     .12       0
   742.8    .045       0   777.8     .12       0  909.55     .06       0
 1059.08     .08       0 1116.78    .016       0 1163.52     .12       0
Bank Sta=742.8,777.8
XS Rating Curve= 0 ,0
Exp/Cntr=0.3,0.1

Type RM Length L Ch R = 1 ,1281.8  ,427.6,429.9,432.1
XS GIS Cut Line= 3
     1762842.087       244063.95     1763784.409       244262.67
     1764211.492       244668.92
#Sta/Elev= 30
       0 1220.19    98.3 1194.44   206.4 1160.19     226 1152.21   324.3 1107.78
   442.2 1064.82   461.9 1060.65     511 1054.04   589.6 1032.41   619.1 1025.72
   658.4 1018.28   668.2 1017.32   697.7 1017.92  740.521018.061   805.8 1019.29
   864.8  1023.5   923.7 1025.47   953.2 1028.07  1031.8 1031.83 1079.971035.655
 1120.511039.389 1147.941040.281 1203.361045.231 1206.351045.487 1244.781048.764
 1248.48 1049.12 1307.541056.627 1352.391064.229  1464.1 1081.35  1552.5 1096.33
#Mann= 13 ,-1 , 0
       0     .12       0   658.4    .045       0   697.7     .12       0
  740.52     .06       0 1079.97     .08       0 1120.51    .016       0
 1147.94     .12       0 1203.36     .06       0 1206.35     .12       0
 1244.78     .06       0 1248.48     .12       0 1307.54    .016       0
 1352.39     .12       0
#XS Ineff= 2 , 0
                           967.6         1035.05
Permanent Ineff=
       F       F
Bank Sta=658.4,697.7
XS Rating Curve= 0 ,0
Exp/Cntr=0.3,0.1

Type RM Length L Ch R = 1 ,852     ,556.7,566.8,576.8
XS GIS Cut Line= 3
     1762833.888      244434.545     1763646.388      244692.358
     1764055.242      245046.525
#Sta/Elev= 30
       0 1198.56    19.6 1195.46    39.2  1190.9    58.8 1185.09   107.8 1168.18
   137.2 1160.12     147 1156.78     245 1116.38   284.1 1107.03   411.5 1069.43
   568.3 1024.65   587.9 1020.76   611.71018.869   627.1 1017.45   646.7 1018.91
  671.171020.249   754.4 1020.02     774 1020.81  792.481022.776     823  1028.2
  842.721034.069   852.4 1036.37   872.1 1038.11  883.651040.482  1009.8 1078.51
    1118 1105.79  1147.5 1113.95  1275.3 1154.08  1363.8 1170.72  1393.3 1172.58
#Mann= 7 ,-1 , 0
       0     .12       0   611.7    .045       0   646.7     .12       0
  671.17     .06       0  792.48     .12       0  842.72    .016       0
  883.65     .12       0
Bank Sta=611.7,646.7
XS Rating Curve= 0 ,0
Exp/Cntr=0.3,0.1

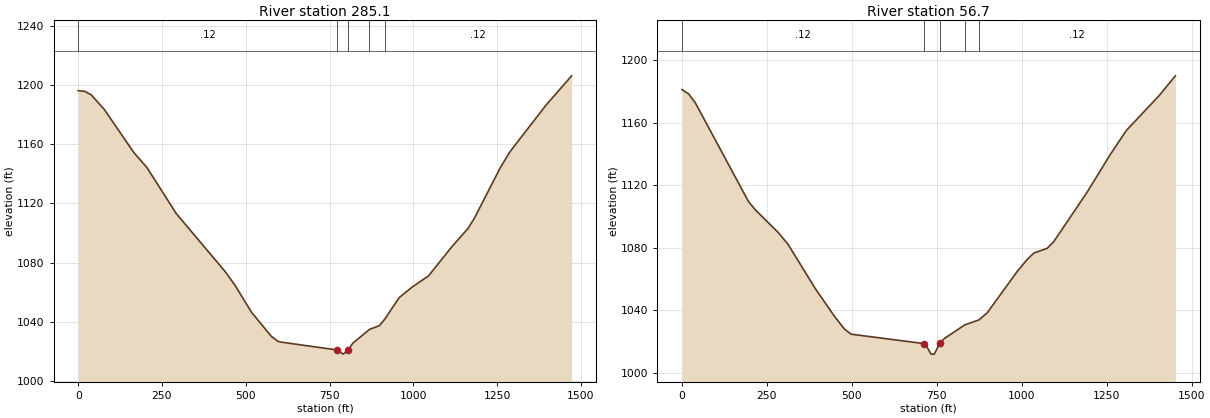
Type RM Length L Ch R = 1 ,285.1   ,226.3,228.5,230.8
XS GIS Cut Line= 4
     1762803.506      244451.906     1763030.068      244959.719
     1763438.923      245339.927     1763767.048      245483.156
#Sta/Elev= 30
       0  1196.4    19.5 1195.98      39 1193.58      78 1183.66   165.8 1154.56
   204.9 1144.43   292.7 1113.15     439 1073.77   468.3 1064.48     517 1046.39
   575.6  1030.2   595.2 1026.75     605 1026.14   771.6 1020.82   791.1 1017.98
   803.91020.472   820.5  1025.6  869.231034.723   898.9 1037.29  915.531041.855
   957.7 1056.23   996.8 1063.45  1045.8 1071.05  1114.4 1090.56  1162.8 1102.98
  1182.1 1109.92  1259.5 1144.21  1288.6 1155.11    1395 1186.33  1472.4 1206.47
#Mann= 5 ,-1 , 0
       0     .12       0   771.6    .045       0   803.9     .12       0
  869.23    .016       0  915.53     .12       0
Bank Sta=771.6,803.9
XS Rating Curve= 0 ,0
Exp/Cntr=0.3,0.1

Type RM Length L Ch R = 1 ,56.7    ,58.6,56.7,54.7
XS GIS Cut Line= 4
     1762710.462      244629.496     1762879.733      245098.246
     1763337.632       245619.08     1763580.688      245712.396
#Sta/Elev= 30
       0 1181.34    19.5 1178.59    39.1 1172.93   195.4 1109.76     215 1104.52
   283.4 1089.78   312.7 1082.06   390.9 1054.36   449.5 1035.88   478.8 1027.79
   498.4 1024.66     713 1018.63  716.92 1018.13  732.78  1011.9   742.6  1011.9
  758.36 1018.72   771.9 1021.87  832.98 1030.71  874.111033.801   898.8 1038.49
   986.8  1064.9  1016.1 1072.57  1035.6 1076.66  1074.7 1079.66  1094.2 1083.94
  1191.9 1115.48  1259.4 1139.37  1307.6 1155.11    1404 1177.42  1452.2 1190.17
#Mann= 5 ,-1 , 0
       0     .12       0     713    .045       0  758.36     .12       0
  832.98    .016       0  874.11     .12       0
Bank Sta=713,758.36
XS Rating Curve= 0 ,0
Exp/Cntr=0.3,0.1

Chan Stop Cuts=-1
Use User Specified Reach Order=0
Composite Channel Slope=5